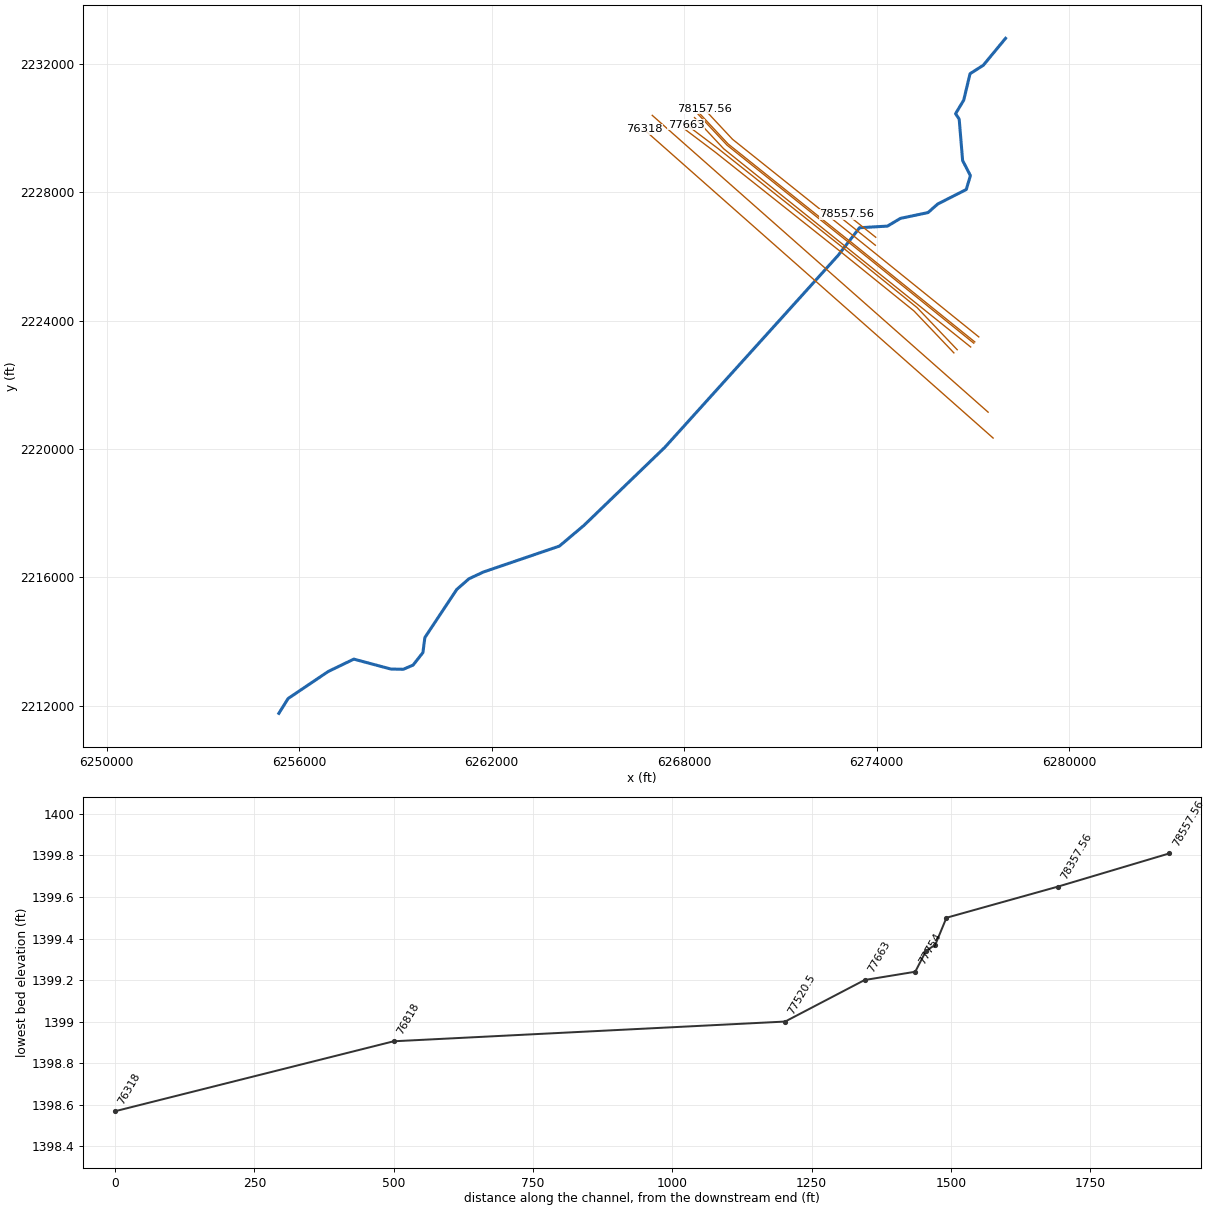
--- R3.prj (project) ---

Proj Title=San Jacinto Stage III Reach 3
Current Plan=p40
Default Exp/Contr=0.3,0.1
English Units
Geom File=g29
Geom File=g33
Flow File=f01
Flow File=f02
Flow File=f03
Flow File=f04
Flow File=f05
Flow File=f06
Flow File=f07
Flow File=f08
Unsteady File=u05
Unsteady File=u01
Unsteady File=u02
Unsteady File=u03
Unsteady File=u04
Plan File=p40
Plan File=p44
Y Axis Title=Elevation
X Axis Title(PF)=Stream Distance in Feet Above Confluence with Lake Elsinore
X Axis Title(XS)=Station
BEGIN DESCRIPTION:
Reach 3 Grading d/s of I-215
L.Johnson/Webb Associates
END DESCRIPTION:
DSS File=..\..\..\..\..\..\..\2015\15-0203\Hyd\HEC-RAS\SJRus_Ethanac.dss
DSS File=..\..\..\..\..\HYD\HEC-RAS\Preferred Alternative\SJR_LJ.dss
DSS File=dss
DSS Export Filename=G:\2009\09-0109\Hyd\HEC-RAS\NRMLF.dss
DSS Export Rating Curves= 0
DSS Export Rating Curve Sorted= 0
DSS Export Volume Flow Curves= 6
SJR Stage III   ,4               ,135810  ,4               ,122633
SJR Stage III   ,3               ,122303  ,3               ,116452
SJR Stage III   ,2               ,123614  ,2               ,116752
SJR Stage III   ,1               ,116114  ,1               ,109225
SJR Stage III   ,1               ,109097  ,1               ,77810
SJR Stage III   ,1               ,77477   ,1               ,66801
DXF Filename=..\..\..\..\..\..\..\2010\10-0261\LOMR\FEMA Submittal Package 24Jan2013\Hydraulic Models\Hyd\Old N=0.035 (8-224-09)\SJR STAGE III.
DXF OffsetX= 0
DXF OffsetY= 0
DXF ScaleX= 1
DXF ScaleY= 10

--- R3.p40 (plan) ---

Plan Title=Phase1
Program Version=5.03
Short Identifier=Phase1
Geom File=g29
Flow File=f08
Subcritical Flow
K Sum by GR= 0
Std Step Tol= 0.01
Critical Tol= 0.01
Num of Std Step Trials= 20
Max Error Tol= 0.3
Flow Tol Ratio= 0.001
Split Flow NTrial= 30
Split Flow Tol= 0.02
Split Flow Ratio= 0.02
Log Output Level= 0
Friction Slope Method= 1
Unsteady Friction Slope Method= 2
Unsteady Bridges Friction Slope Method= 1
Calc Critical at every XS
Parabolic Critical Depth
Global Vel Dist= 0 , 0 , 0
Global Log Level= 0
CheckData=True
Encroach Param=-1 ,0,0, 0
Optimized Weir=San Jacinto Rive,Reach 3         ,60723
BEGIN DESCRIPTION:
SRJ Reach 3
Phase 1 Improvements
JCC
7 FEB 2017
END DESCRIPTION:
Computation Interval=1MIN
Output Interval=1HOUR
Instantaneous Interval=1HOUR
Mapping Interval=1HOUR
Run HTab= 0
Run UNet= 0
Run Sediment= 0
Run PostProcess= 0
Run WQNet= 0
Run RASMapper= 0
UNET Theta= 1
UNET Theta Warmup= 1
UNET ZTol= 0.02
UNET ZSATol= 0.02
UNET MxIter= 20
UNET Max Iter WO Improvement= 0
UNET MaxInSteps= 0
UNET DtIC= 0
UNET DtMin= 0
UNET MaxCRTS= 20
UNET WFStab= 2
UNET SFStab= 1
UNET WFX= 1
UNET SFX= 1
UNET DSS MLevel= 4
UNET Pardiso=0
UNET DZMax Abort= 100
UNET Use Existing IB Tables=-1
UNET Froude Reduction=False
UNET Froude Limit= 0.8
UNET Froude Power= 4
UNET Time Slicing=0,0, 5
UNET D1 Cores= 0
UNET D2 Coriolis=0
UNET D2 Cores= 0
UNET D2 Theta= 1
UNET D2 Theta Warmup= 1
UNET D2 Z Tol= 0.01
UNET D2 Volume Tol= 0.01
UNET D2 Max Iterations= 20
UNET D2 Equation= 0
UNET D2 RampUpFraction=0.1
UNET D2 TimeSlices= 1
UNET D2 BCVolumeCheck=0
UNET D1D2 MaxIter= 0
UNET D1D2 ZTol=0.01
UNET D1D2 QTol=0.1
UNET D1D2 MinQTol=1
DSS File=dss
Write IC File= 0
Write IC File at Fixed DateTime=0
Write IC File at Sim End=0
Echo Input=False
Echo Parameters=False
Echo Output=False
Write Detailed= 0
HDF Write Warmup=0
HDF Write Time Slices=0
HDF Flush=0
HDF Face Node Velocities=0
HDF Compression= 1
HDF Chunk Size= 1
HDF Spatial Parts= 1
HDF Use Max Rows=0
HDF Fixed Rows= 1
Calibration Method= 0
Calibration Iterations= 20
Calibration Max Change=0.05
Calibration Tolerance=0.2
Calibration Maximum=1.5
Calibration Minimum=0.5
Calibration Optimization Method= 1
WQ AD Non Conservative
WQ ULTIMATE=-1
WQ Max Comp Step=1HOUR
WQ Output Interval=15MIN
WQ Output Selected Increments= 0
WQ Output face flow=0
WQ Output face velocity=0
WQ Output face area=0
WQ Output face dispersion=0
WQ Output cell volume=0
WQ Output cell surface area=0
WQ Output cell continuity=0
WQ Output cumulative cell continuity=0
WQ Output face conc=0
WQ Output face dconc_dx=0
WQ Output face courant=0
WQ Output face peclet=0
WQ Output face adv mass=0
WQ Output face disp mass=0
WQ Output cell mass=0
WQ Output cell source sink temp=0
WQ Output nsm pathways=0
WQ Output nsm derived pathways=0
WQ Output MaxMinRange=-1
WQ Daily Max Min Mean=-1
WQ Daily Range=0
WQ Daily Time=0
WQ Create Restart=0
WQ Fixed Restart=0
WQ System Summary=0
WQ Write To DSS=0
WQ Use Fixed Temperature=0
Sorting and Armoring Iterations= 10
XS Update Threshold= 0.02
Bed Roughness Predictor= 0
Hydraulics Update Threshold= 0.02
Energy Slope Method= 1
Volume Change Method= 1
Sediment Retention Method= 0
XS Weighting Method= 0
Number of US Weighted Cross Sections= 1
Number of DS Weighted Cross Sections= 1
Upstream XS Weight=0
Main XS Weight=1
Downstream XS Weight=0
Number of DS XS's Weighted with US Boundary= 1
Upstream Boundary Weight= 1
Weight of XSs Associated with US Boundary= 0
Number of US XS's Weighted with DS Boundary= 1
Downstream Boundary Weight= 0.5
Weight of XSs Associated with DS Boundary= 0.5
Percentile Method= 0
Sediment Output Level= 4
Mass or Volume Output= 0
Output Increment Type= 1
Profile and TS Output Increment= 1
XS Output Flag= 0
XS Output Increment= 10
Write Gradation File= 0
Read Gradation Hotstart= 0
Write HDF5 File= 1
Write DSS Sediment File= 0
SV Curve= 0
Specific Gage Flag= 0

--- R3.p44 (plan) ---

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Plan Title=Phase 2 Ultimate
Short Identifier=Phase 2c-blocked
Geom File=g33
Flow File=f08
San Jacinto River
Reach 3 (DS of I-215)
Phase 2 Conditions with blocked area representing where fill can be placed and the floodplain encroachement can occur
jcc 7 FEB 2017

--- R3.f08 (steady flow) ---

Flow Title=Rating Curve
Program Version=5.01
Number of Profiles= 26
Profile Names=PF 1,PF 2,PF 3,PF 4,PF 5,PF 6,PF 7,PF 8,PF 9,PF 10,PF 11,PF 12,PF 13,PF 14,PF 15,PF 16,PF 17,PF 18,PF 19,PF 20,PF 21,PF 22,PF 23,PF 24,PF 25,PF 26
River Rch & RM=San Jacinto Rive,Reach 3         ,78557.56
     500    1000    2000    3000    4000    5000    6000    7000    8000    9000
   10000   11000   12000   13000   14800   15000   16000   17000   18000   19000
   20000   21000   22000   23000   24000   25000
River Rch & RM=San Jacinto Rive,Reach 3         ,76818
     500    1000    2000    3000    4000    5000    6000    7000    8000    9000
   10000   11000   12000    1000   14800   15000   16000   17000   18000   19000
   20000   21000   22000   23000   24000   25000
Boundary for River Rch & Prof#=San Jacinto Rive,Reach 3         , 1
Up Type= 3
Up Slope=0.0005
Dn Type= 3
Dn Slope=0.002
Boundary for River Rch & Prof#=San Jacinto Rive,Reach 3         , 2
Up Type= 3
Up Slope=0.0005
Dn Type= 3
Dn Slope=0.002
Boundary for River Rch & Prof#=San Jacinto Rive,Reach 3         , 3
Up Type= 3
Up Slope=0.0005
Dn Type= 3
Dn Slope=0.002
Boundary for River Rch & Prof#=San Jacinto Rive,Reach 3         , 4
Up Type= 3
Up Slope=0.0005
Dn Type= 3
Dn Slope=0.002
Boundary for River Rch & Prof#=San Jacinto Rive,Reach 3         , 5
Up Type= 3
Up Slope=0.0005
Dn Type= 3
Dn Slope=0.002
Boundary for River Rch & Prof#=San Jacinto Rive,Reach 3         , 6
Up Type= 3
Up Slope=0.0005
Dn Type= 3
Dn Slope=0.002
Boundary for River Rch & Prof#=San Jacinto Rive,Reach 3         , 7
Up Type= 3
Up Slope=0.0005
Dn Type= 3
Dn Slope=0.002
Boundary for River Rch & Prof#=San Jacinto Rive,Reach 3         , 8
Up Type= 3
Up Slope=0.0005
Dn Type= 3
Dn Slope=0.002
Boundary for River Rch & Prof#=San Jacinto Rive,Reach 3         , 9
Up Type= 3
Up Slope=0.0005
Dn Type= 3
Dn Slope=0.002
Boundary for River Rch & Prof#=San Jacinto Rive,Reach 3         , 10
Up Type= 3
Up Slope=0.0005
Dn Type= 3
Dn Slope=0.002
Boundary for River Rch & Prof#=San Jacinto Rive,Reach 3         , 11
Up Type= 3
Up Slope=0.0005
Dn Type= 3
Dn Slope=0.002
Boundary for River Rch & Prof#=San Jacinto Rive,Reach 3         , 12
Up Type= 3
Up Slope=0.0005
Dn Type= 3
Dn Slope=0.002
Boundary for River Rch & Prof#=San Jacinto Rive,Reach 3         , 13
Up Type= 3
Up Slope=0.0005
Dn Type= 3
Dn Slope=0.002
Boundary for River Rch & Prof#=San Jacinto Rive,Reach 3         , 14
Up Type= 3
Up Slope=0.0005
Dn Type= 3
Dn Slope=0.002
Boundary for River Rch & Prof#=San Jacinto Rive,Reach 3         , 15
Up Type= 3
Up Slope=0.0005
Dn Type= 3
Dn Slope=0.002
Boundary for River Rch & Prof#=San Jacinto Rive,Reach 3         , 16
Up Type= 3
Up Slope=0.0005
Dn Type= 3
Dn Slope=0.002
Boundary for River Rch & Prof#=San Jacinto Rive,Reach 3         , 17
Up Type= 3
Up Slope=0.0005
Dn Type= 3
Dn Slope=0.002
Boundary for River Rch & Prof#=San Jacinto Rive,Reach 3         , 18
Up Type= 3
Up Slope=0.0005
Dn Type= 3
Dn Slope=0.002
Boundary for River Rch & Prof#=San Jacinto Rive,Reach 3         , 19
Up Type= 3
Up Slope=0.0005
Dn Type= 3
Dn Slope=0.002
Boundary for River Rch & Prof#=San Jacinto Rive,Reach 3         , 20
Up Type= 3
Up Slope=0.0005
Dn Type= 3
Dn Slope=0.002
Boundary for River Rch & Prof#=San Jacinto Rive,Reach 3         , 21
Up Type= 3
Up Slope=0.0005
Dn Type= 3
Dn Slope=0.002
Boundary for River Rch & Prof#=San Jacinto Rive,Reach 3         , 22
Up Type= 3
Up Slope=0.0005
Dn Type= 3
Dn Slope=0.002
Boundary for River Rch & Prof#=San Jacinto Rive,Reach 3         , 23
Up Type= 3
Up Slope=0.0005
Dn Type= 3
Dn Slope=0.002
Boundary for River Rch & Prof#=San Jacinto Rive,Reach 3         , 24
Up Type= 3
Up Slope=0.0005
Dn Type= 3
Dn Slope=0.002
Boundary for River Rch & Prof#=San Jacinto Rive,Reach 3         , 25
Up Type= 3
Up Slope=0.0005
Dn Type= 3
Dn Slope=0.002
Boundary for River Rch & Prof#=San Jacinto Rive,Reach 3         , 26
Up Type= 3
Up Slope=0.0005
Dn Type= 3
Dn Slope=0.002
DSS Import GetInterval= 0
DSS Import GetPeak= 0
DSS Import FillOption= 0

--- R3.f01 (steady flow) ---

Flow Title=Flow 01
Program Version=4.10
Number of Profiles= 1
Profile Names=PF 1
DSS Import GetInterval= 0
DSS Import GetPeak= 0
DSS Import FillOption= 0

--- R3.f02 (steady flow) ---

Flow Title=Flow 02
Program Version=4.10
Number of Profiles= 1
Profile Names=PF 1
DSS Import GetInterval= 0
DSS Import GetPeak= 0
DSS Import FillOption= 0

--- R3.f03 (steady flow) ---

Flow Title=Flow 03
Program Version=4.10
Number of Profiles= 1
Profile Names=PF 1
River Rch & RM=SJR Stage III,4               ,63818
   27700
Boundary for River Rch & Prof#=SJR Stage III,4               , 1
Up Type= 3
Up Slope=0.00031
Dn Type= 1
Dn Known WS=1406.44
DSS Import GetInterval= 0
DSS Import GetPeak= 0
DSS Import FillOption= 0

--- R3.f04 (steady flow) ---

Flow Title=Steady flow
Program Version=4.10
Number of Profiles= 1
Profile Names=PF 1
River Rch & RM=SJR Stage III,4               ,66817
   13025
Boundary for River Rch & Prof#=SJR Stage III,4               , 1
Up Type= 3
Up Slope=0.00031
Dn Type= 3
Dn Slope=0.002
DSS Import GetInterval= 0
DSS Import GetPeak= 0
DSS Import FillOption= 0

--- R3.f05 (steady flow) ---

Flow Title=Option 2B-RevA
Program Version=4.10
Number of Profiles= 1
Profile Names=PF 1
River Rch & RM=SJR Stage III,4               ,69317
   23450
Boundary for River Rch & Prof#=SJR Stage III,4               , 1
Up Type= 0
Dn Type= 1
Dn Known WS=1404.73
DSS Import GetInterval= 0
DSS Import GetPeak= 0
DSS Import FillOption= 0

--- R3.f06 (steady flow) ---

Flow Title=Hybrid1A2
Program Version=4.10
Number of Profiles= 1
Profile Names=PF 1
River Rch & RM=SJR Stage III,4               ,80328
   15285
Boundary for River Rch & Prof#=SJR Stage III,4               , 1
Up Type= 0
Dn Type= 3
Dn Slope=0.002
DSS Import GetInterval= 0
DSS Import GetPeak= 0
DSS Import FillOption= 0

--- R3.f07 (steady flow) ---

Flow Title=FEMA Steady Flows
Program Version=4.10
Number of Profiles= 24
Profile Names=PF 1,PF 2,PF 3,PF 4,PF 5,PF 6,PF 7,PF 8,PF 9,PF 10,PF 11,PF 12,PF 13,PF 14,PF 15,PF 16,PF 17,PF 18,PF 19,PF 20,PF 21,PF 22,PF 23,PF 24
River Rch & RM=SJR Stage III,4               ,80328
    1000    2000    3000    4000    5000    6000    7000    8000    9000   10000
   11000   12000   13000   14000   15000   16000   17000   18000   19000   20000
   21000   22000   23000   24000
Boundary for River Rch & Prof#=SJR Stage III,4               , 1
Up Type= 0
Dn Type= 3
Dn Slope=0.002
DSS Import GetInterval= 0
DSS Import GetPeak= 0
DSS Import FillOption= 0

--- R3.u01 (unsteady flow) ---

Flow Title=SJR 500 Year Inflow Hydrogaphs
Program Version=4.10
Use Restart= 0
Initial Flow Loc=SJR Stage III   ,4               ,135810  ,400
Boundary Location=SJR Stage III   ,4               ,53850   ,        ,                ,                ,
Friction Slope=0.002
Boundary Location=SJR Stage III   ,4               ,136855  ,        ,                ,                ,
Interval=1HOUR
Flow Hydrograph= 72
       0      97     249     502     870    1398    1927    2543    3253    5000
    9973   17107   27278   40406   54571   67344   80199   87110   86411   76482
   61095   45734   35133   28730   24473   21198   18516   16222   14244   12562
   11164    9971    8943    8115    7442    6909    6435    5995    5613    5263
    4910    4577    4268    3953    3627    3307    3030    2817    2633    2441
    2228    2038    1887    1715    1492    1256    1047     907     840     806
     785     775     767     759     746     718     667     601     534     449
     335     210
Flow Hydrograph QMin= 400
Use DSS=False
CWMS InputPosition= 0
Use Fixed Start Time=False
Fixed Start Date/Time=23SEP2008,10:00
Is Critical Boundary=False
Boundary Location=SJR Stage III   ,4               ,135254  ,132446  ,                ,                ,
Interval=1HOUR
Uniform Lateral Inflow Hydrograph= 72
       0      24      53      67      75     114     141     159     208     268
     748    1045    1372    1976    3267    3336    3348    2277    1336     917
     702     563     464     382     312     224     154     108      83      57
      36      17       7       5       3       2       2       1       1       0
       0       0       0       0       0       0       0       0       0       0
       0       0       0       0       0       0       0       0       0       0
       0       0       0       0       0       0       0       0       0       0
       0       0
Use DSS=False
CWMS InputPosition= 0
Use Fixed Start Time=False
Is Critical Boundary=False
Boundary Location=SJR Stage III   ,4               ,129582  ,127728  ,                ,                ,
Interval=1HOUR
Uniform Lateral Inflow Hydrograph= 72
       0      20      49      62      69     104     130     164     201     250
     553     803    1162    1658    3113    3125    3216    2218    1269     862
     651     522     427     348     277     202     134      96      71      46
      26      11       6       4       3       2       1       1       0       0
       0       0       0       0       0       0       0       0       0       0
       0       0       0       0       0       0       0       0       0       0
       0       0       0       0       0       0       0       0       0       0
       0       0
Use DSS=False
CWMS InputPosition= 0
Use Fixed Start Time=False
Is Critical Boundary=False
Boundary Location=SJR Stage III   ,4               ,114894  ,112783  ,                ,                ,
Interval=1HOUR
Uniform Lateral Inflow Hydrograph= 72
       0      16      36      44      78      90     102     129     147     193
     350     513     725    1082    2263    2082    2073    1175     485     240
     134      86      60      51      49      33      12       5       2       1
       0       0       0       0       0       0       0       0       0       0
       0       0       0       0       0       0       0       0       0       0
       0       0       0       0       0       0       0       0       0       0
       0       0       0       0       0       0       0       0       0       0
       0       0
Use DSS=False
CWMS InputPosition= 0
Use Fixed Start Time=False
Is Critical Boundary=False
Boundary Location=SJR Stage III   ,4               ,102829  ,102329  ,                ,                ,
Interval=1HOUR
Uniform Lateral Inflow Hydrograph= 72
       0       8      35      63      94     134     155     176     210     272
     410     724    1074    1420    2493    3536    3720    3309    2170    1286
     908     694     560     466     396     330     258     193     145     108
      74      52      40      33      29      25      19      13       6       2
       1       1       1       0       0       0       0       0       0       0
       0       0       0       0       0       0       0       0       0       0
       0       0       0       0       0       0       0       0       0       0
       0       0
Use DSS=False
CWMS InputPosition= 0
Use Fixed Start Time=False
Is Critical Boundary=False
Boundary Location=SJR Stage III   ,4               ,81828   ,79328   ,                ,                ,
Interval=1HOUR
Uniform Lateral Inflow Hydrograph= 72
       0      16     154     282     378     495     648     777     918    1242
    2849    5723    7213    8265   12944   16621   17335   15140    9062    4805
    3381    2570    1978    1586    1289    1035     788     577     451     365
     288     242     203     169     155     149     145     142     139     137
     135     134     133     131     131     130     129     128     128     127
     127     127     126     126     126     126     125     125     125     125
     124     124     124     124     123     123     123     123     123     122
     122     122
Use DSS=False
CWMS InputPosition= 0
Use Fixed Start Time=False
Is Critical Boundary=False
Boundary Location=SJR Stage III   ,4               ,79328   ,78328   ,                ,                ,
Interval=1HOUR
Uniform Lateral Inflow Hydrograph= 72
       0       4      17      20      21      30      40      43      56      71
     181     356     390     478     911     949     931     638     215      94
      51      32      24      22      22      18       6       2       1       0
       0       0       0       0       0       0       0       0       0       0
       0       0       0       0       0       0       0       0       0       0
       0       0       0       0       0       0       0       0       0       0
       0       0       0       0       0       0       0       0       0       0
       0       0
Use DSS=False
CWMS InputPosition= 0
Use Fixed Start Time=False
Is Critical Boundary=False
Boundary Location=SJR Stage III   ,4               ,69317   ,67817   ,                ,                ,
Interval=1HOUR
Uniform Lateral Inflow Hydrograph= 72
       0      16      76     115     128     167     227     261     323     414
     900    1829    2307    2765    4758    5765    5841    4708    2507    1267
     824     575     421     298     224     157      71      32      19      12
       7       4       2       1       0       0       0       0       0       0
       0       0       0       0       0       0       0       0       0       0
       0       0       0       0       0       0       0       0       0       0
       0       0       0       0       0       0       0       0       0       0
       0       0
Use DSS=False
CWMS InputPosition= 0
Use Fixed Start Time=False
Is Critical Boundary=False

--- R3.u02 (unsteady flow) ---

Flow Title=SJR 50 Year Inflow Hydrogaphs
Program Version=4.10
Use Restart= 0
Initial Flow Loc=SJR Stage III   ,4               ,135810  ,400
Boundary Location=SJR Stage III   ,4               ,53850   ,        ,                ,                ,
Friction Slope=0.002
Boundary Location=SJR Stage III   ,4               ,136855  ,        ,                ,                ,
Interval=1HOUR
Flow Hydrograph= 72
       0      64     175     385     680    1060    1438    1865    2330    2949
    4574    7439   12015   19212   28131   36719   45690   51269   51730   45968
   36625   27327   20974   17171   14637   12670   11041    9651    8464    7458
    6623    5904    5286    4792    4391    4074    3793    3531    3307    3105
    2902    2709    2530    2347    2154    1962    1794    1666    1556    1446
    1325    1218    1135    1036     900     753     624     537     497     475
     462     455     449     444     437     426     402     368     332     282
     211     132
Flow Hydrograph QMin= 400
Use DSS=False
CWMS InputPosition= 0
Use Fixed Start Time=False
Fixed Start Date/Time=23SEP2008,10:00
Is Critical Boundary=False
Boundary Location=SJR Stage III   ,4               ,135254  ,132446  ,                ,                ,
Interval=1HOUR
Uniform Lateral Inflow Hydrograph= 72
       0      12      27      36      60      79      98     115     144     189
     260     364     443     808    1730    1776    1793    1186     701     480
     364     293     242     199     162     115      79      57      45      31
      19       9       4       2       2       1       1       1       0       0
       0       0       0       0       0       0       0       0       0       0
       0       0       0       0       0       0       0       0       0       0
       0       0       0       0       0       0       0       0       0       0
       0       0
Use DSS=False
CWMS InputPosition= 0
Use Fixed Start Time=False
Is Critical Boundary=False
Boundary Location=SJR Stage III   ,4               ,129582  ,127728  ,                ,                ,
Interval=1HOUR
Uniform Lateral Inflow Hydrograph= 72
       0      10      28      47      60      82      98     116     140     182
     241     284     307     600    1573    1556    1629    1083     624     441
     331     262     214     174     137      99      67      50      37      23
      13       6       3       2       1       1       1       0       0       0
       0       0       0       0       0       0       0       0       0       0
       0       0       0       0       0       0       0       0       0       0
       0       0       0       0       0       0       0       0       0       0
       0       0
Use DSS=False
CWMS InputPosition= 0
Use Fixed Start Time=False
Is Critical Boundary=False
Boundary Location=SJR Stage III   ,4               ,114894  ,112783  ,                ,                ,
Interval=1HOUR
Uniform Lateral Inflow Hydrograph= 72
       0       7      22      33      42      56      68      84     105     134
     179     194     211     402    1144     999    1005     526     220     124
      71      43      29      24      24      16       6       2       1       0
       0       0       0       0       0       0       0       0       0       0
       0       0       0       0       0       0       0       0       0       0
       0       0       0       0       0       0       0       0       0       0
       0       0       0       0       0       0       0       0       0       0
       0       0
Use DSS=False
CWMS InputPosition= 0
Use Fixed Start Time=False
Is Critical Boundary=False
Boundary Location=SJR Stage III   ,4               ,102829  ,102329  ,                ,                ,
Interval=1HOUR
Uniform Lateral Inflow Hydrograph= 72
       0       4      19      41      58      79     103     129     160     202
     258     315     352     467    1104    1740    1840    1615    1030     623
     447     341     274     225     192     159     125      95      71      53
      36      25      19      15      14      13       9       6       3       1
       1       0       0       0       0       0       0       0       0       0
       0       0       0       0       0       0       0       0       0       0
       0       0       0       0       0       0       0       0       0       0
       0       0
Use DSS=False
CWMS InputPosition= 0
Use Fixed Start Time=False
Is Critical Boundary=False
Boundary Location=SJR Stage III   ,4               ,81828   ,79328   ,                ,                ,
Interval=1HOUR
Uniform Lateral Inflow Hydrograph= 72
       0      16     114     197     271     359     458     545     669     828
    1139    2136    2789    3390    6671    9339    9904    8560    5139    2826
    2032    1570    1235    1007     779     559     378     251     183     160
     149     141     135     131     127     125     123     122     121     120
     119     118     117     117     116     115     115     114     114     113
     113     112     112     112     111     111     111     110     110     110
     109     109     109     108     108     108     107     107     107     106
     106     106
Use DSS=False
CWMS InputPosition= 0
Use Fixed Start Time=False
Is Critical Boundary=False
Boundary Location=SJR Stage III   ,4               ,79328   ,78328   ,                ,                ,
Interval=1HOUR
Uniform Lateral Inflow Hydrograph= 72
       0       2       9      10      17      21      24      29      39      47
      62     120     132     183     491     531     526     345     118      56
      28      17      13      11      11       9       3       1       0       0
       0       0       0       0       0       0       0       0       0       0
       0       0       0       0       0       0       0       0       0       0
       0       0       0       0       0       0       0       0       0       0
       0       0       0       0       0       0       0       0       0       0
       0       0
Use DSS=False
CWMS InputPosition= 0
Use Fixed Start Time=False
Is Critical Boundary=False
Boundary Location=SJR Stage III   ,4               ,69317   ,67817   ,                ,                ,
Interval=1HOUR
Uniform Lateral Inflow Hydrograph= 72
       0       8      39      59      90     120     142     171     222     278
     357     627     790    1029    2407    3156    3252    2563    1350     702
     457     314     231     161     119      81      37      17      10       6
       4       2       1       0       0       0       0       0       0       0
       0       0       0       0       0       0       0       0       0       0
       0       0       0       0       0       0       0       0       0       0
       0       0       0       0       0       0       0       0       0       0
       0       0
Use DSS=False
CWMS InputPosition= 0
Use Fixed Start Time=False
Is Critical Boundary=False

--- R3.u03 (unsteady flow) ---

Flow Title=SJR 10 Year Inflow Hydrogaphs
Program Version=4.10
Use Restart= 0
Initial Flow Loc=SJR Stage III   ,4               ,135810  ,400
Boundary Location=SJR Stage III   ,4               ,53850   ,        ,                ,                ,
Friction Slope=0.002
Boundary Location=SJR Stage III   ,4               ,136855  ,        ,                ,                ,
Interval=1HOUR
Flow Hydrograph= 72
       0      48     130     275     487     765    1049    1364    1704    2124
    2660    3505    4801    7224   11342   16177   21895   26257   27405   24593
   19589   14589   11191    9172    7827    6776    5916    5180    4539    3985
    3524    3130    2793    2527    2313    2143    1992    1853    1734    1630
    1526    1428    1338    1243    1141    1038     950     882     821     760
     699     650     614     565     490     406     333     285     263     251
     243     238     234     231     226     221     213     200     187     163
     123      77
Flow Hydrograph QMin= 400
Use DSS=False
CWMS InputPosition= 0
Use Fixed Start Time=False
Fixed Start Date/Time=23SEP2008,10:00
Is Critical Boundary=False
Boundary Location=SJR Stage III   ,4               ,135254  ,132446  ,                ,                ,
Interval=1HOUR
Uniform Lateral Inflow Hydrograph= 72
       0       9      23      31      43      58      70      84     103     133
     173     192     207     314     776     736     726     445     280     204
     160     133     110      91      72      50      35      25      20      13
       8       4       2       1       1       1       0       0       0       0
       0       0       0       0       0       0       0       0       0       0
       0       0       0       0       0       0       0       0       0       0
       0       0       0       0       0       0       0       0       0       0
       0       0
Use DSS=False
CWMS InputPosition= 0
Use Fixed Start Time=False
Is Critical Boundary=False
Boundary Location=SJR Stage III   ,4               ,129582  ,127728  ,                ,                ,
Interval=1HOUR
Uniform Lateral Inflow Hydrograph= 72
       0       6      21      32      48      58      69      83     101     133
     173     195     213     238     648     551     557     360     228     174
     134     108      88      74      56      40      27      20      15       9
       5       3       2       1       1       0       0       0       0       0
       0       0       0       0       0       0       0       0       0       0
       0       0       0       0       0       0       0       0       0       0
       0       0       0       0       0       0       0       0       0       0
       0       0
Use DSS=False
CWMS InputPosition= 0
Use Fixed Start Time=False
Is Critical Boundary=False
Boundary Location=SJR Stage III   ,4               ,114894  ,112783  ,                ,                ,
Interval=1HOUR
Uniform Lateral Inflow Hydrograph= 72
       0       7      20      25      32      40      49      62      70      94
     122     135     145     156     387     283     243     143      75      49
      35      29      25      23      20      13       5       2       1       0
       0       0       0       0       0       0       0       0       0       0
       0       0       0       0       0       0       0       0       0       0
       0       0       0       0       0       0       0       0       0       0
       0       0       0       0       0       0       0       0       0       0
       0       0
Use DSS=False
CWMS InputPosition= 0
Use Fixed Start Time=False
Is Critical Boundary=False
Boundary Location=SJR Stage III   ,4               ,102829  ,102329  ,                ,                ,
Interval=1HOUR
Uniform Lateral Inflow Hydrograph= 72
       0       3      15      29      43      60      76      93     111     140
     181     222     249     268     438     616     599     494     325     220
     169     135     113      98      87      74      56      39      28      21
      15      11       9       7       6       5       3       2       1       1
       0       0       0       0       0       0       0       0       0       0
       0       0       0       0       0       0       0       0       0       0
       0       0       0       0       0       0       0       0       0       0
       0       0
Use DSS=False
CWMS InputPosition= 0
Use Fixed Start Time=False
Is Critical Boundary=False
Boundary Location=SJR Stage III   ,4               ,82828   ,79328   ,                ,                ,
Interval=1HOUR
Uniform Lateral Inflow Hydrograph= 72
       0      10      85     155     203     261     340     405     483     600
     767     947    1022    1211    2936    4406    4760    3964    2370    1397
    1015     763     594     492     400     318     229     163     138     128
     121     116     113     110     108     107     105     105     104     103
     102     102     101     100      99      99      98      96      93      82
      63      44      28      19       3       0       0       0       0       0
       0       0       0       0       0       0       0       0       0       0
       0       0
Use DSS=False
CWMS InputPosition= 0
Use Fixed Start Time=False
Is Critical Boundary=False
Boundary Location=SJR Stage III   ,4               ,79328   ,78328   ,                ,                ,
Interval=1HOUR
Uniform Lateral Inflow Hydrograph= 72
       0       1       8       9      13      15      18      21      27      33
      44      52      53      67     216     230     229     130      50      27
      16      11      10       8       6       5       1       1       0       0
       0       0       0       0       0       0       0       0       0       0
       0       0       0       0       0       0       0       0       0       0
       0       0       0       0       0       0       0       0       0       0
       0       0       0       0       0       0       0       0       0       0
       0       0
Use DSS=False
CWMS InputPosition= 0
Use Fixed Start Time=False
Is Critical Boundary=False
Boundary Location=SJR Stage III   ,4               ,69317   ,67817   ,                ,                ,
Interval=1HOUR
Uniform Lateral Inflow Hydrograph= 72
       0       4      33      53      70      86     105     124     157     197
     252     308     329     393    1036    1376    1414    1034     544     313
     215     156     123      90      63      41      20      10       6       3
       2       1       1       0       0       0       0       0       0       0
       0       0       0       0       0       0       0       0       0       0
       0       0       0       0       0       0       0       0       0       0
       0       0       0       0       0       0       0       0       0       0
       0       0
Use DSS=False
CWMS InputPosition= 0
Use Fixed Start Time=False
Is Critical Boundary=False

--- R3.u04 (unsteady flow) ---

Flow Title=Unsteady Flow 04
Program Version=4.10
Use Restart= 0

--- R3.u05 (unsteady flow) ---

Flow Title=SJR 100 Year Inflow Hydrogaphs
Program Version=4.10
Use Restart= 0
Initial Flow Loc=SJR Stage III   ,4               ,135810  ,400
Boundary Location=SJR Stage III   ,4               ,53850   ,        ,                ,                ,
Friction Slope=0.002
Boundary Location=SJR Stage III   ,4               ,136855  ,        ,                ,                ,
Interval=1HOUR
Flow Hydrograph= 72
       0      79     210     438     781    1230    1670    2159    2677    3372
    5700    9621   15849   24967   35608   45547   55741   61834   62068   55103
   43960   32865   25256   20671   17601   15222   13270   11611   10192    8986
    7983    7122    6382    5789    5307    4926    4587    4273    4002    3756
    3508    3273    3055    2834    2600    2368    2168    2014    1883    1750
    1602    1469    1365    1243    1080     906     752     649     600     575
     558     550     544     538     531     516     484     440     394     334
     250     156
Flow Hydrograph QMin= 400
Use DSS=False
CWMS InputPosition= 0
Use Fixed Start Time=False
Fixed Start Date/Time=23SEP2008,10:00
Is Critical Boundary=False
Boundary Location=SJR Stage III   ,4               ,135254  ,132446  ,                ,                ,
Interval=1HOUR
Uniform Lateral Inflow Hydrograph= 72
       0      15      34      44      74      89     106     133     156     201
     347     491     665    1105    2119    2178    2196    1464     868     596
     452     363     299     246     200     143      99      71      55      38
      23      11       5       3       2       1       1       1       0       0
       0       0       0       0       0       0       0       0       0       0
       0       0       0       0       0       0       0       0       0       0
       0       0       0       0       0       0       0       0       0       0
       0       0
Use DSS=False
CWMS InputPosition= 0
Use Fixed Start Time=False
Is Critical Boundary=False
Boundary Location=SJR Stage III   ,4               ,129582  ,127728  ,                ,                ,
Interval=1HOUR
Uniform Lateral Inflow Hydrograph= 72
       0      12      30      38      67      88     110     128     163     211
     278     409     516     840    1972    1981    2063    1389     802     547
     410     328     269     220     174     126      84      62      46      29
      17       7       4       2       2       1       1       1       0       0
       0       0       0       0       0       0       0       0       0       0
       0       0       0       0       0       0       0       0       0       0
       0       0       0       0       0       0       0       0       0       0
       0       0
Use DSS=False
CWMS InputPosition= 0
Use Fixed Start Time=False
Is Critical Boundary=False
Boundary Location=SJR Stage III   ,4               ,114894  ,112783  ,                ,                ,
Interval=1HOUR
Uniform Lateral Inflow Hydrograph= 72
       0      10      26      42      52      69      81      94     113     148
     193     227     239     517    1429    1294    1299     710     294     161
      92      55      37      31      30      20       7       3       1       1
       0       0       0       0       0       0       0       0       0       0
       0       0       0       0       0       0       0       0       0       0
       0       0       0       0       0       0       0       0       0       0
       0       0       0       0       0       0       0       0       0       0
       0       0
Use DSS=False
CWMS InputPosition= 0
Use Fixed Start Time=False
Is Critical Boundary=False
Boundary Location=SJR Stage III   ,4               ,102829  ,102329  ,                ,                ,
Interval=1HOUR
Uniform Lateral Inflow Hydrograph= 72
       0       4      25      51      73      91     110     139     172     216
     281     373     443     591    1380    2170    2306    2048    1322     792
     565     431     346     285     242     201     157     119      89      68
      45      32      24      20      18      16      13       8       4       1
       1       1       0       0       0       0       0       0       0       0
       0       0       0       0       0       0       0       0       0       0
       0       0       0       0       0       0       0       0       0       0
       0       0
Use DSS=False
CWMS InputPosition= 0
Use Fixed Start Time=False
Is Critical Boundary=False
Boundary Location=SJR Stage III   ,4               ,81828   ,79328   ,                ,                ,
Interval=1HOUR
Uniform Lateral Inflow Hydrograph= 72
       0      11     120     226     320     412     502     583     706     896
    1628    3473    4550    5353    9008   11850   12411   10805    6511    3517
    2479    1893    1480    1185     949     737     523     339     246     202
     167     153     146     141     137     133     131     129     128     126
     125     124     123     123     122     122     121     120     120     120
     119     119     118     118     118     117     117     117     116     116
     116     115     115     115     114     114     114     114     113     113
     113     113
Use DSS=False
CWMS InputPosition= 0
Use Fixed Start Time=False
Is Critical Boundary=False
Boundary Location=SJR Stage III   ,4               ,79328   ,78328   ,                ,                ,
Interval=1HOUR
Uniform Lateral Inflow Hydrograph= 72
       0       3      11      13      21      26      28      31      40      52
      83     183     204     272     611     652     641     429     147      69
      35      22      16      15      14      12       4       1       1       0
       0       0       0       0       0       0       0       0       0       0
       0       0       0       0       0       0       0       0       0       0
       0       0       0       0       0       0       0       0       0       0
       0       0       0       0       0       0       0       0       0       0
       0       0
Use DSS=False
CWMS InputPosition= 0
Use Fixed Start Time=False
Is Critical Boundary=False
Boundary Location=SJR Stage III   ,4               ,69317   ,68817   ,                ,                ,
Interval=1HOUR
Uniform Lateral Inflow Hydrograph= 72
       0      10      49      74     114     152     169     188     232     302
     457     930    1205    1539    3084    3905    3988    3175    1686     876
     569     391     286     201     149     103      46      21      12       8
       5       3       1       1       0       0       0       0       0       0
       0       0       0       0       0       0       0       0       0       0
       0       0       0       0       0       0       0       0       0       0
       0       0       0       0       0       0       0       0       0       0
       0       0
Use DSS=False
CWMS InputPosition= 0
Use Fixed Start Time=False
Is Critical Boundary=False

--- R3.g29 (geometry) ---

Geom Title=Phase 1
Program Version=5.03
BEGIN GEOM DESCRIPTION:
Phase 1 Improvements
jcc
7 Feb 2017
END GEOM DESCRIPTION:

River Reach=San Jacinto Rive,Reach 3
Reach XY= 30
6278019.500847132232804.372780886277326.145389572231965.21827851
6276912.415510052231701.12700199 6276715.57784632230876.99639316
6276461.071057022230454.678618576276574.470314092230286.19972234
6276681.389613622228995.433370776276924.38802164 2228525.6364486
 6276794.78887072228091.479292936275907.03468673 2227641.1222434
 6275602.48844842227373.127990286274742.957460322227192.02071842
6274339.115848662226951.481179246273468.645432162226900.69073673
6272801.336139292226039.908089856267397.556891182220053.84097189
6264878.000645292217622.123526486264112.280071922216976.74583633
6261745.76875793 2216169.93431046261292.79237433 2215958.0052821
6260912.782042882215625.33329541 6259919.08898012214126.10505769
6259858.453769192213658.001867156259551.80302887 2213268.1336659
6259245.152293712213137.037626716258857.564003922213145.01738562
6257704.962047682213454.114825416256906.996481772213068.57410069
6255656.634446122212225.852235756255367.383659642211762.88202876

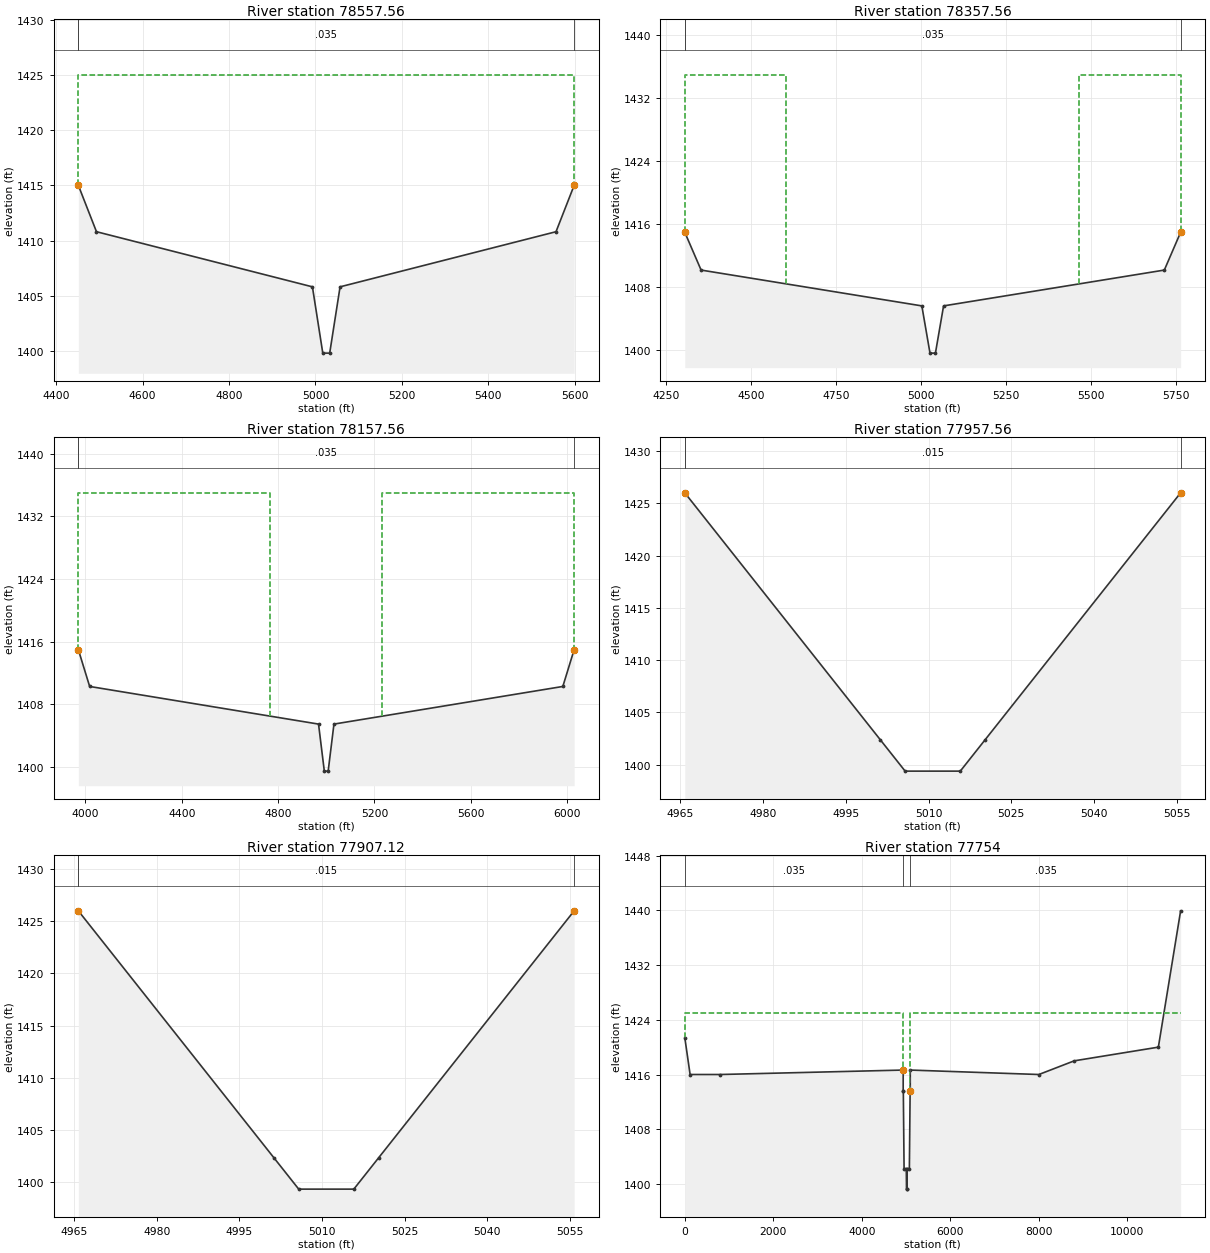
Type RM Length L Ch R = 1 ,78557.56,200,200,200
XS GIS Cut Line= 2
     6273972.351     2226603.809     6273074.936     2227319.936
#Sta/Elev= 8
    4451    1415    4493  1410.8    4993 1405.81    5017 1399.81    5033 1399.81
    5057 1405.81    5557  1410.8    5599    1415
#Mann= 3 , 0 , 0
    4451    .035       0    4451    .035       0    5599    .035       0
#XS Ineff= 2 , 0
      25    4393    1425    5657      25    1425
Permanent Ineff=
       F       F
Bank Sta=4451,5599
XS Rating Curve= 0 ,0
Exp/Cntr=0.3,0.1

Type RM Length L Ch R = 1 ,78357.56,200,200,200
XS GIS Cut Line= 2
     6273961.869     2226354.717     6272821.488     2227266.527
#Sta/Elev= 8
  4304.5    1415  4352.5  1410.2  5002.5 1405.65  5026.5 1399.65  5042.5 1399.65
  5066.5 1405.65  5716.5  1410.2  5764.5    1415
#Mann= 3 , 0 , 0
  4304.5    .035       0  4304.5    .035       0  5764.5    .035       0
#XS Ineff= 2 , 0
    34.5  4602.5    1435  5466.5    34.5    1435
Permanent Ineff=
       F       F
Bank Sta=4304.5,5764.5
XS Rating Curve= 0 ,0
Exp/Cntr=0.3,0.1

Type RM Length L Ch R = 1 ,78157.56,20,20,20
XS GIS Cut Line= 5
     6277186.039     2223497.061     6273359.222     2226584.527
     6273188.769     2226716.875     6269507.342     2229659.431
     6268619.748     2230609.156
#Sta/Elev= 8
    3971    1415    4018  1410.3    4968  1405.5    4992  1399.5    5008  1399.5
    5032  1405.5    5982  1410.3    6029    1415
#Mann= 3 , 0 , 0
    3971    .035       0    3971    .035       0    6029    .035       0
#XS Ineff= 2 , 0
       0    4768    1435    5232       0    1435
Permanent Ineff=
       F       F
Bank Sta=3971,6029
XS Rating Curve= 0 ,0
Exp/Cntr=0.3,0.1

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
Type RM Length L Ch R = 1 ,77957.56,16.79,16.79,16.79
XS GIS Cut Line= 5
     6277060.456     2223341.404      6273235.09     2226427.699
     6273064.998     2226559.768     6269371.132     2229512.266
     6268473.628     2230472.595
#Sta/Elev= 6
  4965.8    1426 5001.25 1402.37 5005.75 1399.37 5015.75 1399.37 5020.25 1402.37
  5055.7    1426
#Mann= 3 , 0 , 0
  4965.8    .035       0  4965.8    .015       0  5055.7    .035       0
Bank Sta=4965.8,5055.7
XS Rating Curve= 0 ,0
Exp/Cntr=0.3,0.1

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
Type RM Length L Ch R = 1 ,77907.12,19.15,19.15,19.15
XS GIS Cut Line= 5
     6277029.124     2223302.202     6273204.014     2226388.097
     6273033.743     2226520.298     6269337.257     2229475.702
     6268436.828     2230438.605
#Sta/Elev= 6
 4965.75    1426 5001.25 1402.34 5005.75 1399.34 5015.75 1399.34 5020.25 1402.34
 5055.74    1426
#Mann= 3 , 0 , 0
 4965.75    .015       0 4965.75    .015       0 5055.74    .015       0
Bank Sta=4965.75,5055.74
XS Rating Curve= 0 ,0
Exp/Cntr=0.3,0.1

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
Type RM Length L Ch R = 1 ,77754   ,91,91,91
XS GIS Cut Line= 3
      6276933.12      2223182.61      6269232.93      2229362.99
      6268324.96      2230333.97
#Sta/Elev= 19
       01421.389     120    1416     800    1416 4934.46 1416.65 4934.46 1413.65
 4937.46 1413.65 4954.58 1402.24 5004.46 1402.24 5009.46 1399.24 5019.46 1399.24
 5023.96 1402.24 5074.34 1402.24 5091.46 1413.65 5094.46 1413.65 5094.46 1416.65
    8000    1416    8800    1418   10700    142011203.071439.933
#Mann= 3 , 0 , 0
       0    .035       0 4934.46    .015       0 5094.46    .035       0
#XS Ineff= 2 , 0
       0 4934.46    1425 5094.46       0    1425
Permanent Ineff=
       F       F
Bank Sta=4934.46,5094.46
XS Rating Curve= 0 ,0
Exp/Cntr=0.5,0.3

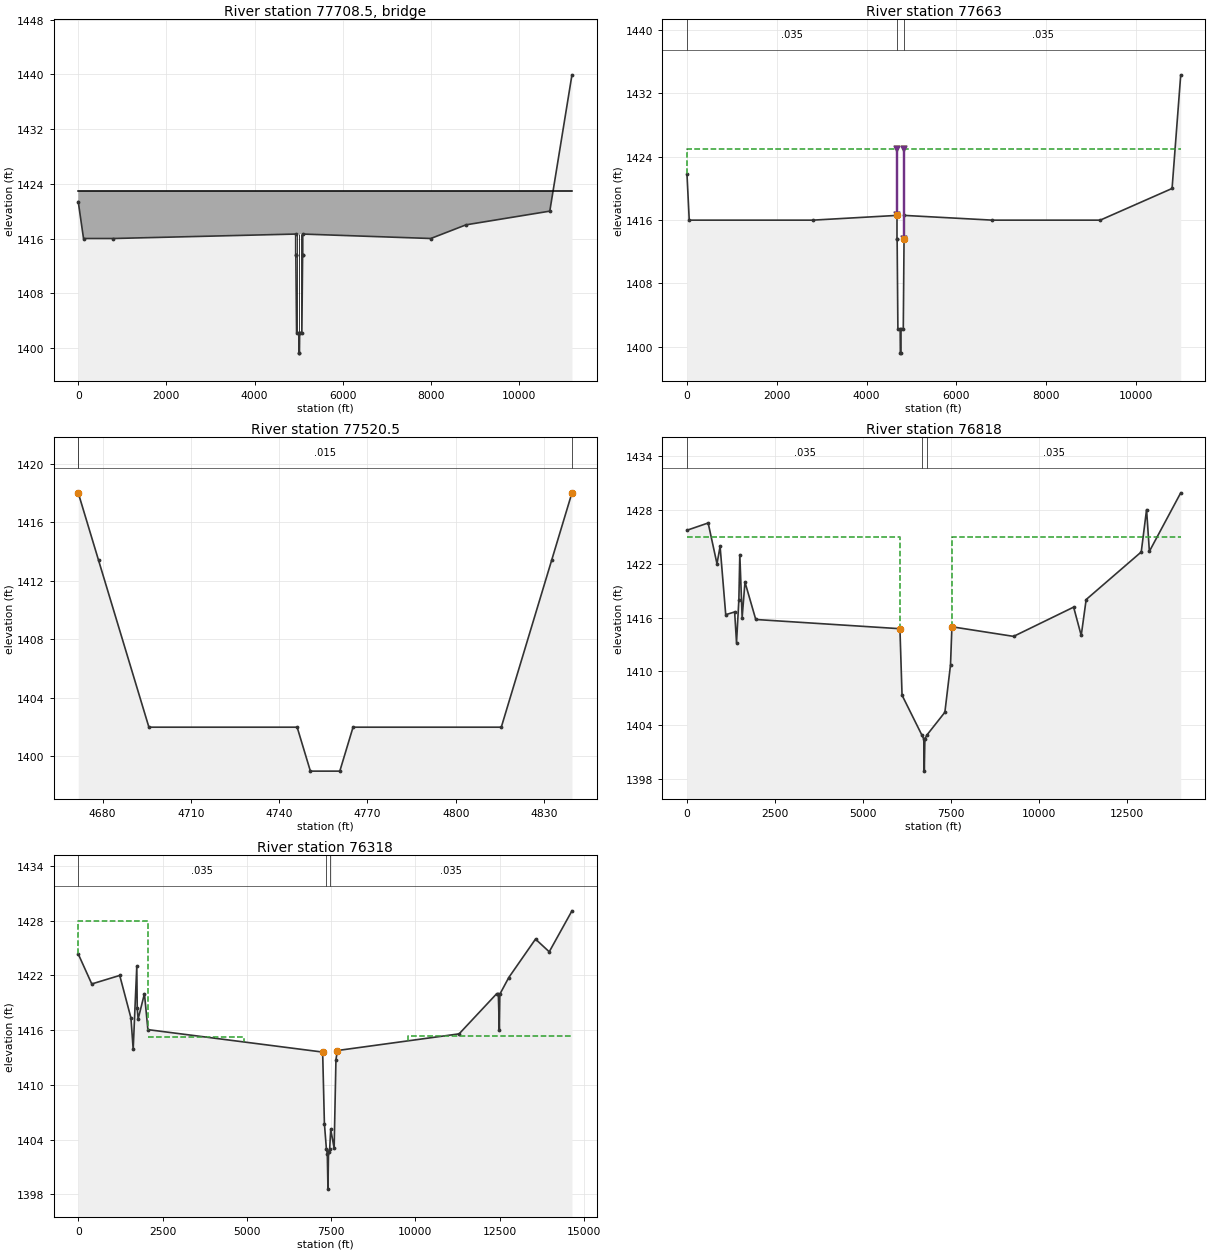
Type RM Length L Ch R = 3 ,77708.5 ,,,
BEGIN DESCRIPTION:
I-215 Freeway
END DESCRIPTION:
Bridge Culvert--1,0,-1,-1, 0
Deck Dist Width WeirC Skew NumUp NumDn MinLoCord MaxHiCord MaxSubmerge Is_Ogee
3,85,3,0, 4, 4, , , 0.98, 0, 7.5,7.5,,
       0 4934.46 5094.4611203.07
    1423    1423    1423    1423
    1410 1416.65 1416.65    1410
       0 4675.59 4835.5910992.76
    1423    1423    1423    1423
    1410  1416.6  1416.6    1410
Pier Skew, UpSta & Num, DnSta & Num=  ,4955, 2 ,4695, 2 , 0 , 0 , 0 ,,
       1       1
    1400 1416.65
       1       1
    1400 1416.65
Pier Skew, UpSta & Num, DnSta & Num=  ,5000, 2 ,4740, 2 , 0 , 0 , 0 ,,
       1       1
    1400    1425
       1       1
    1400    1425
Pier Skew, UpSta & Num, DnSta & Num=  ,5050, 2 ,4785, 2 , 0 , 0 , 0 ,,
       1       1
    1400    1425
       1       1
    1400    1425
BR Coef=-1 , 1 , 1 ,1.33, 0 ,,,0.8,0,1.2,0,
WSPro=,,,, 1 ,,,, 0 ,,,, 0 ,,,,-1 ,-1 ,-1 , 0 , 0 , 0 , 0 , 0
BC Design=,, 0 ,, 0 ,,,,,,
BC Use User HTab Curves=0
BC User HTab FreeFlow(D)= 0

Type RM Length L Ch R = 1 ,77663   ,142.5,142.5,142.5
XS GIS Cut Line= 6
       6276512.7       2223097.9      6275262.67      2224410.89
      6273048.68      2226198.88      6272902.67      2226316.89
      6269058.69       2229368.9      6268069.77       2230113.8
#Sta/Elev= 19
       0 1421.78      50    1416    2800    1416 4675.59  1416.6 4675.59  1413.6
 4678.59  1413.6 4695.71  1402.2 4746.09  1402.2 4750.59  1399.2 4760.59  1399.2
 4765.09  1402.2 4815.47  1402.2 4832.59  1413.6 4835.59  1413.6 4835.59  1416.6
    6800    1416    9200    1416   10800    142010992.761434.359
#Mann= 3 , 0 , 0
       0    .035       0 4675.59    .015       0 4835.59    .035       0
Levee=-1,4675.59,1425,-1,4835.59,1425,,
#XS Ineff= 2 , 0
       0 4675.59    1425 4835.59       0    1425
Permanent Ineff=
       F       F
Bank Sta=4675.59,4835.59
XS Rating Curve= 0 ,0
Exp/Cntr=0.5,0.3

Type RM Length L Ch R = 1 ,77520.5 ,702.5,702.5,702.5
XS GIS Cut Line= 6
     6276409.443     2222999.637      6275165.87     2224305.887
     6272959.121     2226088.031     6272813.078     2226206.065
     6268971.464     2229256.164     6267983.913     2230000.073
#Sta/Elev= 10
 4671.69    1418 4678.59  1413.4 4695.71    1402 4746.09    1402 4750.59    1399
 4760.59    1399 4765.09    1402 4815.47    1402 4832.59  1413.4 4839.49    1418
#Mann= 3 , 0 , 0
 4671.69    .035       0 4671.69    .015       0 4839.49    .035       0
Bank Sta=4671.69,4839.49
XS Rating Curve= 0 ,0
Exp/Cntr=0.3,0.1

Type RM Length L Ch R = 1 ,76818   ,500.841,500,500.043
XS GIS Cut Line= 6
    6277476.6081    2221151.8251    6272451.3577    2225592.4073
    6272437.5322    2225604.6244    6272413.0807    2225626.2309
    6267155.8005    2230271.8474    6267006.7539    2230403.5529
#Sta/Elev= 30
       01425.711 601.9011426.521 852.8181421.975 941.0941423.9141101.2321416.314
1354.783 1416.621408.1631413.1881474.887    14181501.577    14231568.301    1416
 1648.371419.9411955.3011415.7816053.6771414.7546114.0841407.3556683.397 1402.87
6732.7491402.4716746.0941398.9056763.4651402.509 6830.151402.9697331.5631405.457
7491.7011410.7277531.7351414.9699284.6851413.90110992.061417.15611208.03    1414
11348.36    141812914.541423.29513065.56 1428.0113145.761423.36214036.861429.876
#Mann= 3 ,-1 , 0
       0    .035       06683.397     .07       0 6830.15    .035       0
#XS Ineff= 2 , 0
       06053.677    14257531.735       0    1425
Permanent Ineff=
       F       F
Bank Sta=6053.677,7531.735
XS Rating Curve= 0 ,0
Exp/Cntr=0.3,0.1

Type RM Length L Ch R = 1 ,76318   ,500.841,500,500.043
XS GIS Cut Line= 6
      6277632.23    2220345.0092    6275110.5665    2222575.3457
    6273203.7003    2224260.3554    6272252.1557    2225101.1917
    6272086.0613    2225247.9615    6266746.3671    2229966.4034
#Sta/Elev= 30
       01424.358 401.6211421.0671230.733    14221563.0911417.3431629.8431413.906
1736.644    14231749.9951418.4121776.6951417.2191963.598    14202065.9441416.057
7248.7181413.5967300.5781405.764  7360.11402.9487386.3991402.4597406.2911398.568
7422.201 1402.667457.2451402.9947488.0621405.1187589.523 1403.057642.9031412.769
7686.3551413.767 11295.71415.59412409.931419.99712458.55    142012488.751416.043
12503.851419.94612767.321421.76413560.981425.98513968.351424.593 14642.31429.085
#Mann= 3 ,-1 , 0
       0    .035       0  7360.1     .07       07457.245    .035       0
#XS Ineff= 3 ,-1
       0    2074    1428    2074    4914  1415.3    9770   15000  1415.4
Permanent Ineff=
       T       T       T
Bank Sta=7248.718,7686.355
XS Rating Curve= 0 ,0
Exp/Cntr=0.3,0.1