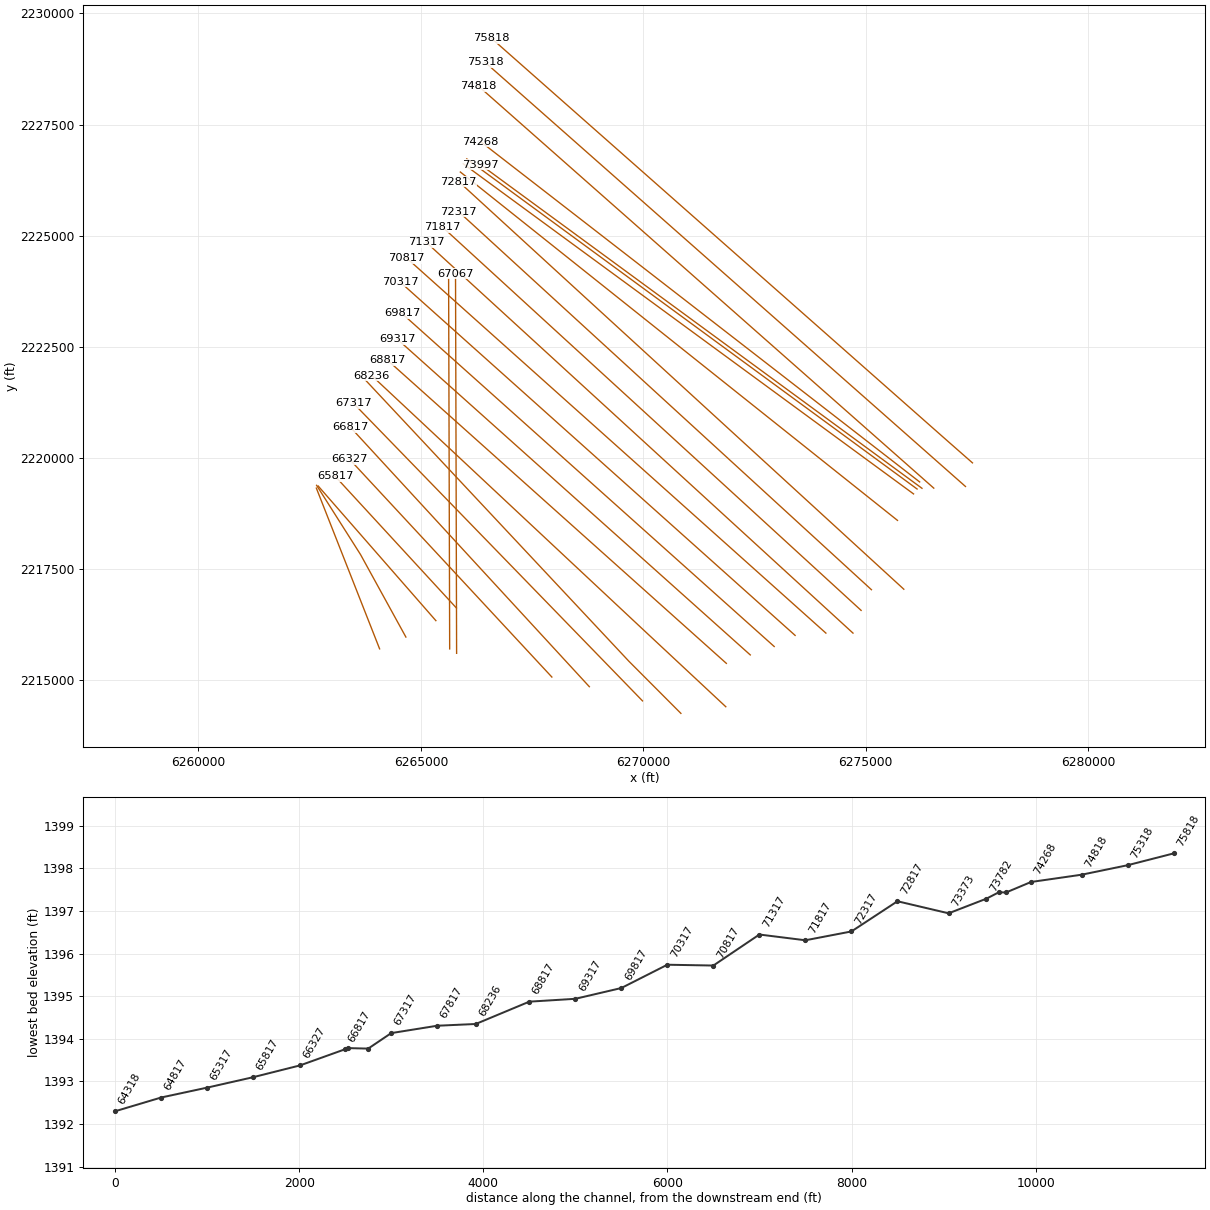
HEC-RAS study R3.prj: San Jacinto Stage III Reach 3

--- R3.g29 (geometry) --- (continued)

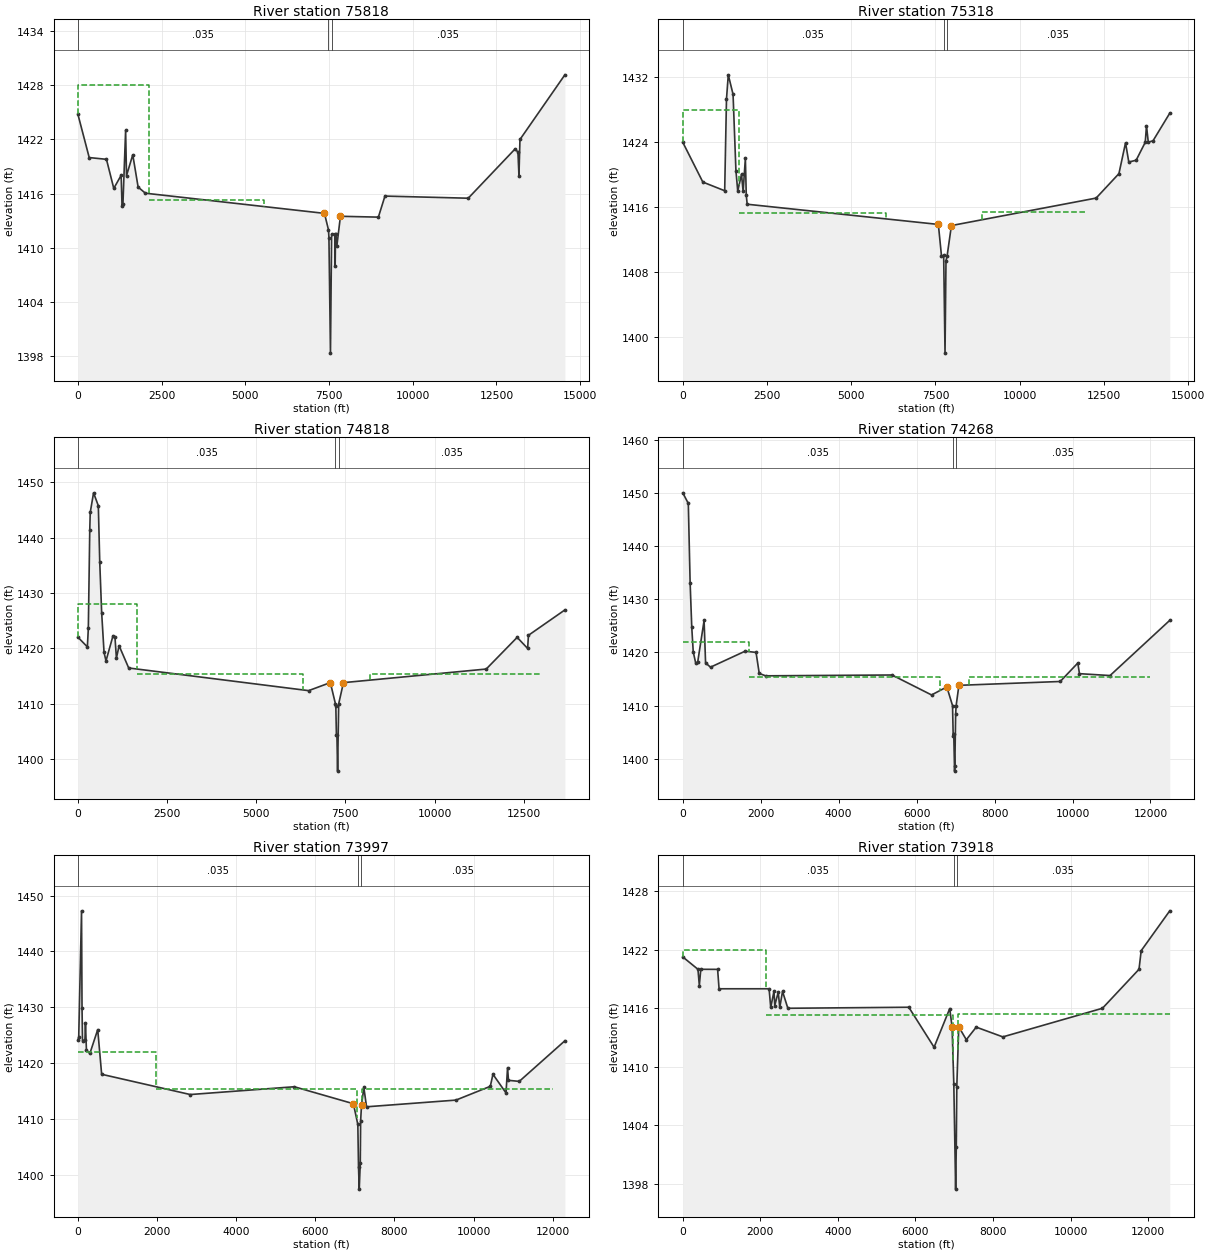
Type RM Length L Ch R = 1 ,75818   ,500.841,500,500.043
XS GIS Cut Line= 6
    6277400.9622    2219887.2207    6276802.7563    2220412.7941
    6268628.6081    2227635.9124    6267610.4083    2228535.6485
     6267584.743    2228558.3279    6266588.6342    2229438.5433
#Sta/Elev= 30
       01424.796 338.115    1420 853.0611419.8051071.8451416.5881291.8641418.036
1318.554 1414.631345.2441414.8441425.313    14231452.002    1418 1638.831420.308
1798.968 1416.732015.9051416.0547363.7611413.8227483.864    14127497.2091411.134
7543.1891398.3517577.2781411.5217672.6071411.5217683.3551407.9647694.1041411.521
7734.1381410.2277840.8961413.4998973.8781413.4069170.2021415.73611657.52  1415.5
13051.381420.93413141.991420.625 13172.2    1418 13202.4    142214543.691429.159
#Mann= 3 ,-1 , 0
       0    .035       07483.864     .07       07577.278    .035       0
#XS Ineff= 3 ,-1
       0    2135    1428    2135    5563  1415.3    9418   14000  1415.4
Permanent Ineff=
       T       T       T
Bank Sta=7363.761,7840.896
XS Rating Curve= 0 ,0
Exp/Cntr=0.3,0.1

Type RM Length L Ch R = 1 ,75318   ,500.841,500,500.043
XS GIS Cut Line= 6
6277243.476495732219356.10864324    6276196.6814    2220281.1131
    6275931.9347    2220515.0577    6275854.2341     2220583.718
    6275507.9727    2220889.6934    6266443.7792    2228899.3036
#Sta/Elev= 30
       01423.989 595.4321419.0991243.8461418.0321297.2251429.2981350.604 1432.28
1492.2581429.8821577.4661420.5011630.846    14181743.1751420.0491790.9841417.958
1857.708    14221884.3971417.4951911.0871416.3757584.9661413.893 7678.21    1410
7742.7771410.0917782.8121398.0747811.6711409.4387844.331    14107972.4471413.753
12266.981417.131 12943.81420.13513140.121423.92413236.261421.56313454.671421.781
 13725.11423.985 13761.61426.02413814.98    142413955.621424.17314452.351427.563
#Mann= 3 ,-1 , 0
       0    .035       07742.777     .07       07844.331    .035       0
#XS Ineff= 3 ,-1
       0    1670    1428    1670 6017.18  1415.3 8872.18   12000  1415.4
Permanent Ineff=
       T       T       T
Bank Sta=7584.966,7972.447
XS Rating Curve= 0 ,0
Exp/Cntr=0.3,0.1

Type RM Length L Ch R = 1 ,74818   ,270,550,790
XS GIS Cut Line= 2
     6276530.736     2219318.683      6266298.93     2228360.059
#Sta/Elev= 30
       01422.031 266.0161420.281 292.7061423.641  332.741441.297 346.0851444.547
 439.4991448.094 572.947 1445.76 612.9821435.544 666.3611426.467 733.0851419.301
 787.8691417.753 985.4911422.3051040.016    14221080.051 1418.26 1155.521420.482
1424.7321416.4716468.9271412.3817078.1981413.8367221.266    14107232.0171409.644
7248.2271404.3887262.3961404.3817281.6731397.8517312.085    14107445.5341413.825
11448.981416.281 12316.4    142212609.98    142012632.481422.37113654.171426.953
#Mann= 3 ,-1 , 0
       0    .035       07221.266     .07       07312.085    .035       0
#XS Ineff= 3 ,-1
       0    1670    1428    1670    6324  1415.3    8178   13000  1415.4
Permanent Ineff=
       T       T       T
Bank Sta=7078.198,7445.534
XS Rating Curve= 0 ,0
Exp/Cntr=0.3,0.1

Type RM Length L Ch R = 1 ,74268   ,122,271,370
XS GIS Cut Line= 2
     6276213.599     2219458.017     6266340.809     2227116.229
#Sta/Elev= 30
       01449.993 142.002    1448 188.5681433.089 230.5931424.726  268.561420.084
 331.839    1418 382.4631418.149 546.988    1426 584.9551418.024 711.5131417.219
1597.4191420.2191880.155    14201961.7331416.0512124.8891415.5945368.848 1415.75
6383.251    14126774.8251413.5086921.665    14106938.0861404.356 6952.341404.745
6973.722 1397.68 6980.851398.7227001.4461408.4727014.103    14107084.8211413.807
9684.4771414.53110135.83    141810178.05    141610962.711415.64612494.811426.023
#Mann= 3 ,-1 , 0
       0    .035       06921.665     .07       07014.103    .035       0
#XS Ineff= 3 ,-1
       0    1706    1422    1706 6593.72  1415.3 7353.72   12000  1415.4
Permanent Ineff=
       T       T       T
Bank Sta=6774.825,7084.821
XS Rating Curve= 0 ,0
Exp/Cntr=0.3,0.1

Type RM Length L Ch R = 1 ,73997   ,79,79,79
BEGIN DESCRIPTION:
Cut Upstream of BNSF Railroad
jcc  14 DEC 2009
END DESCRIPTION:
XS GIS Cut Line= 2
     6276265.564     2219315.089     6266341.885     2226595.725
#Sta/Elev= 30
       01424.109  21.0791424.641  91.9891447.273 104.3911429.949 116.794    1424
 178.0061424.162  191.211427.173 216.0151422.305 302.8341421.729 501.277    1426
 600.498    14182839.7651414.3735469.3111415.7686963.0661412.7297075.298 1409.01
7092.2031401.4747110.7171397.4347136.7031402.0427146.487 1409.717167.9491412.453
7227.4441415.6377295.0641412.1789555.2231413.37810423.411415.84410490.13    1418
10820.291414.65910859.431419.18910882.311416.91711155.171416.72912308.01    1424
#Mann= 3 ,-1 , 0
       0    .035       07075.298     .07       07146.487    .035       0
#XS Ineff= 3 ,-1
       0    1979    1422    1979  7042.8  1415.3  7181.2   12000  1415.4
Permanent Ineff=
       T       T       T
Bank Sta=6963.066,7167.949
XS Rating Curve= 0 ,0
Exp/Cntr=0.5,0.3

Type RM Length L Ch R = 1 ,73918   ,136,136,136
BEGIN DESCRIPTION:
Copy of Section 73782
Upstream of Case Road Bridge and Downstream of BNSF Bridge
jcc  14 DEC 2009
END DESCRIPTION:
XS GIS Cut Line= 2
     6276155.702     2219298.933     6266032.209     2226726.123
#Sta/Elev= 30
       01421.269 391.276    1420 427.0311418.335 464.239    1420 898.3741419.992
 935.539    14182225.414    14182267.7511416.0812352.2781417.7692372.103 1416.28
2461.0641417.6652500.8751416.0852572.0451417.7292709.117    14165827.4981416.105
 6479.52    14126882.8691415.9696943.5261414.0826988.0281408.2347035.0151397.438
 7051.921401.7337065.1451407.9497115.2231414.0997310.4971412.7717565.9271414.064
8252.1881413.06210821.011416.00111763.05    142011819.181421.90812555.81    1426
#Mann= 3 ,-1 , 0
       0    .035       06988.028     .07       07065.145    .035       0
#XS Ineff= 3 ,-1
       0    2143    1422    2143    6972  1415.3    7096   14000  1415.4
Permanent Ineff=
       T       T       T
Bank Sta=6943.526,7115.223
XS Rating Curve= 0 ,0
Exp/Cntr=0.5,0.3

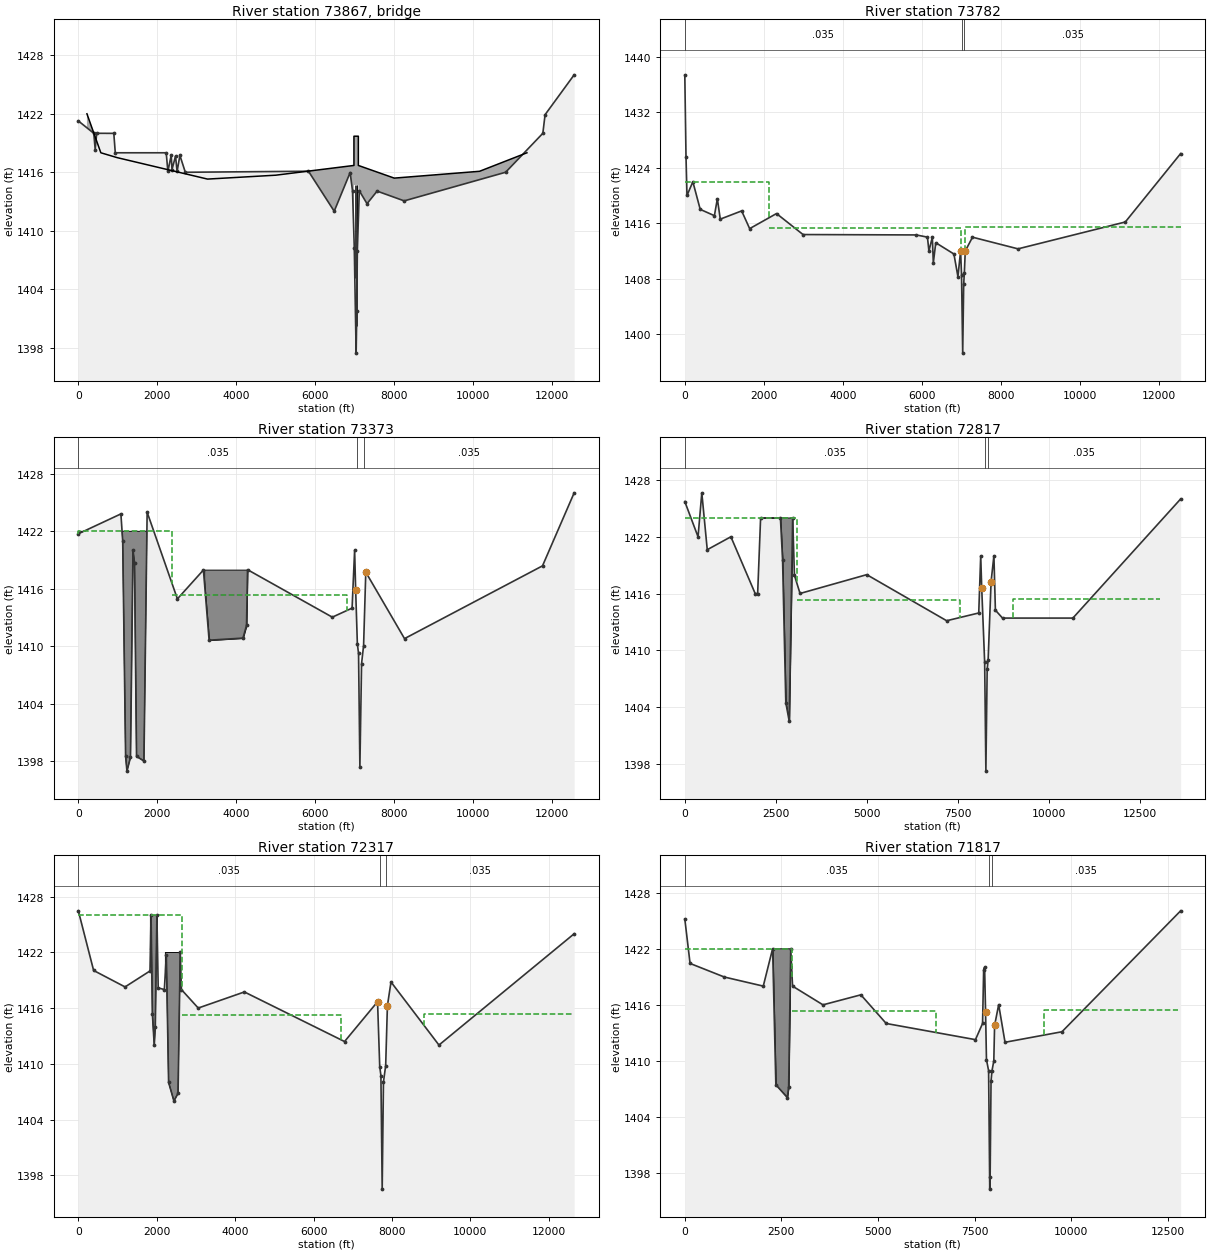
Type RM Length L Ch R = 3 ,73867   ,,,
BEGIN DESCRIPTION:
Case Road Bridge
This is based on field topo.  The sections are projected to the upstream and downstream sections.
jcc 6 August 2009
END DESCRIPTION:
Bridge Culvert--1,0,-1,-1, 0
Deck Dist Width WeirC Skew NumUp NumDn MinLoCord MaxHiCord MaxSubmerge Is_Ogee
59,23,3,0, 12, 12, 1415.3, , 0.98, 0, 5,5,,
     218     570     985    3272    5000  6979.1 6979.11  7090.8 7090.81    8000
   10160   11360
    1422    1418  1417.5  1415.3  1415.7  1416.7  1419.7  1419.7  1416.7  1415.4
  1416.1    1418
                                                  1414.7  1414.7
                
     218     570     985    3272    5000 6991.28 6991.28 7102.98 7102.98    8000
   10160   11360
    1422    1418  1417.5  1415.3  1415.7  1416.7  1419.7  1419.7  1416.7  1415.4
  1416.1    1418
                                                  1414.7  1414.7
                
Pier Skew, UpSta & Num, DnSta & Num=  ,7001.34, 2 ,7013.52, 2 , 0 , 0 , 0 ,,
    1.17    1.17
    1380    1420
    1.17    1.17
    1380    1420
Pier Skew, UpSta & Num, DnSta & Num=  ,7023.58, 2 ,7035.76, 2 , 0 , 0 , 0 ,,
    1.17    1.17
    1380    1420
    1.17    1.17
    1380    1420
Pier Skew, UpSta & Num, DnSta & Num=  ,7045.82, 2 ,7058, 2 , 0 , 0 , 0 ,,
    1.17    1.17
    1380    1420
    1.17    1.17
    1380    1420
Pier Skew, UpSta & Num, DnSta & Num=  ,7068.06, 2 ,7080.24, 2 , 0 , 0 , 0 ,,
    1.17    1.17
    1380    1420
    1.17    1.17
    1380    1420
BR Coef=-1 , 1 , 0 ,, 0 ,,,0.8,-1,2,0,
WSPro=,,,, 1 ,,,, 0 ,,,, 0 ,,,,-1 ,-1 ,-1 , 0 , 0 , 0 , 0 , 0
BC Design=,, 0 ,, 0 ,,,,,,
BC Use User HTab Curves=0
BC User HTab FreeFlow(D)= 0

Type RM Length L Ch R = 1 ,73782   ,618,409,265
BEGIN DESCRIPTION:
Cut Downstream of Case Road
END DESCRIPTION:
XS GIS Cut Line= 2
     6276076.022     2219188.714     6265951.617     2226616.616
#Sta/Elev= 30
       01437.383  30.5431425.602  55.349    1420 204.1811421.975 390.221    1418
 749.898 1417.09 824.3141419.527  898.731416.5931439.7621417.7771642.6241415.223
2322.4091417.3962994.7811414.3715859.7971414.3156145.058    14146182.2661411.998
6269.085    1414 6293.89 1410.296355.9031413.1936815.5921411.5676917.0231408.308
6984.644    14127008.2951408.575 7038.051397.2877062.8551407.1837079.835 1408.89
7102.979    14127286.104 1413.99  8439.1 1412.3111155.741416.18112556.961426.038
#Mann= 3 ,-1 , 0
       0    .035       07008.295     .07       07079.835    .035       0
#XS Ineff= 3 ,-1
       0    2143    1422    2143 6984.18  1415.3 7108.18   14000  1415.4
Permanent Ineff=
       T       F       F
Bank Sta=6984.644,7102.979
XS Rating Curve= 0 ,0
Exp/Cntr=0.5,0.3

Type RM Length L Ch R = 1 ,73373   ,900,556,295
XS GIS Cut Line= 2
     6275715.067     2218593.054     6265887.981     2226430.734
#Sta/Elev= 30
       01421.7421079.1411423.8191125.0051420.9821198.549  1398.51232.6331396.945
 1322.171398.3761386.125    14201424.4991418.7081475.6631398.4861663.642    1398
1744.274    14242511.7351414.9413171.1861417.9583315.5261410.6254174.5661410.844
4264.1041412.1794289.6861417.9926438.5761413.0316940.0461413.9757004.197    1420
7031.0931415.8257073.7881410.2267103.7081409.253 7137.831397.3697180.5241408.182
7231.6191410.0687287.2611417.7328269.2371410.789 11767.41418.39212569.841426.022
#Mann= 3 ,-1 , 0
       0    .035       07073.788     .07       07231.619    .035       0
#XS Ineff= 3 ,-1
       0    2382    1422    2382    6806  1415.3    7537   12000  1415.4
Permanent Ineff=
       T       F       F
#Block Obstruct= 3 ,-1
       0 1817.49    1422 3190.38 4294.24    1418
Bank Sta=7031.093,7287.261
XS Rating Curve= 0 ,0
Exp/Cntr=0.3,0.1

Type RM Length L Ch R = 1 ,72817   ,500.397,500,500.121
XS GIS Cut Line= 6
    6275857.4419    2217044.5198    6273400.7516    2219296.0591
    6269761.1881    2222631.5016    6269754.4644    2222637.6633
    6269661.5136    2222722.84736265848.183051432226217.53663142
#Sta/Elev= 30
       01425.725 363.893    1422 467.4961426.646  617.121420.634 1266.72    1422
 1934.331416.0012002.184    14162083.572    14242628.362    14242687.5641419.516
2776.3661404.4562870.313  1402.52965.265    14243013.1741417.933 3167.541416.007
 5000.941417.996 7197.291413.125 8078.961413.9468133.2171419.9848160.3451416.627
 8241.731408.7168275.2811397.228 8310.671408.0168336.6791408.9298418.0641417.261
8495.992    14208536.6851414.2428732.7141413.40610666.261413.406 13627.61425.996
#Mann= 3 ,-1 , 0
       0    .035       0 8241.73     .07       08336.679    .035       0
#XS Ineff= 3 ,-1
       0    3079    1424    3079    7555  1415.3    902313056.47  1415.4
Permanent Ineff=
       T       F       F
#Block Obstruct= 2 ,-1
 2146.26  2479.3 1424.04 2627.31 2960.35 1424.04
Bank Sta=8160.345,8418.064
XS Rating Curve= 0 ,0
Exp/Cntr=0.3,0.1

Type RM Length L Ch R = 1 ,72317   ,500.397,500,500.121
XS GIS Cut Line= 6
    6275128.8969    2217034.1096    6269419.8493    2222266.1105
    6269310.9003    2222365.9556    6266817.9029    2224650.6387
    6266528.6258     2224915.744     6265849.151    2225538.4419
#Sta/Elev= 30
       01426.473 389.9711420.0541191.7421418.2831827.771    1420  1854.91426.019
1889.0061415.3871936.285    14121963.4131414.0072004.105    14262037.0151418.179
2194.004    14182244.2281421.7362302.517    1408 2438.371406.0012543.5991406.832
2599.449    14222629.052    14183058.2781416.0094235.1891417.7426790.2711412.404
7631.761 1416.697687.4861409.702 7717.461408.7457750.1681396.5197782.4351408.045
7838.9741409.8187883.3761416.2667974.8531418.8149198.0641412.026 12646.41424.004
#Mann= 3 ,-1 , 0
       0    .035       07687.486     .07       07838.974    .035       0
#XS Ineff= 3 ,-1
       0    2637    1426    2637    6692  1415.3    882612587.19  1415.4
Permanent Ineff=
       T       F       F
#Block Obstruct= 2 ,-1
 1837.89 2010.57 1425.99 2220.26 2602.64 1421.99
Bank Sta=7631.761,7883.376
XS Rating Curve= 0 ,0
Exp/Cntr=0.3,0.1

Type RM Length L Ch R = 1 ,71817   ,500.397,500.004,500.121
BEGIN DESCRIPTION:
Blocked obstruction is EMWD WWTP.
jcc  20 AUG 2009
END DESCRIPTION:
XS GIS Cut Line= 6
     6274897.156    2216568.2786     6268837.788    2222121.3272
     6266479.211    2224282.8219    6265509.8915    2225171.1454
    6265500.7718    2225179.5029    6265487.3615    2225191.7927
#Sta/Elev= 30
       01425.185 136.3271420.4231024.382 1418.972030.844    14182273.027    1422
2356.4641407.4592652.483  1406.12688.0491407.2362741.288    14222788.465    1418
 3575.97    14164556.585 1417.075213.0411414.0087522.3541412.281  7706.21414.007
7734.5111419.7367758.798    14207784.0551415.2537807.2021410.1577862.4051408.964
7892.0071396.3127902.1511397.6117925.6111407.864 7951.211408.983  7997.1 1410.01
8017.6221413.7988123.2981416.0238287.502    14129761.1011413.12512832.071426.044
#Mann= 3 ,-1 , 0
       0    .035       07862.405     .07       0 7951.21    .035       0
#XS Ineff= 4 ,-1
       0    2777    1422    2777    6503  1415.3    930312763.59  1415.4
Permanent Ineff=
       T       F       F       F
#Block Obstruct= 1 ,-1
  2269.6 2725.99 1422.04
Bank Sta=7784.055,8017.622
XS Rating Curve= 0 ,0
Exp/Cntr=0.3,0.1

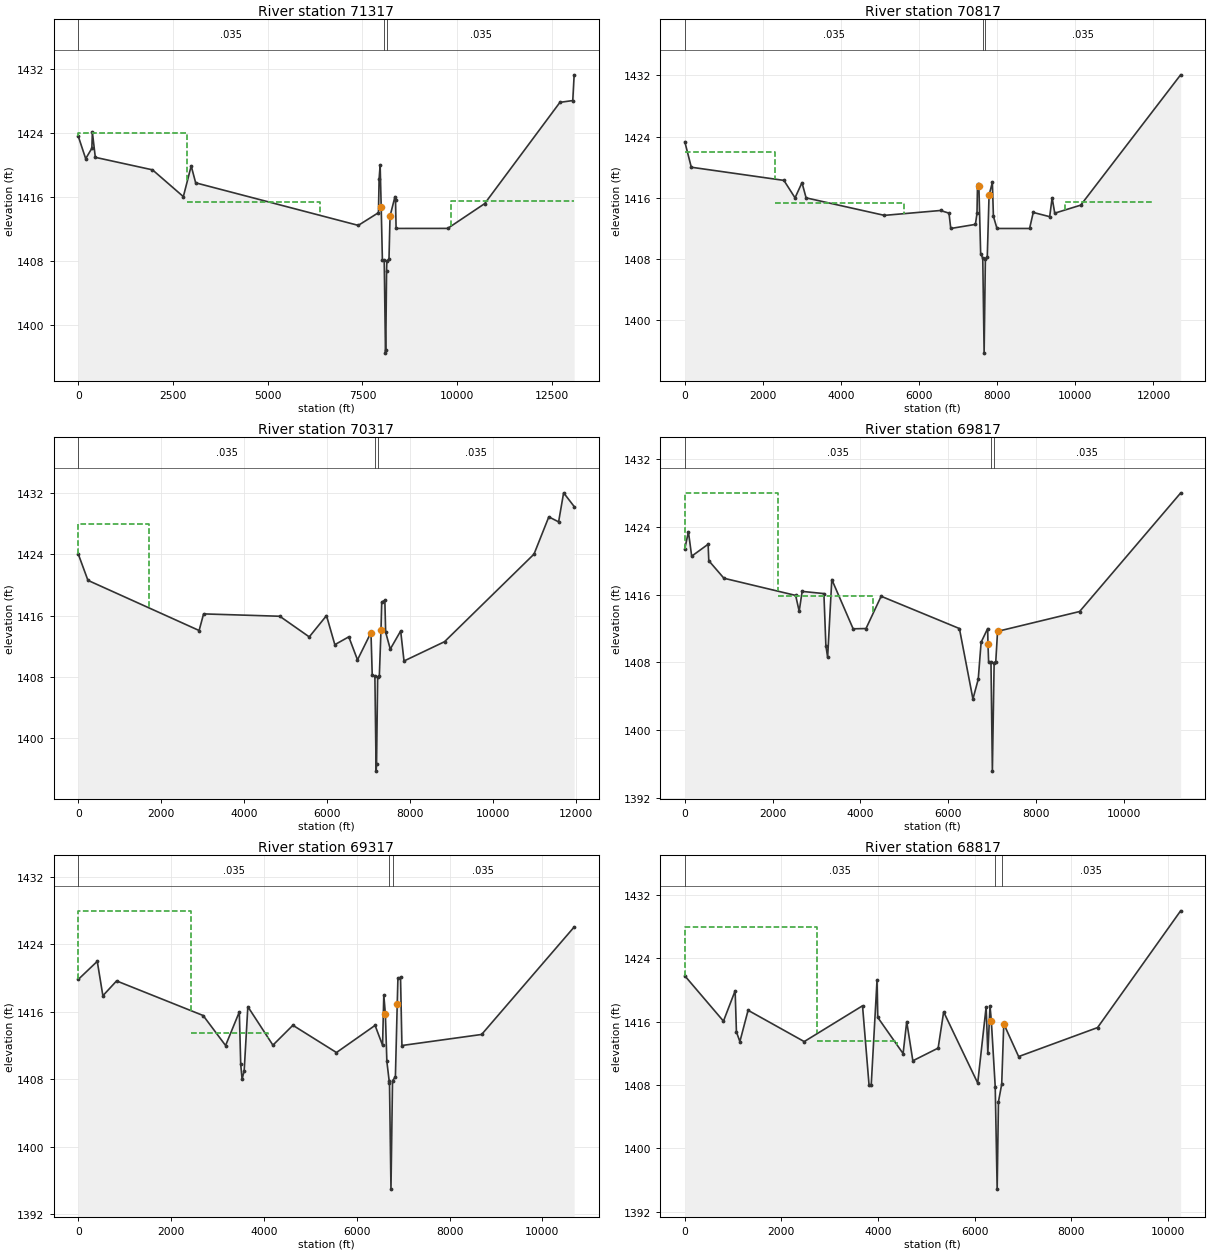
Type RM Length L Ch R = 1 ,71317   ,495.606,499.985,508.776
XS GIS Cut Line= 6
    6274714.5628    2216057.4067    6274442.6697    2216306.5805
    6274417.9132    2216329.2682    6269825.6327    2220537.8189
    6269666.6179    2220683.5463    6265124.4031    2224846.2147
#Sta/Elev= 30
       01423.522 194.1941420.735 356.9641422.039 370.5281424.041 448.4371420.906
1957.8191419.3432772.181    14162979.3931419.8343097.3431417.7217390.0661412.406
7922.8991413.9937939.3261418.1627967.3021419.932 7995.171414.6668026.5051408.107
8074.9671408.0318108.4151396.447 8115.661396.8628136.7271406.7398144.913    1408
8200.4271408.1448228.7371413.5678358.967    14168372.9751415.591 8388.261412.025
9749.9441412.028 10726.81415.12512713.061427.77513052.16    142813088.781431.214
#Mann= 3 ,-1 , 0
       0    .035       08074.967     .07       08144.913    .035       0
#XS Ineff= 3 ,-1
       0    2862    1424    2862    6379  1415.3    9847   14000  1415.4
Permanent Ineff=
       T       F       F
Bank Sta=7995.17,8228.737
XS Rating Curve= 0 ,0
Exp/Cntr=0.3,0.1

Type RM Length L Ch R = 1 ,70817   ,500.661,500.005,500.027
XS GIS Cut Line= 6
    6274105.4658    2216057.4067    6273559.9997    2216545.8269
    6271992.4237    2217949.4632    6271991.0083    2217950.7307
    6271758.6536    2218158.7852    6264680.1111     2224497.042
#Sta/Elev= 30
       0 1423.33  166.54    14202537.9071418.2812822.732    14163000.6041417.986
 3106.18    14165110.9871413.7136548.5971414.3516765.307    14146810.279    1412
7441.8151412.5357482.0841413.9817495.507 1417.81 7530.271417.5367576.0451408.688
7629.7371408.1157664.7531395.7197696.8531408.0587745.4251408.3047790.813 1416.32
7875.6871418.0287902.5331413.5917994.183    14128828.722    14128922.6831414.096
9343.3541413.5429405.911    14169473.026    141410137.861415.04812696.27 1432.07
#Mann= 3 ,-1 , 0
       0    .035       07629.737     .07       07696.853    .035       0
#XS Ineff= 3 ,-1
       0    2304    1422    2304    5613  1415.3    9748   12000  1415.4
Permanent Ineff=
       T       F       F
Bank Sta=7530.27,7790.813
XS Rating Curve= 0 ,0
Exp/Cntr=0.3,0.1

Type RM Length L Ch R = 1 ,70317   ,500.661,500,500.027
XS GIS Cut Line= 6
    6273413.7322    2216005.6467    6269080.6305    2219885.5853
    6268048.6346    2220809.6535    6268046.1537    2220811.8748
    6265310.5989    2223261.3407    6264531.8918    2223958.6094
#Sta/Elev= 30
       0    1424 231.9661420.5952915.3151414.0613023.3151416.2254862.2691415.918
5573.6881413.2295989.802    14166191.1471412.2166528.0931413.2376737.9641410.235
7063.6441413.7967093.9161408.2037157.6521408.1537187.6871395.7387197.8741396.638
 7224.721407.9827264.9891408.108 7305.151414.0967322.6041417.7577397.959    1418
7417.7471413.8347528.9141411.6387780.168    14147860.7061410.0878838.9281412.603
10998.881424.01611355.521428.866 11592.31428.21811713.11    143211967.481430.217
#Mann= 3 ,-1 , 0
       0    .035       07157.652     .07       0 7224.72    .035       0
#XS Ineff= 1 ,-1
       0    1706    1428
Permanent Ineff=
       T
Bank Sta=7063.644,7305.15
XS Rating Curve= 0 ,0
Exp/Cntr=0.3,0.1

Type RM Length L Ch R = 1 ,69817   ,500.661,500.002,500.027
XS GIS Cut Line= 6
    6272943.2486    2215755.7755    6270994.7448    2217500.5014
    6270193.8444    2218217.6423    6270085.1804    2218314.9422
    6269209.1478    2219099.3577    6264575.4207    2223248.4819
#Sta/Elev= 30
       01421.401  82.4771423.413 156.8191420.531 531.5891421.938 546.579    1420
 891.3671417.9312526.0141415.9062606.5521414.0392674.4251416.3793169.9661416.122
3214.938    14103255.1341408.5973349.8551417.781 3836.391411.9694129.375    1412
4474.1631415.8066258.066    14126566.3431403.693 6687.151406.0246752.7611410.385
6901.918    14126909.3551410.1816923.5191408.0616977.623    14087009.3021395.191
7049.5711407.994 7086.611408.0897127.5311411.6688997.1711414.00711299.281427.979
#Mann= 3 ,-1 , 0
       0    .035       06977.623     .07       07049.571    .035       0
#XS Ineff= 2 ,-1
       0    2113    1428    2113    4298 1415.85
Permanent Ineff=
       T       F
Bank Sta=6909.355,7127.531
XS Rating Curve= 0 ,0
Exp/Cntr=0.3,0.1

Type RM Length L Ch R = 1 ,69317   ,500.661,500,500.027
XS GIS Cut Line= 6
    6272405.3835    2215566.2388    6270968.3818    2216852.9566
    6270895.7975    2216917.9498    6267536.6199    2219925.8191
    6267261.3017    2220172.3439    6264476.1754    2222666.1971
#Sta/Elev= 30
       01419.858 408.043    1422 528.8511417.911 824.1571419.6742689.5661415.563
3173.185    14123469.0861415.9883499.0681409.771 3529.05    14083574.0221409.018
  3652.91416.6154193.3341412.0414623.3761414.4055562.4821411.1676394.709 1414.39
6555.7861412.0286582.631    1418 6616.211415.7556648.511 1410.116698.0841407.793
6705.1661407.5566737.0761394.9386770.5541407.7966832.639 1408.316871.9931416.913
6886.9841420.021 6943.131420.0816973.112    14128690.9321413.31310684.551426.078
#Mann= 3 ,-1 , 0
       0    .035       06698.084     .07       06770.554    .035       0
#XS Ineff= 2 ,-1
       0    2429    1428    2429    4087  1413.5
Permanent Ineff=
       T       T
Bank Sta=6616.21,6871.993
XS Rating Curve= 0 ,0
Exp/Cntr=0.3,0.1

Type RM Length L Ch R = 1 ,68817   ,587.366,581.311,564.226
XS GIS Cut Line= 6
    6271867.5185    2215376.7022    6268446.0672    2218440.3323
     6267313.766    2219454.2157    6267027.5635    2219710.4865
    6266914.9734    2219811.3019    6264250.8034    2222196.8485
#Sta/Elev= 30
       01421.783 800.0331416.0631041.7911419.8911068.6371414.7021140.0361413.483
 1309.721417.4322471.4191413.4843678.263    1418 3813.18    14083858.152    1408
3978.0781421.2033993.0691416.5394518.066 1411.97 4592.62    14164719.6981411.061
5243.1951412.663 5357.231417.226    60621408.2546236.4991417.8596271.667    1412
 6316.641417.9996343.8831416.0926424.4211407.805 6464.691394.8716491.5361405.896
 6558.631408.1066601.4641415.7196908.9581411.5948542.7931415.25110261.591429.979
#Mann= 3 ,-1 , 0
       0    .035       06424.421     .07       0 6558.63    .035       0
#XS Ineff= 2 ,-1
       0    2745    1428    2745    4392  1413.5
Permanent Ineff=
       T       T
Bank Sta=6343.883,6601.464
XS Rating Curve= 0 ,0
Exp/Cntr=0.3,0.1

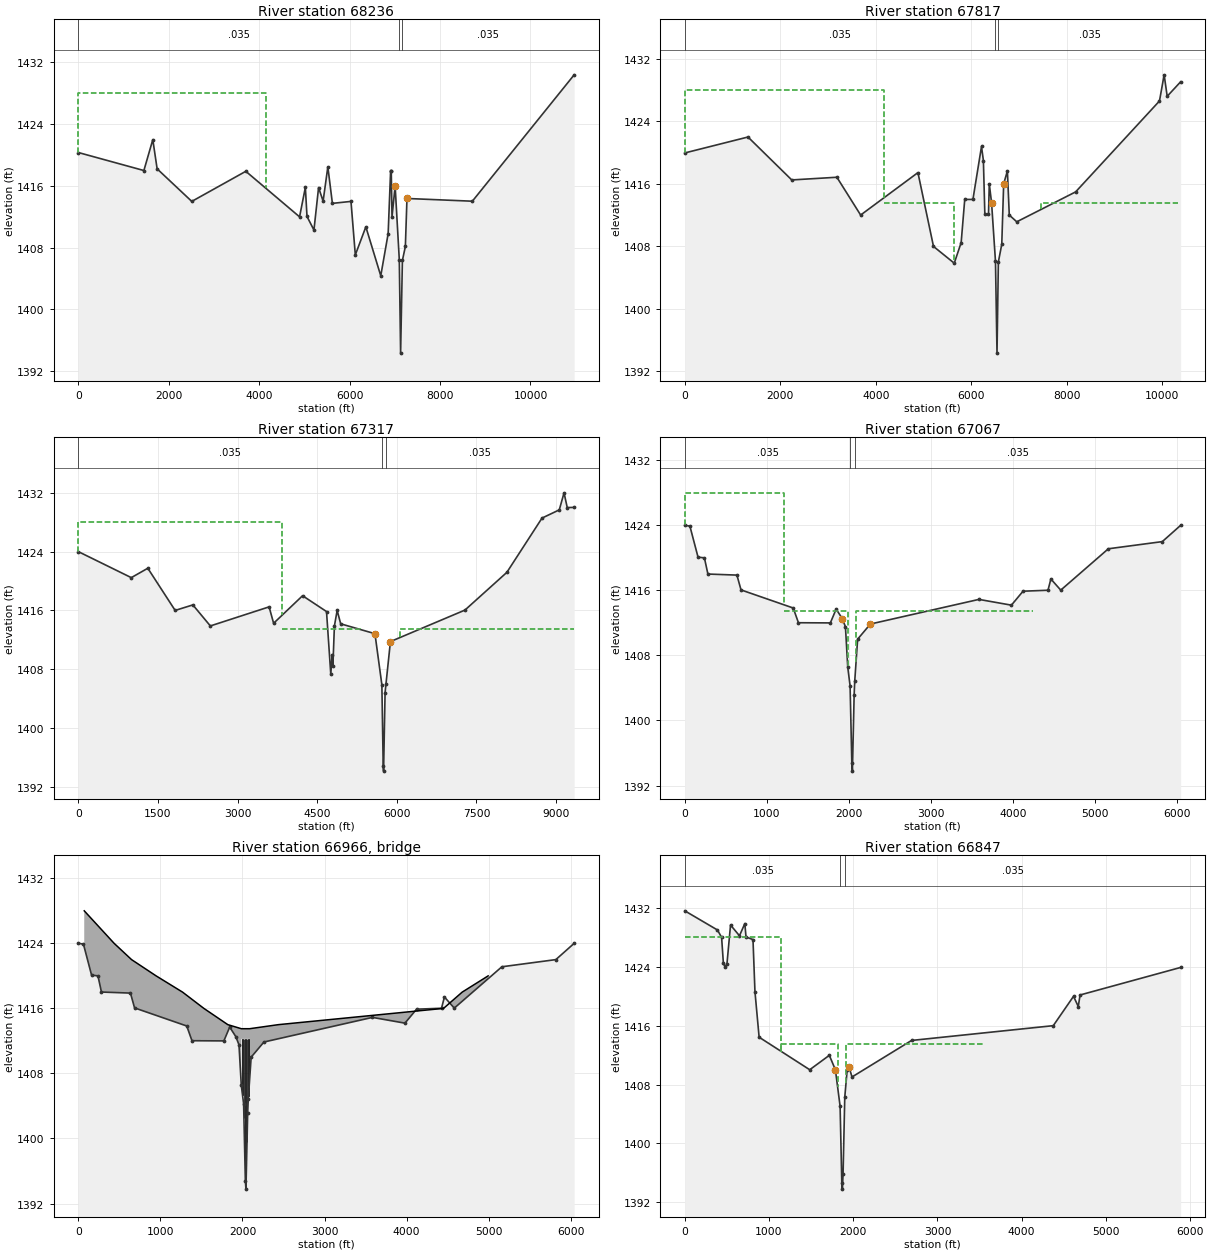
Type RM Length L Ch R = 1 ,68236   ,440.603,418.742,376.128
XS GIS Cut Line= 6
    6271854.9762    2214400.7357    6270100.0362    2216040.1783
    6270021.4155    2216113.6248     6270009.351    2216124.8955
      6269725.97    2216390.2589    6263897.9128    2221847.7668
#Sta/Elev= 30
       01420.3321449.715    14181647.062    14221742.7751418.218 2509.17    1414
3704.1221417.8994892.967    14125020.8331415.8135057.3671412.0475211.025 1410.29
5313.4361415.7985413.5651414.0315518.2571418.4815619.0641413.7466030.062    1414
6125.961 1407.07 6358.861410.7066688.6671404.3656852.0581409.8186906.8571417.997
6920.5581417.9736937.379    14127006.5161415.988 7098.311406.474 7127.571394.347
7167.1561406.3517232.9121408.1597268.286 1414.388714.3411414.026 10965.91430.396
#Mann= 3 ,-1 , 0
       0    .035       0 7098.31     .07       07167.156    .035       0
#XS Ineff= 2 ,-1
       0    4150    1428    4150    5742  1413.5
Permanent Ineff=
       T       F
Bank Sta=7006.516,7268.286
XS Rating Curve= 0 ,0
Exp/Cntr=0.3,0.1

Type RM Length L Ch R = 1 ,67817   ,494.922,499.973,511.295
XS GIS Cut Line= 6
    6270845.6578    2214251.3503    6269675.7065    2215424.9974
    6269663.8418    2215437.6703    6267902.4543    2217319.0645
    6267847.6979    2217377.5514    6263748.7983    2221755.7168
#Sta/Elev= 30
       01419.9581323.335    14222239.896  1416.53185.0941416.8443682.677    1412
4882.4871417.4385208.5651407.9785643.343 1405.835787.8151408.468 5862.82    1414
6034.388    14146213.9841420.7886253.5651418.9866283.9511412.0956360.3031412.074
6376.852    14166425.4491413.5316506.6211406.0796538.6471394.3066566.9471405.983
6638.3081408.2546678.2191415.9896756.2331417.6566795.594    14126952.2591411.134
8185.6181414.9699941.4381426.61810038.991429.96910102.921427.21910384.191429.075
#Mann= 3 ,-1 , 0
       0    .035       06506.621     .07       06566.947    .035       0
#XS Ineff= 3 ,-1
       0    4170    1428    4170    5645  1413.5    7468   10329  1413.5
Permanent Ineff=
       T       T       T
Bank Sta=6425.449,6678.219
XS Rating Curve= 0 ,0
Exp/Cntr=0.3,0.1

Type RM Length L Ch R = 1 ,67317   ,250,250,250
XS GIS Cut Line= 2
     6269983.315     2214531.662     6263478.697     2221233.914
#Sta/Elev= 30
       0    1424 997.587 1420.461308.7491421.7381823.731    14162157.3721416.749
2486.7921413.888  3593.51416.4833678.554 1414.254224.181    14184674.9541415.846
4755.4481407.3224781.0321409.9844795.1761408.4544823.4631413.8774875.537    1416
 4942.111414.1745587.2241412.8355717.4741405.8915742.8051394.8395749.8761394.133
5778.1641404.8185795.2591406.013 5878.87 1411.76 7282.561416.0468072.2821421.181
8734.2011428.5649059.5071429.6819149.177    1432 9209.38    14309339.7131430.011
#Mann= 3 ,-1 , 0
       0    .035       05717.474     .07       05795.259    .035       0
#XS Ineff= 3 ,-1
       0    3843    1428    3843    5331  1413.5    6064 9339.97  1413.5
Permanent Ineff=
       T       T       T
Bank Sta=5587.224,5878.87
XS Rating Curve= 0 ,0
Exp/Cntr=0.3,0.1

Type RM Length L Ch R = 1 ,67067   ,220,220,220
BEGIN DESCRIPTION:
Section Taken Just Upstream of Goetz Road - This section will be skewed with Bridge  jcc 11 DEC 2009
END DESCRIPTION:
XS GIS Cut Line= 2
     6265803.439     2215602.343     6265778.971     2224145.867
#Sta/Elev= 30
       01424.016  62.2561423.898 161.2511420.089 239.033    1420  281.461418.011
 635.015 1417.88 685.0291416.0591320.9111413.8331384.5511412.0221773.461    1412
1844.1721413.6981917.9061412.539 1957.311411.5271985.5941406.5252013.8781404.271
2035.0921394.7792042.1631393.7692063.3761403.1622070.4481404.8172105.803    1410
2261.3671411.8623583.6621414.8913979.6441414.1834121.065  1415.94425.1221416.018
4460.4781417.4014580.6871416.0315160.5171421.1185818.128    14226041.208    1424
#Mann= 3 ,-1 , 0
       0    .035       02013.878     .07       02070.448    .035       0
#XS Ineff= 3 ,-1
       01214.102    14281214.1021986.093  1413.52086.9554242.641  1413.5
Permanent Ineff=
       T       T       T
Bank Sta=1917.906,2261.367
XS Rating Curve= 0 ,0
Skew Angle= 45
Exp/Cntr=0.5,0.3

Type RM Length L Ch R = 3 ,66966   ,,,
BEGIN DESCRIPTION:
Goetz Road Bridge
This is based on field topo.  The sections taken along the Goetz Road and then skewed 45 degrees to match the direction of flow.
END DESCRIPTION:
Bridge Culvert--1,0,-1,-1, 0
Deck Dist Width WeirC Skew NumUp NumDn MinLoCord MaxHiCord MaxSubmerge Is_Ogee
70,42,3,45, 15, 16, 1413.5, , 0.98, 0, 2,2,,
  72.125 436.285 648.417 947.5231269.9641529.4721821.5071986.0931986.0932086.955
2086.9552437.3974449.8234676.8044993.319
    1428    1424    1422    1420    1418    1416    1414  1413.5  1413.5  1413.5
  1413.5    1414    1416    1418    1420
                                                                 1412.25 1412.25
                                        
  50.205  364.16 622.254  921.361198.5461466.5391750.089 1814.04 1814.041914.902
1914.9022369.515 4381.944652.7635008.4375126.524
    1428    1424    1422    1420    1418    1416    1414  1413.5  1413.5  1413.5
  1413.5    1414    1416    1418    1420    1422
                                                                 1412.25 1412.25
                                                
Pier Skew, UpSta & Num, DnSta & Num=  ,2000.143, 2 ,1828.09, 2 , 0 , 0 , 0 ,,
     1.5     1.5
    1380    1415
     1.5     1.5
    1380    1415
Pier Skew, UpSta & Num, DnSta & Num=  ,2017.842, 2 ,1845.789, 2 , 0 , 0 , 0 ,,
     1.5     1.5
    1380    1415
     1.5     1.5
    1380    1415
Pier Skew, UpSta & Num, DnSta & Num=  ,2036.694, 2 ,1864.641, 2 , 0 , 0 , 0 ,,
     1.5     1.5
    1380    1415
     1.5     1.5
    1380    1415
Pier Skew, UpSta & Num, DnSta & Num=  ,2055.284, 2 ,1883.23, 2 , 0 , 0 , 0 ,,
     1.5     1.5
    1380    1415
     1.5     1.5
    1380    1415
Pier Skew, UpSta & Num, DnSta & Num=  ,2072.94, 2 ,1900.887, 2 , 0 , 0 , 0 ,,
     1.5     1.5
    1380    1415
     1.5     1.5
    1380    1415
Abutment Skew #Up #Dn= , 2 , 2
1986.0932017.842
 1411.25    1404
 1814.041845.789
 1411.25    1404
Abutment Skew #Up #Dn= , 2 , 2
2055.2842086.955
    1404 1411.25
 1883.231914.902
    1404 1411.25
BR Coef=-1 , 1 , 0 ,, 0 ,,,0.8,-1,1.2,0,
WSPro=,,,, 1 ,,,, 0 ,,,, 0 ,,,,-1 ,-1 ,-1 , 0 , 0 , 0 , 0 , 0
BC Design=,, 0 ,, 0 ,,,,,,
BC Use User HTab Curves=0
BC User HTab FreeFlow(D)= 0

Type RM Length L Ch R = 1 ,66847   ,30,30,30
BEGIN DESCRIPTION:
Section Taken Just Downstream of Goetz Road - This section will be skewed with Bridge  jcc 11 DEC 2009
END DESCRIPTION:
XS GIS Cut Line= 2
     6265647.533     2215702.258     6265623.687     2224029.063
#Sta/Elev= 30
       01431.627 387.5861429.022 437.0841428.018 458.2981424.478 479.5111423.966
 500.7241424.423 543.1511429.698 649.2171428.236 712.8571429.895 726.9991428.064
 809.8321427.719 833.0661420.647 882.5631414.4411483.5151410.0181716.3771411.978
1788.4451410.0051844.2321405.0551864.4461394.6341871.4971393.7811879.5881395.899
1899.7011406.2861927.9051409.9451951.5481410.3481985.6541409.0332692.764    1414
4375.685 1416.014616.103    14204672.6711418.6144693.8841420.1835887.9641423.928
#Mann= 3 ,-1 , 0
       0    .035       01844.232     .07       01899.701    .035       0
#XS Ineff= 3 ,-1
       01146.927    14281146.927 1814.04  1413.51914.9023535.534  1413.5
Permanent Ineff=
       T       F       F
Bank Sta=1788.445,1951.548
XS Rating Curve= 0 ,0
Skew Angle= 45
Exp/Cntr=0.5,0.3

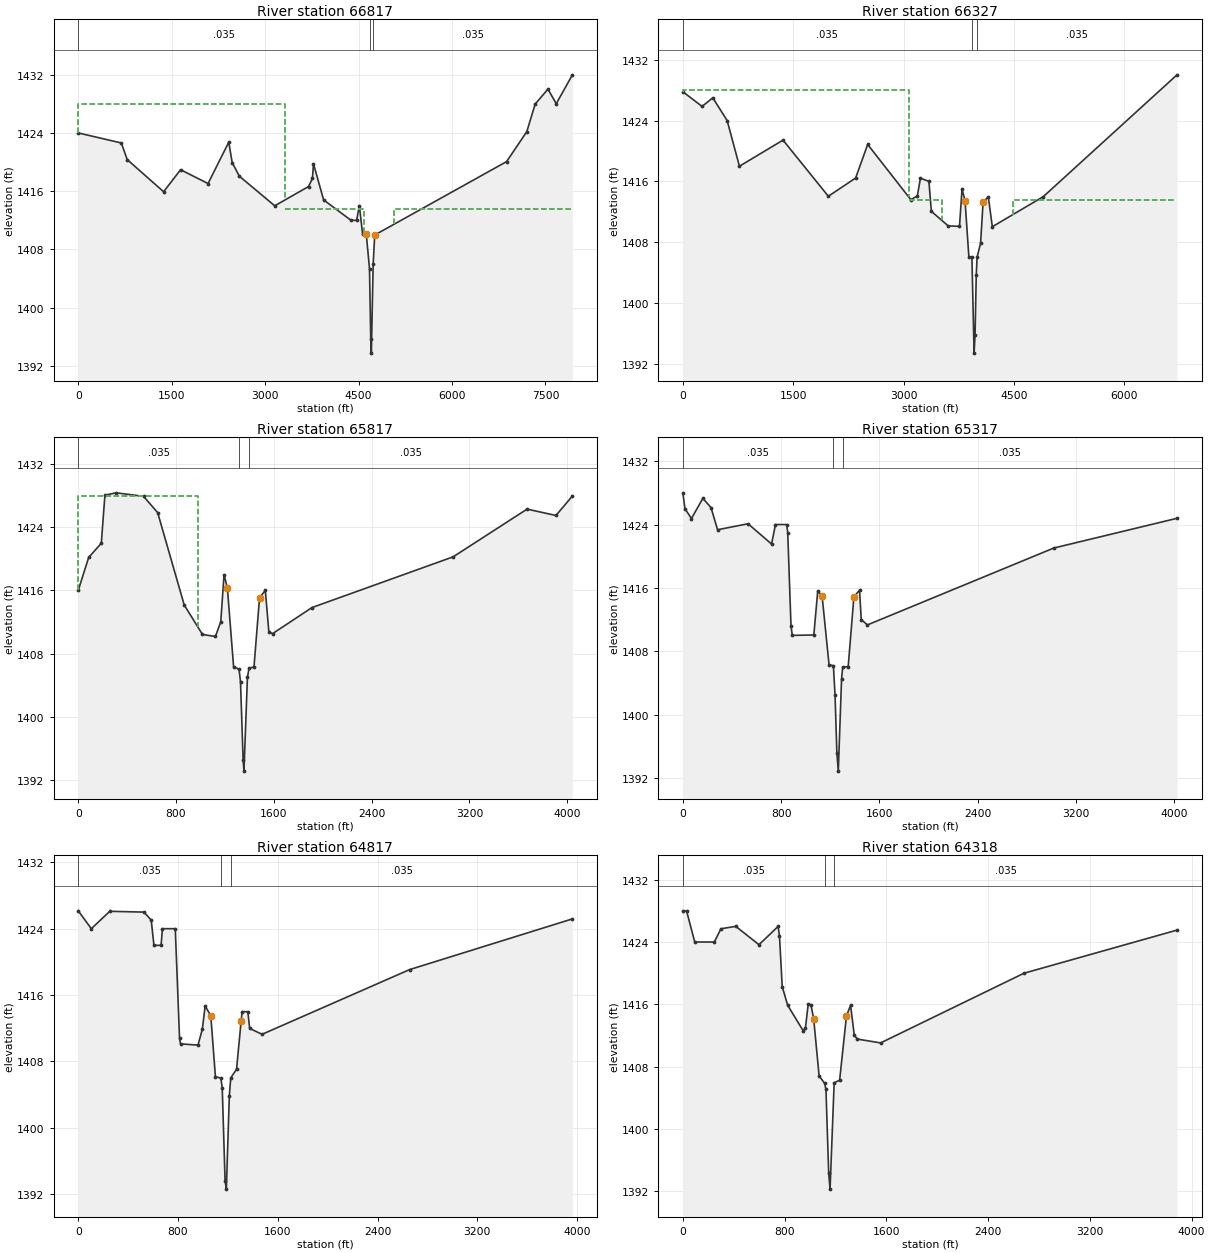
Type RM Length L Ch R = 1 ,66817   ,488.943,490.173,495.119
XS GIS Cut Line= 2
     6268787.315     2214851.759      6263416.04     2220689.036
#Sta/Elev= 30
       01424.011 691.1921422.632 786.3171420.346 1370.661415.9311642.4471418.957
2083.9071417.0572415.9841422.7382471.399 1419.932586.3871418.0653154.402    1414
3697.5031416.6493759.9041417.7673775.9781419.7813939.0511414.8084380.175    1412
4468.7851412.006 4513.09    14144564.161 1410.154624.6141410.0624675.5421405.351
4695.3851395.7244705.0791393.7554734.6161405.991 4759.081409.9866876.027 1420.07
7200.4991424.1857335.1721427.979 7540.411430.0317673.5191428.025 7932.491431.996
#Mann= 3 ,-1 , 0
       0    .035       04675.542     .07       04734.616    .035       0
#XS Ineff= 3 ,-1
       0    3325    1428    3325    4590  1413.5    5063 7932.49  1413.5
Permanent Ineff=
       T       F       F
Bank Sta=4624.614,4759.08
XS Rating Curve= 0 ,0
Exp/Cntr=0.3,0.1

Type RM Length L Ch R = 1 ,66327   ,512.084,509.915,510.645
XS GIS Cut Line= 6
    6267944.6375    2215068.9381    6265311.6366    2217905.6875
      6265242.75    2217979.9049    6264399.7486      2218888.14
    6264393.0136     2218895.396    6263394.9866    2219970.6531
#Sta/Elev= 30
       01427.813 261.2061425.878 406.6491427.012 602.2991424.011 769.139    1418
1361.9051421.438 1977.681414.0422348.6941416.4442512.4191420.8663099.0981413.594
3187.5061414.0823229.9611416.4233344.685    14163378.5571412.0533606.1431410.146
3760.6591410.0763794.9281414.9673835.8591413.4793888.0271406.0743929.532    1406
3958.9311393.3753972.296 1395.79 3988.331403.6033999.583    14064047.128 1407.85
4081.4461413.231 4152.111413.9784206.9821410.027 4901.321414.0046717.493 1430.04
#Mann= 3 ,-1 , 0
       0    .035       03929.532     .07       03999.583    .035       0
#XS Ineff= 3 ,-1
       0    3068    1428    3068    3517  1413.5    4486 6687.76  1413.5
Permanent Ineff=
       T       F       F
Bank Sta=3835.859,4081.446
XS Rating Curve= 0 ,0
Exp/Cntr=0.3,0.1

Type RM Length L Ch R = 1 ,65817   ,510.902,499.882,492.717
XS GIS Cut Line= 6
    6265799.1095    2216622.3803    6265003.0642    2217487.4889
    6264943.4484    2217552.2767    6264628.0409    2217895.0485
    6264144.0191    2218421.0629    6263070.3566    2219587.8743
#Sta/Elev= 30
       0    1416  85.2341420.171 188.6121421.966 218.1491428.063 309.8451428.357
 533.9581427.914 649.5791425.857 867.0091414.1451016.492 1410.411122.2421410.156
1165.9751412.023 1192.86    14181220.3331416.2551270.8621406.3361315.458    1406
 1327.481404.4231348.7111394.5381355.7881393.0981384.0971404.9711396.9951406.123
1437.7631406.3041483.1781415.0631530.495    14161559.2081410.7691589.5681410.515
1912.5321413.8233067.0411420.2473671.9061426.294  3908.21425.486 4042.651427.953
#Mann= 3 ,-1 , 0
       0    .035       01315.458     .07       01396.995    .035       0
#XS Ineff= 2 , 0
       0     979    1428               0
Permanent Ineff=
       T       F
Bank Sta=1220.333,1483.178
XS Rating Curve= 0 ,0
Exp/Cntr=0.3,0.1

Type RM Length L Ch R = 1 ,65317   ,585.896,499.588,419.787
XS GIS Cut Line= 2
     6265337.133     2216337.679     6262691.738     2219366.285
#Sta/Elev= 30
       01428.007  16.872    1426  69.9821424.763 162.9251427.313 229.313 1426.14
 282.3841423.345 530.436  1424.1 721.7891421.538  753.57    1424 844.776    1424
 853.3611422.994 879.9161411.248 890.379    14101065.8031410.051 1097.411415.585
1132.8461415.0171189.5431406.3021225.1341406.1551238.412 1402.481253.3281395.149
1264.9671392.8531291.5221404.5061300.8061405.9811345.4611406.0681392.0121414.874
1437.6151415.7111451.7691412.0061501.3791411.3193018.5191421.0334021.265 1424.79
#Mann= 3 ,-1 , 0
       0    .035       01225.134     .07       01300.806    .035       0
Bank Sta=1132.846,1392.012
XS Rating Curve= 0 ,0
Exp/Cntr=0.3,0.1

Type RM Length L Ch R = 1 ,64817   ,549.221,499.439,451.105
XS GIS Cut Line= 3
     6264663.061     2215968.432     6263644.063     2217823.711
     6262655.654       2219382.4
#Sta/Elev= 30
       01426.153 104.911    1424 252.7281426.095 527.046    1426 585.0851425.034
  606.91    1422 663.9551421.994 675.364    1424 778.046    1424 812.273 1410.79
 820.1011410.123 960.0221409.972 994.8181411.8741017.6361414.682 1062.851413.509
1099.9441406.1671143.135    14061154.5451404.8581177.3631393.6441187.4841392.621
 1211.591403.9011222.9991406.0311269.3221407.0591306.1441412.8671314.271    1414
1359.908    14141374.4351411.9831473.9981411.2752657.4531419.074 3962.36 1425.18
#Mann= 3 ,-1 , 0
       0    .035       01143.135     .07       01222.999    .035       0
Bank Sta=1062.85,1306.144
XS Rating Curve= 0 ,0
Exp/Cntr=0.3,0.1

Type RM Length L Ch R = 1 ,64318   ,532.348,499.504,468.255
XS GIS Cut Line= 2
     6264072.036     2215703.426     6262650.272     2219318.767
#Sta/Elev= 30
       0    1428  29.0741427.998  93.443    1424 247.667    1424 298.9361425.697
 415.807 1426.01  598.481423.656 748.916    1426 759.6621424.758 781.1531418.268
 824.1351415.875 946.7841412.593 963.8261412.997 985.3461415.9981006.8081415.951
1028.2991414.1791071.2811406.8041114.2631405.8881125.0081405.0951146.4991394.366
1157.2451392.2991189.481 1405.951232.4631406.265 1286.191414.5031318.4271415.881
1347.833 1412.041372.1541411.5461554.8271411.0572682.0911419.9973884.8561425.528
#Mann= 3 ,-1 , 0
       0    .035       01114.263     .07       01189.481    .035       0
Bank Sta=1028.299,1286.19
XS Rating Curve= 0 ,0
Exp/Cntr=0.3,0.1