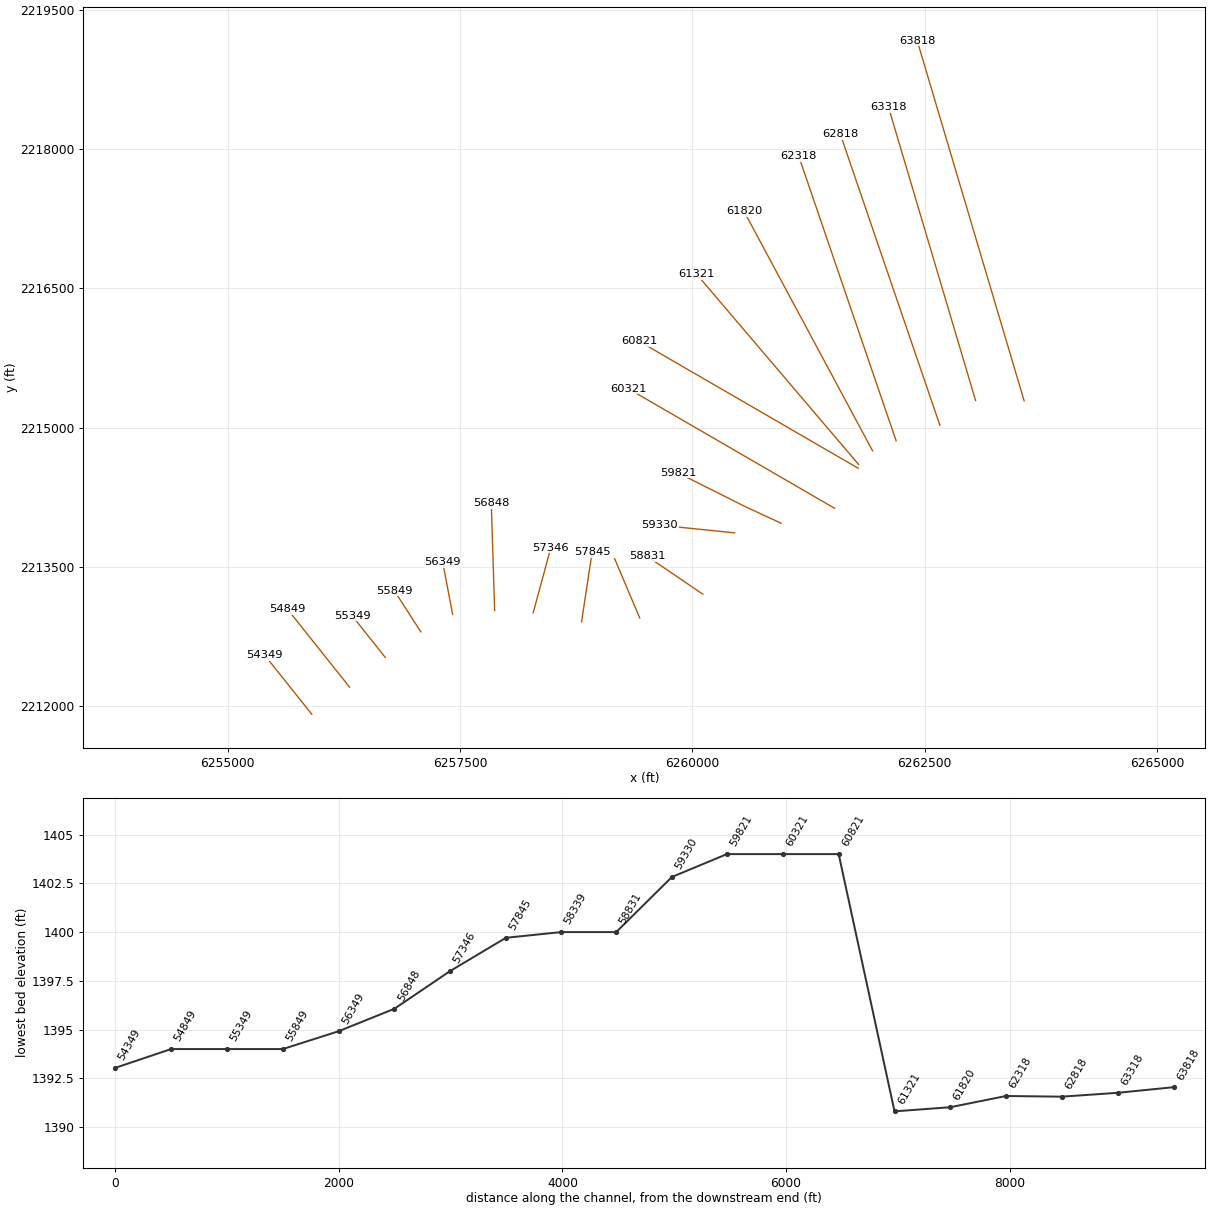
HEC-RAS study R3.prj: San Jacinto Stage III Reach 3

--- R3.g29 (geometry) --- (continued)

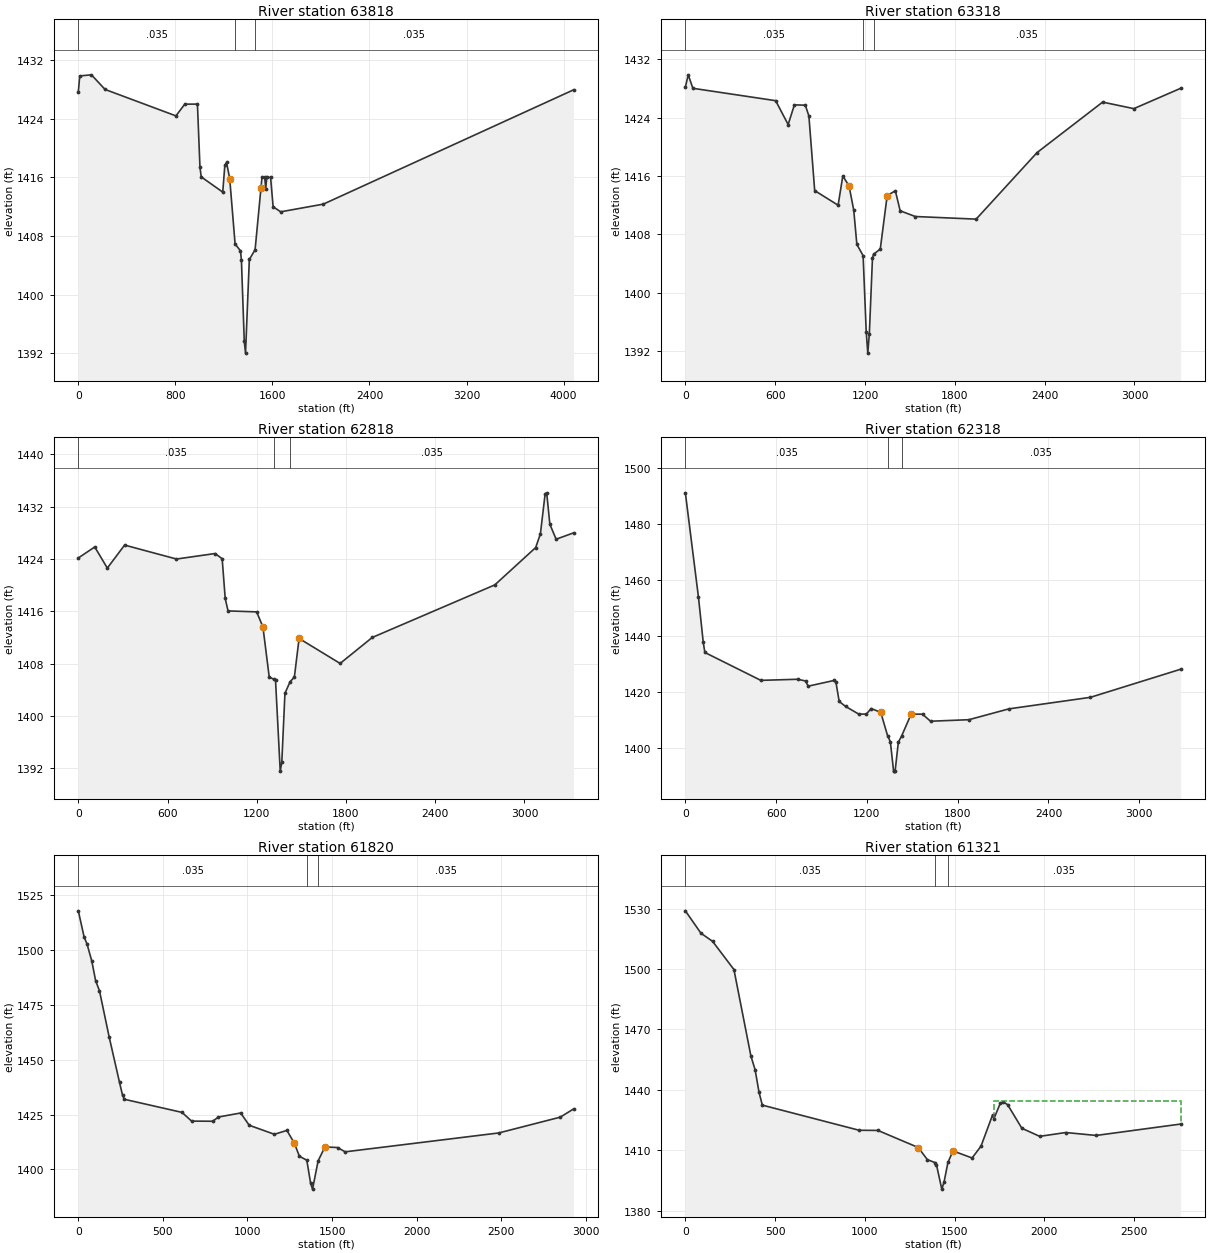
Type RM Length L Ch R = 1 ,63818   ,500.024,500,500.222
XS GIS Cut Line= 6
    6263571.6532    2215289.0961    6263217.3778    2216482.3522
    6262895.6989    2217565.8176    6262782.8345    2217945.9632
    6262578.2574    2218635.0111    6262421.0415    2219164.5396
#Sta/Elev= 30
       01427.629  11.7771429.842 108.1621429.992 220.406    1428 804.5661424.395
 877.5861425.993   981.9    14261002.7631417.3861013.1951416.0761190.529    1414
1207.751 1417.661221.8231418.0391247.9671415.835 1292.291406.9261336.5691405.997
1344.4881404.7091367.8631393.6691378.2951392.0441409.5891404.8241457.0951406.136
1505.3551414.5271513.904    14161536.102    14161544.8281414.4891553.555    1416
1584.849 1416.011605.712    14121668.3011411.3132019.566 1412.364082.2951427.948
#Mann= 3 ,-1 , 0
       0    .035       0 1292.29     .07       01457.095    .035       0
Bank Sta=1247.967,1505.355
XS Rating Curve= 0 ,0
Exp/Cntr=0.3,0.1

Type RM Length L Ch R = 1 ,63318   ,484.415,499.819,514.433
XS GIS Cut Line= 6
    6263049.1812    2215292.1281    6262735.8303    2216347.5437
    6262534.2464    2217026.5107    6262438.7653    2217348.1059
    6262417.2653    2217420.5217    6262111.5792    2218450.1211
#Sta/Elev= 30
       01428.143  19.0451429.844   50.34    1428 603.2061426.306 686.6571423.039
 728.3831425.732 801.403 1425.69 825.2851424.204 863.992    14141020.463    1412
1051.758    1416 1093.381414.6451124.7781411.3381145.6411406.6391187.3661405.101
1208.2291394.6791218.6611391.7561229.0921394.4311249.9551404.759 1257.071405.287
1302.112    14061348.1041413.3051402.7821413.9791434.9551411.2381535.6331410.454
1942.4591410.0942349.285  1419.22787.4051426.1112996.0341425.2163308.701    1428
#Mann= 3 ,-1 , 0
       0    .035       01187.366     .07       0 1257.07    .035       0
Bank Sta=1093.38,1348.104
XS Rating Curve= 0 ,0
Exp/Cntr=0.3,0.1

Type RM Length L Ch R = 1 ,62818   ,501.027,500.015,500.265
XS GIS Cut Line= 6
    6262665.1355     2215025.788    6262628.7483    2215132.1668
    6261844.0206    2217426.3413    6261696.8594    2217856.5717
    6261660.8127     2217961.955    6261592.5569    2218161.5032
#Sta/Elev= 30
       01424.164 110.5481425.848 195.0981422.618 311.3551426.134 660.1261424.001
  920.081424.844 967.3311424.043  987.761417.9761006.7061416.0651199.1361415.918
1241.4111413.6111283.6871405.9531315.393  1405.61325.9621405.5241357.6681391.558
1368.2371392.8991389.3751403.4641424.0871405.2281452.7881405.9471484.4941411.855
1760.398 1408.031976.5231412.0042800.5981420.0463075.3871425.7593107.0941427.855
  3138.81433.9713149.3691434.1283170.5061429.3223212.7821427.031 3330.221428.005
#Mann= 3 ,-1 , 0
       0    .035       01315.393     .07       01424.087    .035       0
Bank Sta=1241.411,1484.494
XS Rating Curve= 0 ,0
Exp/Cntr=0.3,0.1

Type RM Length L Ch R = 1 ,62318   ,441.519,498.258,545.036
XS GIS Cut Line= 6
    6262193.9493    2214858.4017    6261870.8543    2215802.9796
    6261774.1023    2216085.8366    6261709.8765    2216273.6029
    6261687.9728    2216337.6387    6261145.1096    2217924.7155
#Sta/Elev= 30
       01491.213  86.6871453.821 118.3541437.644 128.9231434.062 498.8321424.083
 741.9151424.476 794.7591423.863 811.693    1422 984.9971424.074 995.5661423.366
1016.7041416.5391058.9791414.7511145.4661412.0261196.374    1412 1228.08    1414
1291.4931412.6311336.5151404.3091354.9061402.1071376.0441391.7771381.7191391.592
1386.6131391.689 1407.751401.949 1428.97  1404.11492.301    14121567.6071411.974
1620.4511409.4541874.103    14102138.3231413.8792677.333 1418.013273.7631428.065
#Mann= 3 ,-1 , 0
       0    .035       01336.515     .07       0 1428.97    .035       0
Bank Sta=1291.493,1492.301
XS Rating Curve= 0 ,0
Exp/Cntr=0.3,0.1

Type RM Length L Ch R = 1 ,61820   ,427.551,498.528,543.781
XS GIS Cut Line= 2
     6261940.961      2214750.17     6260556.217     2217330.166
#Sta/Elev= 30
       01517.877  34.2931505.969  51.536 1502.75   79.691495.008 102.3891486.028
 125.088 1481.45 181.834 1460.58 243.5571439.699  261.281433.912 272.6291431.966
 613.1091425.998 669.8551422.026 794.6981421.961 828.7461423.893 959.9411425.725
1010.3351420.1291159.3471416.0161233.2011417.7841277.5141411.9231307.0551406.001
1350.8151404.2021373.5241393.6551384.8631391.0171417.8361403.9281458.1261410.239
1532.4041409.9821577.8011408.0212485.7471416.6252848.926 1423.822928.1221427.576
#Mann= 3 ,-1 , 0
       0    .035       01350.815     .07       01417.836    .035       0
Bank Sta=1277.514,1458.126
XS Rating Curve= 0 ,0
Exp/Cntr=0.3,0.1

Type RM Length L Ch R = 1 ,61321   ,389.412,499.567,583.656
XS GIS Cut Line= 6
    6261789.9075    2214604.2509    6260715.9898    2215865.9574
     6260675.789     2215913.188    6260481.8705    2216141.0156
     6260313.931    2216338.32176260046.317746252216652.73055002
#Sta/Elev= 30
       0 1528.85  86.8481517.746 151.9861513.691 270.6951499.721 365.0851456.915
 388.8831449.963 410.3841438.909  428.931432.469 968.065 1420.011073.1551419.919
1297.7761411.4511348.9931405.4161392.2641403.9421399.3581402.9431429.0951390.804
1441.5621394.2351463.2031404.0161491.5791409.7621597.9871406.2551647.6441412.111
1712.182 1427.621719.6341425.7651754.7681433.2881772.297    14341795.8871432.708
1875.3641420.9911974.6791416.982 2119.881418.881 2289.591417.4312760.2721423.085
#Mann= 3 ,-1 , 0
       0    .035       01392.264     .07       01463.203    .035       0
#XS Ineff= 2 , 0
                         1718.06         1434.46
Permanent Ineff=
       F       F
Bank Sta=1297.776,1491.579
XS Rating Curve= 0 ,0
Exp/Cntr=0.3,0.1

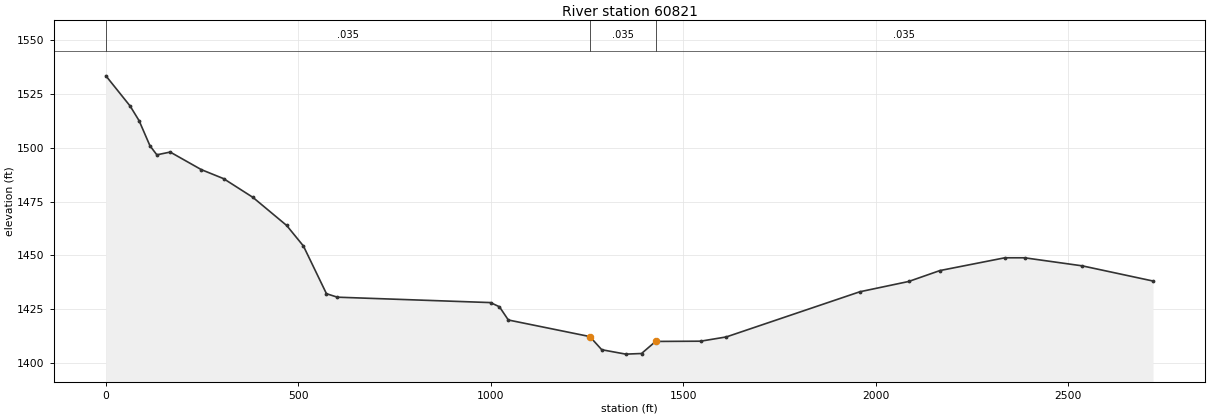
Type RM Length L Ch R = 1 ,60821   ,502.739,500.048,501.639
XS GIS Cut Line= 2
     6261785.927     2214562.971       6259432.2     2215927.567
#Sta/Elev= 30
       01533.526  63.0331519.441  86.1511512.686 114.4721500.969 132.388 1496.76
 167.0651498.045 247.9781489.863 305.7741485.675 381.9071476.966 469.7111463.871
 513.2261454.313 573.0391432.126 601.4161430.502 999.3181427.9881022.4361426.041
1045.5541419.8911257.3381412.1721288.2951406.0471350.609    1404 1391.651404.288
1428.2351409.9051545.3071410.0221611.9491412.0061958.7211433.0162085.8711437.818
2166.7841442.8862335.5411448.838 2386.761448.8392536.6741445.087 2720.691438.019
#Mann= 3 , 0 , 0
       0    .035       01257.338    .035       01428.235    .035       0
Bank Sta=1257.338,1428.235
XS Rating Curve= 0 ,0
Exp/Cntr=0.3,0.1

Type RM Length L Ch R = 6 ,60723   ,,,
Lateral Weir Pos= 3
Lateral Weir TW Multiple XS=0
Lateral Weir Coef=2
LW OverFlow Method 2D=False
Lateral Weir WSCriteria=-1
Lateral Weir Flap Gates= 0
Lateral Weir Hagers EQN= 0 ,,,,,
Lateral Weir SS=0.05,0.05,
Lateral Weir Type= 0
Lateral Weir Connection Pos and Dist= 3 ,
Lateral Weir SE= 0
Lateral Weir Centerline= 0
LW Div RC= 9 ,False,
 1393.27      50 1394.41     100 1396.18     200 1397.93     300 1402.82     400
 1406.12     500 1410.16     600 1414.94     700 1420.44     800

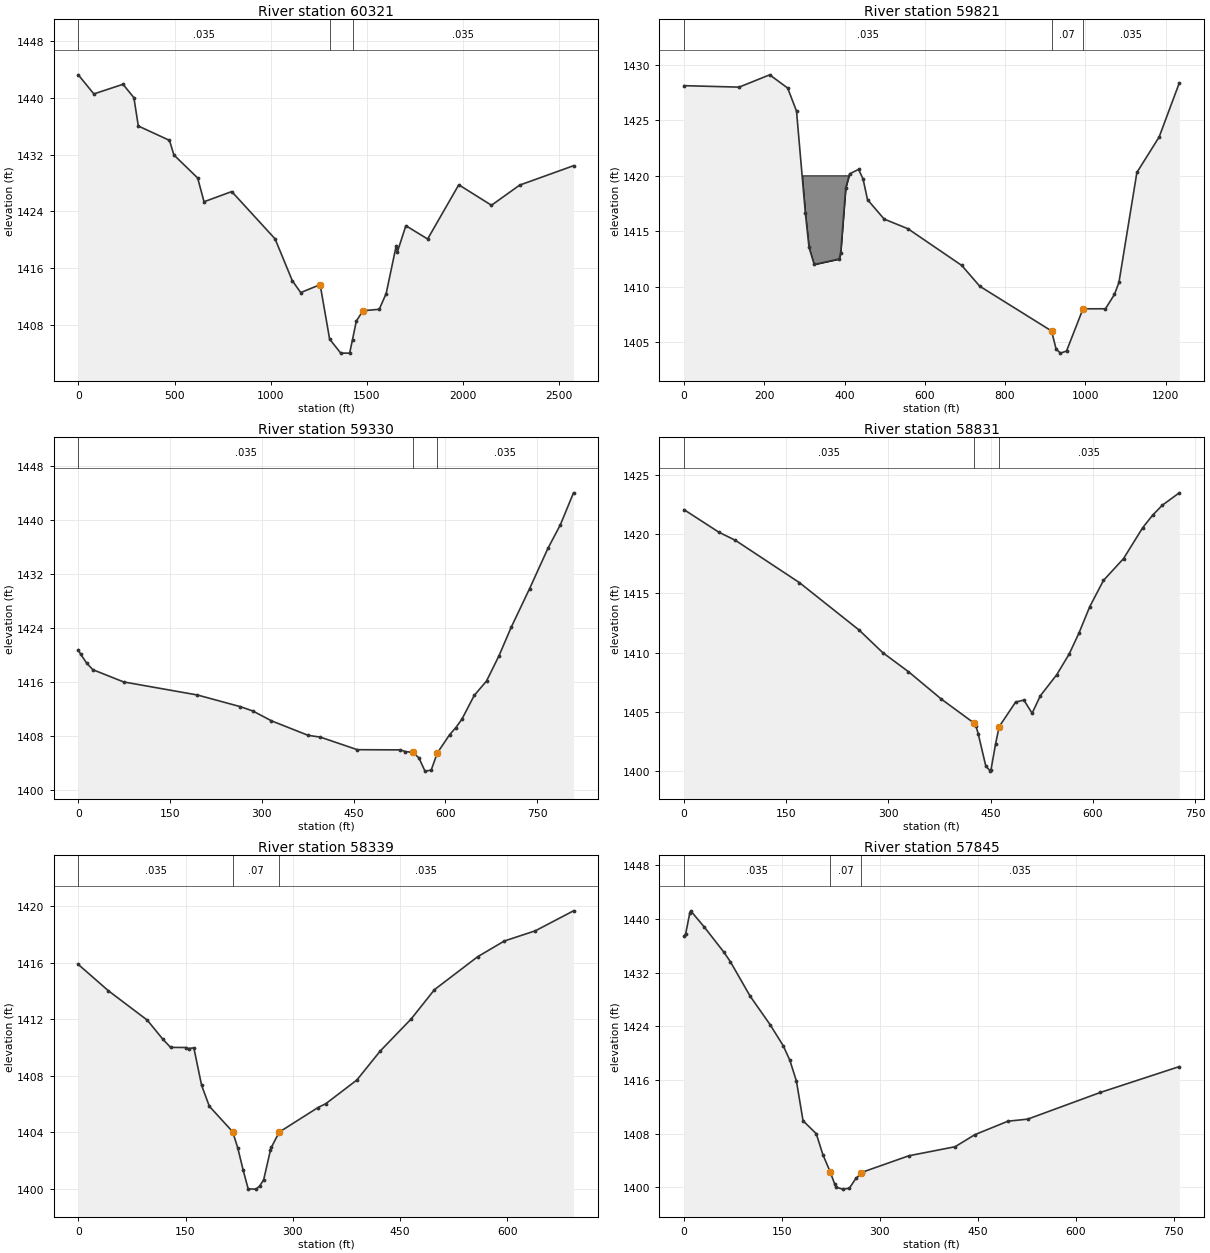
Type RM Length L Ch R = 1 ,60321   ,475.681,499.787,516.943
XS GIS Cut Line= 6
    6261531.2769    2214132.6535    6260617.4146    2214662.4741
    6260444.8318    2214762.5307    6260439.9567    2214765.3572
    6259635.9465    2215231.4899    6259315.6303    2215417.1965
#Sta/Elev= 30
       01443.241  80.776 1440.55 232.3971441.906  288.841440.022 311.9581436.023
 473.785    1434 496.9031431.941 620.1971428.698 653.4231425.345 797.4391426.781
1022.6311420.107 1111.991414.218 1155.771412.5371256.7751413.6581306.0381405.977
1363.833    14041410.069    14041425.0651405.9171444.7471408.5181479.4241409.982
1563.7321410.1791599.8361412.3981652.3281419.1611658.4761418.3021702.2081421.967
1815.3741420.0931977.2011427.7392147.1081424.8492293.4481427.6892573.3781430.424
#Mann= 3 ,-1 , 0
       0    .035       01306.038     .07       01425.065    .035       0
Bank Sta=1256.775,1479.424
XS Rating Curve= 0 ,0
Exp/Cntr=0.3,0.1

Type RM Length L Ch R = 1 ,59821   ,332.534,491.272,538.845
BEGIN DESCRIPTION:
Blocked Area is WQ Marsh for Adjacent Tract
jcc  20 Aug 2009
END DESCRIPTION:
XS GIS Cut Line= 3
     6260955.898     2213971.706     6260586.032     2214142.223
     6259846.974     2214513.309
#Sta/Elev= 30
       01428.132 137.096    1428 213.431 1429.11 258.2241427.917 280.2471425.836
  302.271416.635  311.411413.538 324.293    1412 386.7791412.494 390.3621413.063
 402.8921418.908 412.4681420.172 434.8471420.579 446.0371419.721 457.2271417.845
 498.7581416.094 557.9351415.224 692.2121411.909 736.9711410.036 915.9241405.998
 927.198 1404.38  938.04    1404 953.1711404.186 994.336    14081050.2851408.002
1072.6651409.2971083.8541410.3731128.6141420.3011184.1021423.5041234.2691428.373
#Mann= 3 , 0 , 0
       0    .035       0 915.924     .07       0 994.336    .035       0
#Block Obstruct= 1 ,-1
  294.87  426.78 1420.04
Bank Sta=915.924,994.336
XS Rating Curve= 0 ,0
Exp/Cntr=0.3,0.1

Type RM Length L Ch R = 1 ,59330   ,700.378,498.855,440.172
XS GIS Cut Line= 2
     6260454.991     2213867.925     6259649.991     2213949.983
#Sta/Elev= 30
       01420.783   3.6141420.162  13.6661418.822  23.7181417.844  73.9771416.031
 194.5991414.097 264.9611412.365 285.0651411.734 315.6711410.271 375.5311408.125
 395.6351407.858 455.946    1406 526.3091405.972 534.5991405.721 546.4121405.604
 556.4641404.805 566.5161402.828 576.5681402.968  586.621405.512 606.7231408.222
 616.7751409.251 626.8271410.517  646.931414.026 667.0341416.164 687.1381419.844
 707.2411424.092 737.3971429.833 767.5521435.828 787.6561439.276 809.1721444.014
#Mann= 3 , 0 , 0
       0    .035       0 546.412     .07       0  586.62    .035       0
Bank Sta=546.412,586.62
XS Rating Curve= 0 ,0
Exp/Cntr=0.3,0.1

Type RM Length L Ch R = 1 ,58831   ,624.909,491.981,412.339
XS GIS Cut Line= 2
     6260113.691     2213207.505     6259512.807     2213616.378
#Sta/Elev= 30
       0 1422.07  51.1581420.167  75.3491419.484 169.2751415.914 256.7821411.915
 291.637    1410 329.3551408.394 377.7371406.074 426.1191404.033 428.3941403.796
 431.7381403.149  442.791400.437 449.513    1400 450.3111400.071 457.1861402.298
 462.4061403.751 486.5971405.829 498.693    1406 510.7881404.886 522.884 1406.36
 547.0751408.151 565.1521409.882 579.5481411.655 595.4571413.891 615.5371416.098
 645.0461417.947 673.1191420.551 687.5141421.596  701.911422.449   726.81423.494
#Mann= 3 , 0 , 0
       0    .035       0 426.119     .07       0 462.406    .035       0
Bank Sta=426.119,462.406
XS Rating Curve= 0 ,0
Exp/Cntr=0.3,0.1

Type RM Length L Ch R = 1 ,58339   ,575.329,494.229,395.965
XS GIS Cut Line= 2
     6259434.833     2212951.526     6259164.833     2213589.526
#Sta/Elev= 30
       01415.866  42.1961414.006   96.491411.935 118.2071410.592 129.065 1410.01
 150.783    1410 154.3471409.928 161.6411409.981   172.51407.331 183.359 1405.85
 215.9341404.051 223.0151402.927 230.6451401.341 237.6521400.018  248.51    1400
 253.5341400.202 259.3691400.669 268.7931402.754 270.2271402.965 281.0861404.026
 335.3791405.764 346.2381406.033 389.6721407.704 422.2481409.746 465.6831412.019
 498.2591414.087 558.7231416.413 595.9861417.522 639.4211418.244  692.781419.654
#Mann= 3 , 0 , 0
       0    .035       0 215.934     .07       0 281.086    .035       0
Bank Sta=215.934,281.086
XS Rating Curve= 0 ,0
Exp/Cntr=0.3,0.1

Type RM Length L Ch R = 1 ,57845   ,514.213,499.263,481.295
XS GIS Cut Line= 2
     6258808.677     2212909.698     6258922.502     2213659.637
#Sta/Elev= 30
    .6961437.453   2.9911437.738   9.5031440.931   10.811441.219  31.0391438.874
  61.3831435.083  71.4971433.637 101.8411428.484 132.1851424.263 152.4141421.102
 162.5281418.938 172.6431415.818 182.7571409.908 202.9861407.973 213.1011404.858
 224.1421402.323 231.3151400.427  233.331399.991 243.4441399.708 253.5591399.833
 263.6741401.311  271.841402.048 273.7881402.245  344.591404.681 415.3911406.029
 445.7351407.833 496.308 1409.84 526.651 1410.15 637.9111414.134 758.5281417.984
#Mann= 3 , 0 , 0
    .696    .035       0 224.142     .07       0  271.84    .035       0
Bank Sta=224.142,271.84
XS Rating Curve= 0 ,0
Exp/Cntr=0.3,0.1

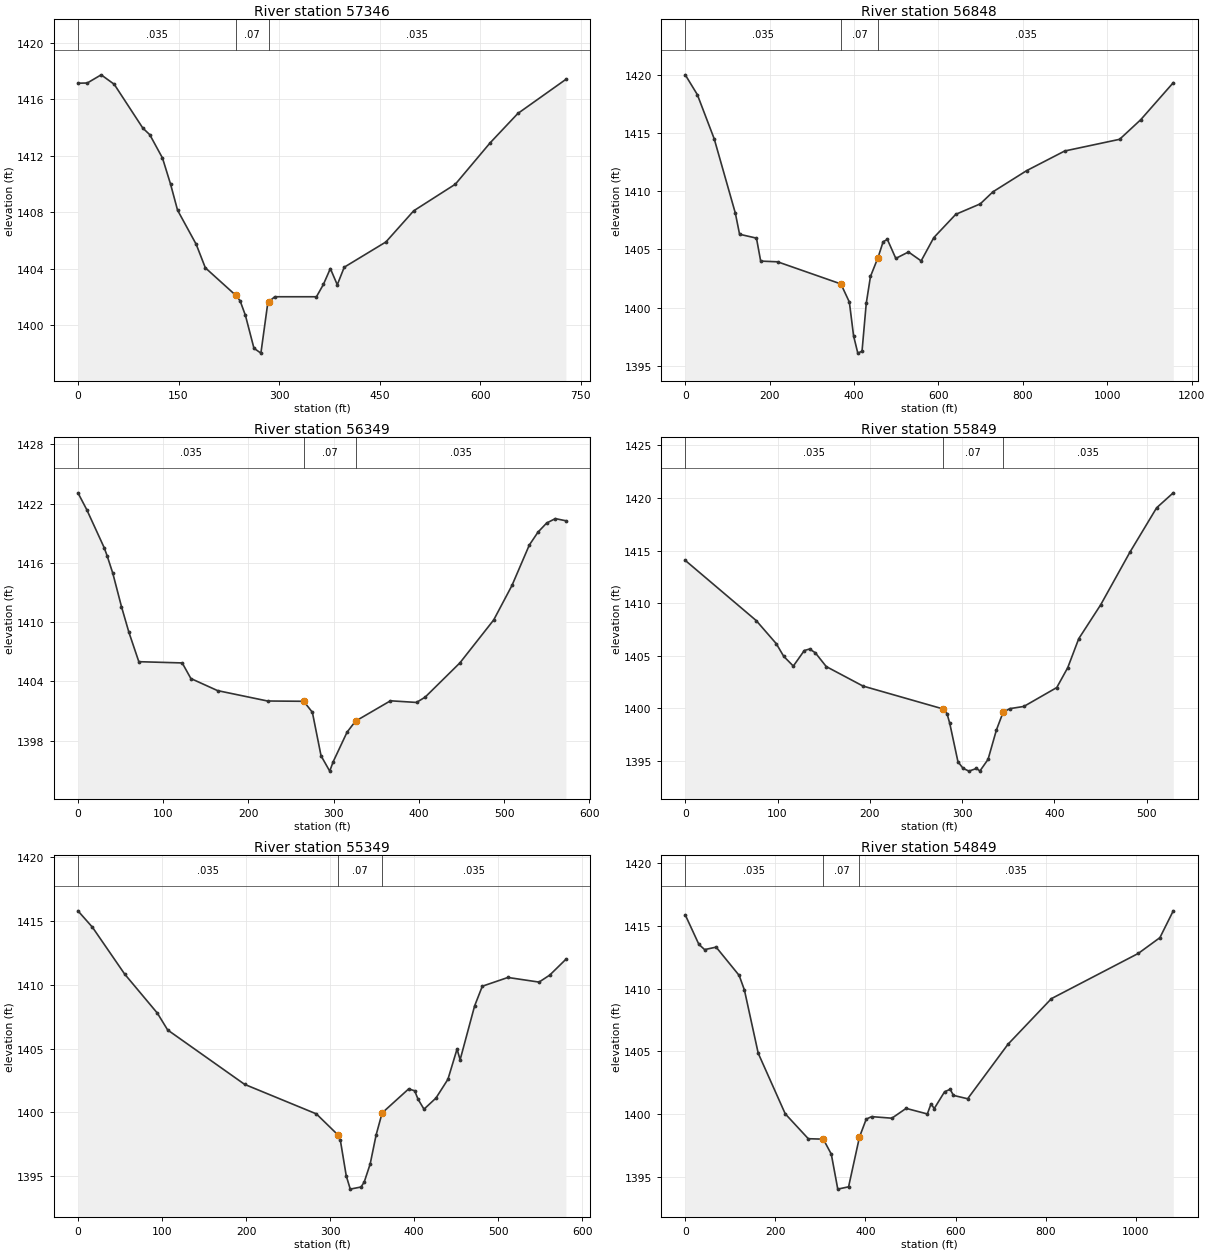
Type RM Length L Ch R = 1 ,57346   ,453.727,498.048,544.871
XS GIS Cut Line= 2
     6258288.506     2213006.936     6258478.324     2213709.609
#Sta/Elev= 30
       01417.151  13.9321417.165  34.6491417.745  54.1021417.075    96.81413.965
 107.1581413.497 126.1161411.841 138.2331409.975 148.592 1408.14 176.4331405.717
 190.0261404.052  235.351402.104 241.8181401.719 249.8311400.675 262.5351398.346
 272.893    1398 283.2521401.588 284.641 1401.65  293.61    1402 355.761    1402
 366.1191402.874 376.478    1404 386.8361402.849 397.1951404.096 459.3451405.887
 500.7791408.096  562.931409.986 614.7221412.915 656.1561415.004  727.861417.425
#Mann= 3 , 0 , 0
       0    .035       0  235.35     .07       0 284.641    .035       0
Bank Sta=235.35,284.641
XS Rating Curve= 0 ,0
Exp/Cntr=0.3,0.1

Type RM Length L Ch R = 1 ,56848   ,463.71,498.764,521.989
XS GIS Cut Line= 2
     6257873.523     2213031.774     6257837.237     2214187.449
#Sta/Elev= 30
       01420.055  28.6261418.347  68.6461414.531  118.671408.131 128.6751406.314
 168.6951405.979   178.7    1404  218.721403.939 368.7941402.031 388.8031400.469
 398.808 1397.56 408.8131396.068 418.8181396.233 428.8231400.354 438.8281402.675
 456.634  1404.3 468.8431405.667 478.8481405.871 498.8581404.232 528.8721404.786
 558.8871404.017 588.9021406.025 640.9411408.031 698.9561408.932 728.9711409.971
  809.01  1411.8 899.055 1413.491029.1191414.4971079.1431416.1851156.2451419.376
#Mann= 3 , 0 , 0
       0    .035       0 368.794     .07       0 456.634    .035       0
Bank Sta=368.794,456.634
XS Rating Curve= 0 ,0
Exp/Cntr=0.3,0.1

Type RM Length L Ch R = 1 ,56349   ,400.121,499.315,547.433
XS GIS Cut Line= 2
     6257421.121     2212990.223     6257314.613     2213552.586
#Sta/Elev= 30
       01423.104  10.3441421.396  30.6991417.563  34.1331416.752  40.8771414.962
  51.0551411.579  59.8041408.971   71.41    1406 122.2991405.874 132.4771404.293
 163.774 1403.07 222.3891402.018 264.7881401.989 274.9661400.875 285.1431396.469
 295.3211394.915 299.4031395.875 315.6771398.866  325.561399.976 366.5661402.039
 397.0991401.872 407.2771402.413 447.9881405.878  487.661410.231 509.0541413.719
  529.411417.814 539.5881419.122 549.7651420.045 559.9431420.492  572.361420.273
#Mann= 3 , 0 , 0
       0    .035       0 264.788     .07       0  325.56    .035       0
Bank Sta=264.788,325.56
XS Rating Curve= 0 ,0
Exp/Cntr=0.3,0.1

Type RM Length L Ch R = 1 ,55849   ,483.814,499.484,509.926
XS GIS Cut Line= 2
     6257079.224     2212801.961     6256792.619     2213246.493
#Sta/Elev= 30
       0 1414.06  76.8651408.335  98.5681406.141 106.7191404.928 117.108    1404
 129.007 1405.48 134.7381405.624 140.9051405.271 152.8031403.954 192.6111402.099
 279.4211399.919 283.6841399.479 286.6551398.555 295.5821394.886 301.1241394.269
  307.48    1394 315.5921394.254 319.3781394.016 328.1731395.117 337.294 1397.93
 344.5281399.609 351.7631399.948 366.9711400.157 402.6661401.956 414.5641403.851
 426.4631406.605 450.2591409.834 481.9771414.847 510.914 1419.07 528.9151420.492
#Mann= 3 , 0 , 0
       0    .035       0 279.421     .07       0 344.528    .035       0
Bank Sta=279.421,344.528
XS Rating Curve= 0 ,0
Exp/Cntr=0.3,0.1

Type RM Length L Ch R = 1 ,55349   ,501.885,500.002,500.816
XS GIS Cut Line= 6
    6256696.5451    2212526.8543    6256569.2877    2212686.6895
    6256477.0868     2212802.494    6256442.5236    2212845.9052
    6256415.5425    2212879.7936    6256339.4156    2212975.4089
#Sta/Elev= 30
       01415.775  17.2971414.488  55.6441410.823  94.5221407.769 106.7741406.453
 198.3221402.198 283.7191399.887   309.11398.262 312.1851397.864 319.3021395.039
 324.074    1394 336.8571394.167 340.6511394.547 347.7671395.967 354.8841398.251
     3621399.962  393.581401.842 400.7691401.692 404.6991401.039 411.8151400.256
 426.0481401.124 440.2811402.591 451.1411404.956 454.8231404.124 472.0451408.331
 481.2171409.876 511.6931410.561 548.7391410.199 561.4911410.748 580.7251411.987
#Mann= 3 , 0 , 0
       0    .035       0   309.1     .07       0     362    .035       0
Bank Sta=309.1,362
XS Rating Curve= 0 ,0
Exp/Cntr=0.3,0.1

Type RM Length L Ch R = 1 ,54849   ,500.709,500,500.43
XS GIS Cut Line= 6
    6256312.2608    2212206.7801    6256102.3601    2212470.4154
      6256015.49    2212579.5241    6255895.5148    2212730.2131
    6255719.0876    2212951.8055    6255642.9384     2213047.449
#Sta/Elev= 30
       01415.891  30.1741413.542  42.9561413.119  68.5211413.318 119.6511411.059
 131.2781409.896 161.9361404.848  221.911400.012  273.041398.025 306.4281397.988
 324.1691396.791 338.538    1394 362.5171394.185 386.702 1398.16 401.7031399.589
 413.6461399.787 458.6341399.662 490.2761400.446 537.312    1400 545.5391400.807
 552.6561400.432 575.6591401.775 587.9821401.965 595.3541401.483 626.7891401.213
 716.2661405.561 812.7481409.2061005.4051412.8111053.5691414.0731083.2011416.215
#Mann= 3 , 0 , 0
       0    .035       0 306.428     .07       0 386.702    .035       0
Bank Sta=306.428,386.702
XS Rating Curve= 0 ,0
Exp/Cntr=0.3,0.1

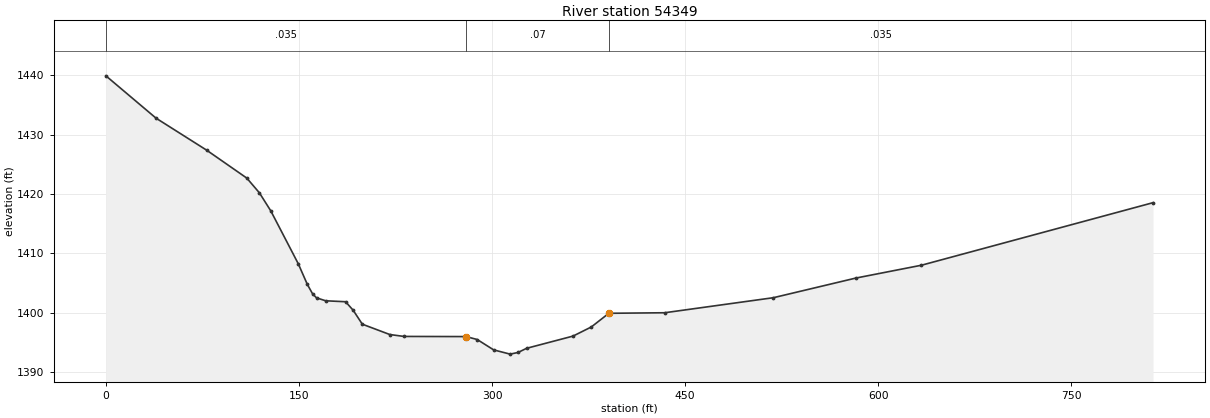
Type RM Length L Ch R = 1 ,54349   ,487.215,499.118,518.069
XS GIS Cut Line= 2
     6255905.662     2211914.732     6255398.978     2212551.128
#Sta/Elev= 30
       01439.926  38.9591432.791  78.2241427.405 109.4861422.691 119.2331420.214
 128.0391417.192 149.3891408.283 156.5051404.771 160.6161403.172 163.622 1402.52
 170.7381402.021 186.1811401.862 192.0871400.429 199.2041398.077 220.5531396.336
 231.6161396.014  279.78 1395.99  288.441395.497 301.2221393.749 314.0051393.034
 320.1831393.314 326.7871394.013 362.8821396.074 377.1151397.614 390.6991399.915
 434.0471400.005 518.5231402.541 582.4351405.843 633.5651408.014 813.4671418.554
#Mann= 3 , 0 , 0
       0    .035       0  279.78     .07       0 390.699    .035       0
Bank Sta=279.78,390.699
XS Rating Curve= 0 ,0
Exp/Cntr=0.3,0.1