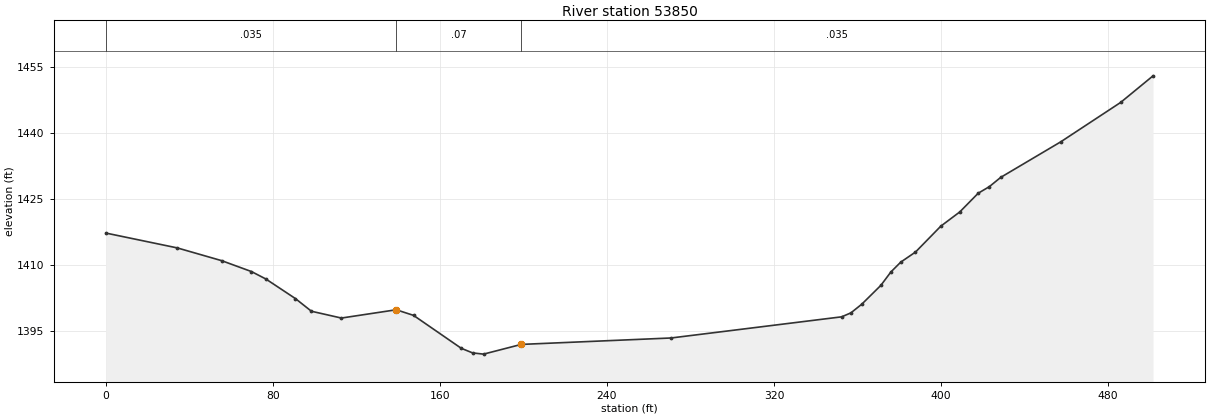
HEC-RAS study R3.prj: San Jacinto Stage III Reach 3

--- R3.g29 (geometry) --- (continued)

Type RM Length L Ch R = 1 ,53850   ,,,
XS GIS Cut Line= 2
     6255511.186     2211651.813     6255151.296     2212001.195
#Sta/Elev= 30
       01417.361  34.2021413.988  55.4171411.097  69.7331408.615  76.6331406.924
  90.7761402.479  98.4461399.599 112.8021398.054  139.081399.936 147.3511398.663
 170.2281391.179 175.6391390.137 180.8911389.857 198.9411392.065 270.7221393.525
 352.4351398.332 356.8611399.232 362.0751401.206 371.2171405.486 376.0121408.525
 380.7221410.754 387.7941413.049  399.931418.935 409.0091422.164 417.824 1426.41
 423.1531427.903 428.6431430.022 457.3551438.085 486.0681447.043 501.5861453.086
#Mann= 3 , 0 , 0
       0    .035       0  139.08     .07       0 198.941    .035       0
Bank Sta=139.08,198.941
XS Rating Curve= 0 ,0
Exp/Cntr=0.3,0.1
Stream Node=SJR Stage III   ,4               , 0 , 0 ,Upstream end
Stream Node=SJR Stage III   ,4               , 0 , 1 ,Downstream end
Stream Node=SJR Stage III   ,2               , 0 , 0 ,Upstream end
Stream Node=SJR Stage III   ,2               , 0 , 1 ,Downstream end
Stream Node=SJR Stage III   ,3               , 0 , 0 ,Upstream end
Stream Node=SJR Stage III   ,3               , 0 , 1 ,Downstream end
Stream Node=SJR Stage III   ,1               , 0 , 0 ,Upstream end
Stream Node=SJR Stage III   ,1               , 0 , 1 ,Downstream end
LCMann Table=0

Chan Stop Cuts=-1
Use User Specified Reach Order=0
Composite Channel Slope=5

--- R3.g33 (geometry) ---

Geom Title=Phase 2 Ultimate
Program Version=5.03
BEGIN GEOM DESCRIPTION:
Reach 3 DS of I-215
Use to establish Reach 2 Rating Curve and also to model Reach 3 - Blocked areas represent where future fill can be placed for development
jcc  7 FEB 2016
END GEOM DESCRIPTION:

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
River Reach=San Jacinto Rive,Reach 3
Reach XY= 30
6278019.500847132232804.372780886277326.145389572231965.21827851
6276912.415510052231701.12700199 6276715.57784632230876.99639316
6276461.071057022230454.678618576276574.470314092230286.19972234
6276681.389613622228995.433370776276924.38802164 2228525.6364486
 6276794.78887072228091.479292936275907.03468673 2227641.1222434
 6275602.48844842227373.127990286274742.957460322227192.02071842
6274339.115848662226951.481179246273468.645432162226900.69073673
6272801.336139292226039.908089856267397.556891182220053.84097189
6264878.000645292217622.123526486264091.635199132217008.74859064
6263650.978637872216780.692726866261526.42189891 2216103.5091418
6260877.894908822215640.12269508 6259919.08898012214126.10505769
6259858.453769192213658.001867156259551.80302887 2213268.1336659
6259245.152293712213137.037626716258857.564003922213145.01738562
6257704.962047682213454.11482541 6256492.95242712212791.20575938
6255869.098236012212327.843921286255367.383659642211762.88202876

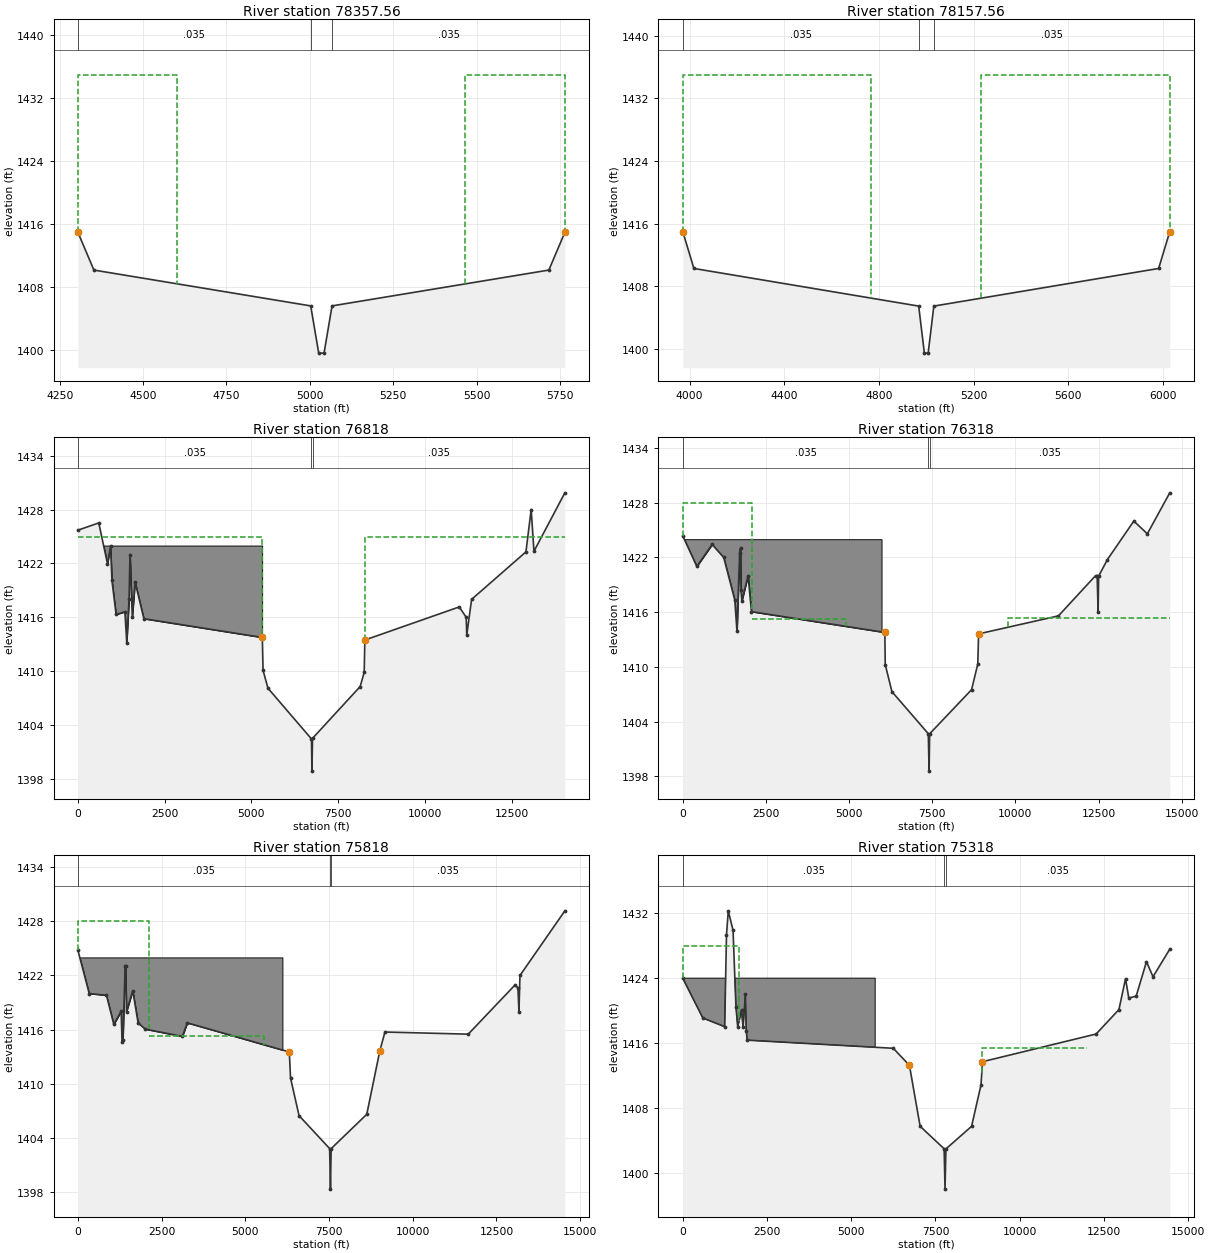
Type RM Length L Ch R = 1 ,78357.56,200,200,200
XS GIS Cut Line= 2
     6273961.869     2226354.717     6272821.488     2227266.527
#Sta/Elev= 8
  4304.5    1415  4352.5  1410.2  5002.5 1405.65  5026.5 1399.65  5042.5 1399.65
  5066.5 1405.65  5716.5  1410.2  5764.5    1415
#Mann= 3 ,-1 , 0
  4304.5    .035       0  5002.5     .07       0  5066.5    .035       0
#XS Ineff= 2 , 0
    34.5  4602.5    1435  5466.5    34.5    1435
Permanent Ineff=
       F       F
Bank Sta=4304.5,5764.5
XS Rating Curve= 0 ,0
Exp/Cntr=0.3,0.1

Type RM Length L Ch R = 1 ,78157.56,20,20,20
XS GIS Cut Line= 5
     6277186.039     2223497.061     6273359.222     2226584.527
     6273188.769     2226716.875     6269507.342     2229659.431
     6268619.748     2230609.156
#Sta/Elev= 8
    3971    1415    4018  1410.3    4968  1405.5    4992  1399.5    5008  1399.5
    5032  1405.5    5982  1410.3    6029    1415
#Mann= 3 ,-1 , 0
    3971    .035       0    4968     .07       0    5032    .035       0
#XS Ineff= 2 , 0
       0    4768    1435    5232       0    1435
Permanent Ineff=
       F       F
Bank Sta=3971,6029
XS Rating Curve= 0 ,0
Exp/Cntr=0.3,0.1

Type RM Length L Ch R = 1 ,76818   ,500.841,500,500.043
XS GIS Cut Line= 6
    6277476.6081    2221151.8251    6272451.3577    2225592.4073
    6272437.5322    2225604.6244    6272413.0807    2225626.2309
    6267155.8005    2230271.8474    6267006.7539    2230403.5529
#Sta/Elev= 30
       01425.711 601.9011426.521 852.8181421.975 941.0941423.914 981.1281420.108
1101.2321416.3141354.783 1416.621408.1631413.1881474.887    14181501.577    1423
1568.301    1416 1648.371419.9411901.9211415.8445316.0811413.7565337.3341410.088
5479.0251408.0946732.989 1402.446746.0941398.8526763.4651402.5098136.9881408.283
8252.3551409.8628271.5951413.46910992.061417.15611192.93    141611208.03    1414
11348.36    141812914.541423.29513065.56 1428.0113145.761423.36214036.861429.876
#Mann= 3 ,-1 , 0
       0    .035       06732.989     .07       06763.465    .035       0
#XS Ineff= 2 , 0
       05313.685    14258278.265       0    1425
Permanent Ineff=
       F       F
#Block Obstruct= 2 , 0
       0    5311    1424    8803       0    1424
Bank Sta=5316.081,8271.595
XS Rating Curve= 0 ,0
Exp/Cntr=0.3,0.1

Type RM Length L Ch R = 1 ,76318   ,500.841,500,500.043
XS GIS Cut Line= 6
      6277632.23    2220345.0092    6275110.5665    2222575.3457
    6273203.7003    2224260.3554    6272252.1557    2225101.1917
    6272086.0613    2225247.9615    6266746.3671    2229966.4034
#Sta/Elev= 30
       01424.358 422.3761421.014 882.8591423.4211230.733    14221563.0911417.343
1629.8431413.9061709.9441422.4531736.644    14231749.9951418.4121776.6951417.219
1963.598    14202065.9441416.0576075.7591413.7796087.7181410.2586288.7531407.281
7382.1671402.6757406.2911398.5687422.2011402.6588683.461  1407.58870.6271410.321
8894.5051413.618 11295.71415.59412409.931419.99712458.55    142012488.751416.043
12503.851419.94612767.321421.76413560.981425.98513968.351424.593 14642.31429.085
#Mann= 3 ,-1 , 0
       0    .035       07382.167     .07       07422.201    .035       0
#XS Ineff= 3 ,-1
       0    2074    1428    2074    4914  1415.3    9770   15000  1415.4
Permanent Ineff=
       T       T       T
#Block Obstruct= 2 , 0
       0    5976    1424    9267       0    1424
Bank Sta=6075.759,8894.505
XS Rating Curve= 0 ,0
Exp/Cntr=0.3,0.1

Type RM Length L Ch R = 1 ,75818   ,500.841,500,500.043
XS GIS Cut Line= 6
    6277400.9622    2219887.2207    6276802.7563    2220412.7941
    6268628.6081    2227635.9124    6267610.4083    2228535.6485
     6267584.743    2228558.3279    6266588.6342    2229438.5433
#Sta/Elev= 30
       01424.796 338.115    1420 853.0611419.8051071.8451416.5881291.8641418.036
1318.554 1414.631345.2441414.8441411.968    14231425.313    14231452.002    1418
 1638.831420.3081798.968 1416.732015.9051416.0543120.106 1415.253266.8991416.755
6314.4071413.5266350.1421410.6536604.8731406.475 7518.411402.8287543.1891398.337
7563.9341402.824 8627.441406.6259017.0911413.6549170.2021415.73611657.52  1415.5
13051.381420.93413141.991420.625 13172.2    1418 13202.4    142214543.691429.159
#Mann= 3 ,-1 , 0
       0    .035       0 7518.41     .07       07563.934    .035       0
#XS Ineff= 3 ,-1
       0    2135    1428    2135    5563  1415.3    9418   14000  1415.4
Permanent Ineff=
       T       T       T
#Block Obstruct= 2 , 0
       0    6108    1424    9161       0    1424
Bank Sta=6314.407,9017.091
XS Rating Curve= 0 ,0
Exp/Cntr=0.3,0.1

Type RM Length L Ch R = 1 ,75318   ,500.841,500,500.043
XS GIS Cut Line= 6
6277243.476495732219356.10864324    6276196.6814    2220281.1131
    6275931.9347    2220515.0577    6275854.2341     2220583.718
    6275507.9727    2220889.6934    6266443.7792    2228899.3036
#Sta/Elev= 30
       01423.989 595.4321419.0991243.8461418.0321297.2251429.2981350.604 1432.28
1492.2581429.8821577.4661420.5011630.846    14181743.1751420.0491790.9841417.958
1857.708    14221884.3971417.4951911.0871416.3756248.1561415.3756726.7921413.277
7043.9311405.785 7756.271403.0177782.8121398.0557809.501    1403 8570.461405.776
8851.1881410.8828893.4381413.72412266.981417.131 12943.81420.13513140.121423.924
13236.261421.56313454.671421.781 13761.61426.02413955.621424.17314452.351427.563
#Mann= 3 ,-1 , 0
       0    .035       0 7756.27     .07       07809.501    .035       0
#XS Ineff= 3 ,-1
       0    1670    1428    1670 6017.18  1415.3 8872.18   12000  1415.4
Permanent Ineff=
       T       T       T
#Block Obstruct= 2 , 0
       0    5710    1424    8591       0    1424
Bank Sta=6726.792,8893.438
XS Rating Curve= 0 ,0
Exp/Cntr=0.3,0.1

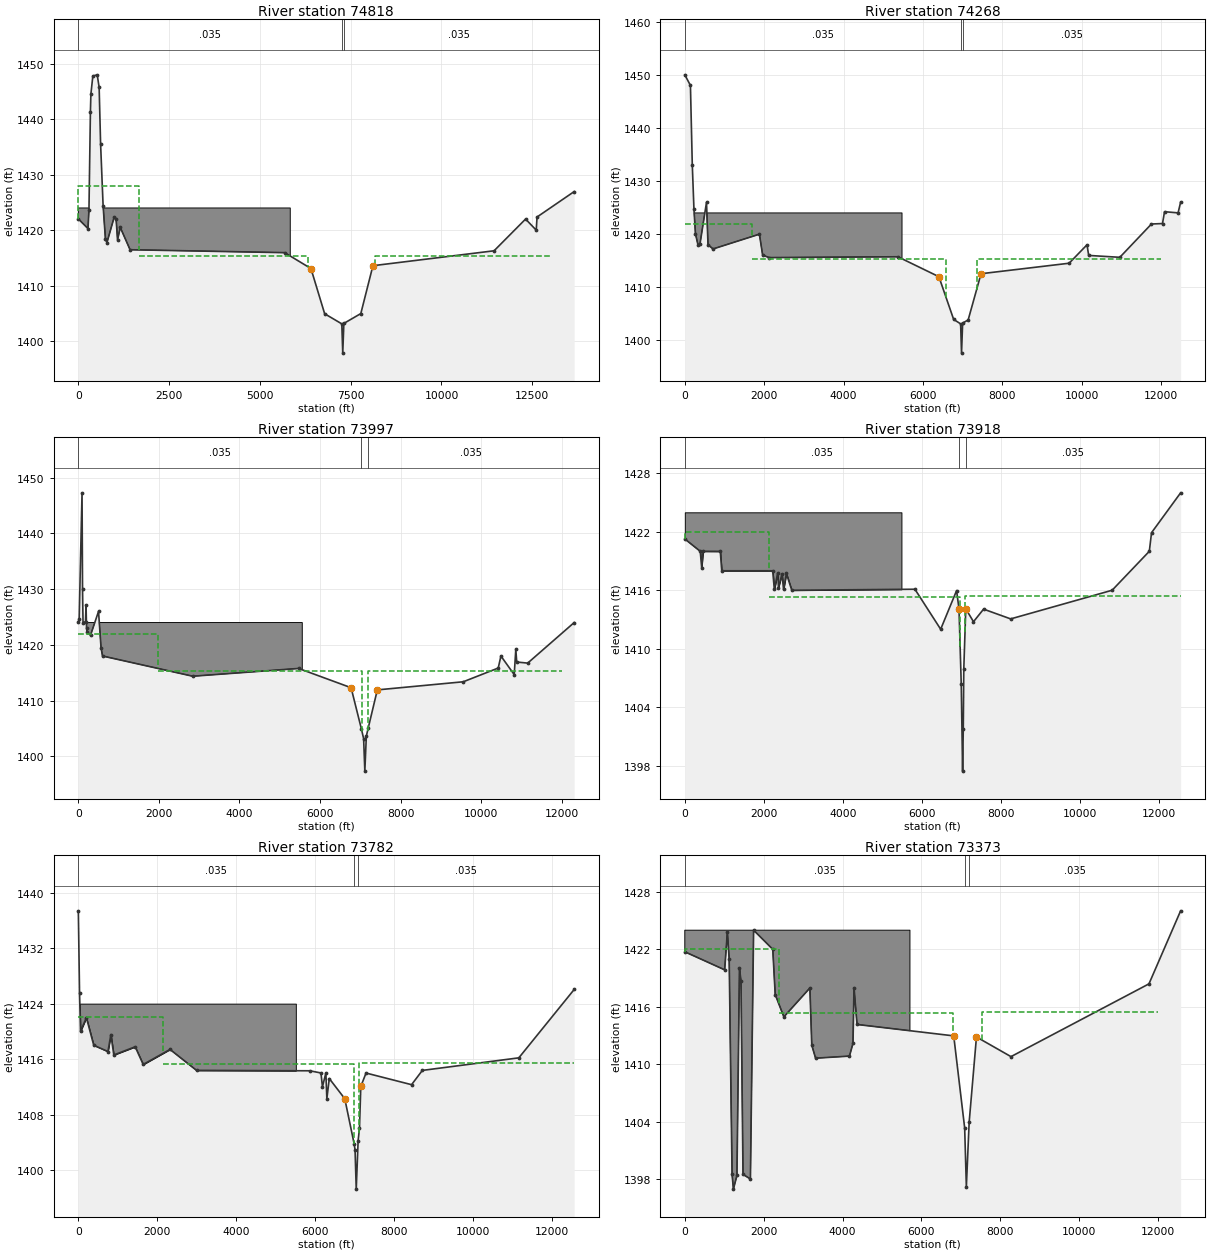
Type RM Length L Ch R = 1 ,74818   ,270,550,790
XS GIS Cut Line= 2
     6276530.736     2219318.683      6266298.93     2228360.059
#Sta/Elev= 30
       01422.031 266.0161420.281 292.7061423.641  332.741441.297 346.0851444.547
 399.4651447.782 519.568    1448 572.947 1445.76 612.9821435.544 682.1561424.415
  746.43 1418.39 787.8691417.753 985.4911422.3051040.016    14221080.051 1418.26
 1155.521420.4821424.7321416.4715682.5421415.9436405.7651413.0836783.3121404.933
7255.3121403.1097281.6731397.8337311.8771403.1877779.1541404.9658112.7751413.592
11448.981416.281 12316.4    142212609.98    142012632.481422.37113654.171426.953
#Mann= 3 ,-1 , 0
       0    .035       07255.312     .07       07311.877    .035       0
#XS Ineff= 3 ,-1
       0    1670    1428    1670    6324  1415.3    8178   13000  1415.4
Permanent Ineff=
       T       T       T
#Block Obstruct= 2 , 0
       0    5836    1424    8623       0    1424
Bank Sta=6405.765,8112.775
XS Rating Curve= 0 ,0
Exp/Cntr=0.3,0.1

Type RM Length L Ch R = 1 ,74268   ,122,271,370
XS GIS Cut Line= 2
     6276213.599     2219458.017     6266340.809     2227116.229
#Sta/Elev= 30
       01449.993 142.002    1448 188.5681433.089 230.5931424.726  268.561420.084
 331.839    1418 382.4631418.149 546.988    1426 584.9551418.024 711.5131417.219
1880.155    14201961.7331416.0512124.8891415.5945368.848 1415.756403.5411411.996
6774.825 1403.966950.8231403.1226973.7221397.6127001.4461403.268 7140.661403.857
7465.5031412.5589684.4771414.53110135.83    141810178.05    141610962.711415.646
11760.031421.91512038.46    142212089.081424.23212430.791424.01112494.811426.023
#Mann= 3 ,-1 , 0
       0    .035       06950.823     .07       07001.446    .035       0
#XS Ineff= 3 ,-1
       0    1706    1422    1706 6593.72  1415.3 7353.72   12000  1415.4
Permanent Ineff=
       T       T       T
#Block Obstruct= 2 , 0
       0    5474    1424    8430       0    1424
Bank Sta=6403.541,7465.503
XS Rating Curve= 0 ,0
Exp/Cntr=0.3,0.1

Type RM Length L Ch R = 1 ,73997   ,79,79,79
BEGIN DESCRIPTION:
Cut Upstream of BNSF Railroad
jcc  14 DEC 2009
END DESCRIPTION:
XS GIS Cut Line= 2
     6276265.564     2219315.089     6266341.885     2226595.725
#Sta/Elev= 30
       01424.109  21.0791424.641  91.9891447.273 104.3911429.949 116.794    1424
 178.0061424.162  191.211427.173 203.6131423.098 216.0151422.305 302.8341421.729
 501.277    1426  563.291419.522 600.498    14182839.7651414.3735469.3111415.768
6771.0051412.3117025.0791404.9617082.1011403.1747111.8981397.3497149.106 1403.62
7193.634 1405.017421.9641411.9229555.2231413.37810423.411415.84410490.13    1418
10820.291414.65910859.431419.18910882.311416.91711155.171416.72912308.01    1424
#Mann= 3 ,-1 , 0
       0    .035       07025.079     .07       07193.634    .035       0
#XS Ineff= 3 ,-1
       0    1979    1422    1979  7042.8  1415.3  7181.2   12000  1415.4
Permanent Ineff=
       T       T       T
#Block Obstruct= 2 , 0
       0    5559    1424    8569       0    1424
Bank Sta=6771.005,7421.964
XS Rating Curve= 0 ,0
Exp/Cntr=0.5,0.3

Type RM Length L Ch R = 1 ,73918   ,136,136,136
BEGIN DESCRIPTION:
Copy of Section 73782
Upstream of Case Road Bridge and Downstream of BNSF Bridge
jcc  14 DEC 2009
END DESCRIPTION:
XS GIS Cut Line= 2
     6276155.702     2219298.933     6266032.209     2226726.123
#Sta/Elev= 30
       01421.269 391.276    1420 427.0311418.335 464.239    1420 898.3741419.992
 935.539    14182225.414    14182267.7511416.0812352.2781417.7692372.103 1416.28
2461.0641417.6652500.8751416.0852572.0451417.7292709.117    14165827.4981416.105
 6479.52    14126882.8691415.9696943.5261414.0827000.7581406.3337035.0151397.438
 7051.921401.7337065.1451407.9497115.2231414.0997310.4971412.7717565.9271414.064
8252.1881413.06210821.011416.00111763.05    142011819.181421.90812555.81    1426
#Mann= 3 ,-1 , 0
       0    .035       06943.526     .07       07115.223    .035       0
#XS Ineff= 3 ,-1
       0    2143    1422    2143    6972  1415.3    7096   14000  1415.4
Permanent Ineff=
       T       T       T
#Block Obstruct= 2 , 0
       0    5486    1424    8481       0    1424
Bank Sta=6943.526,7115.223
XS Rating Curve= 0 ,0
Exp/Cntr=0.5,0.3

Type RM Length L Ch R = 1 ,73782   ,618,409,265
BEGIN DESCRIPTION:
Cut Downstream of Case Road
END DESCRIPTION:
XS GIS Cut Line= 2
     6276076.022     2219188.714     6265951.617     2226616.616
#Sta/Elev= 30
       01437.383  30.5431425.602  55.349    1420 204.1811421.975 390.221    1418
 749.898 1417.09 824.3141419.527  898.731416.5931439.7621417.7771642.6241415.223
2322.4091417.3962994.7811414.3715859.7971414.3156145.058    14146182.2661411.998
6269.085    1414 6293.89 1410.296355.9031413.1936747.9721410.2836988.4391403.691
7008.2951402.869 7038.051397.2477086.0741404.2297119.8851406.0117153.6951412.048
7286.104 1413.99  8439.1 1412.31 8712.411414.36911155.741416.18112556.961426.038
#Mann= 3 ,-1 , 0
       0    .035       06988.439     .07       07086.074    .035       0
#XS Ineff= 3 ,-1
       0    2143    1422    2143 6984.18  1415.3 7108.18   14000  1415.4
Permanent Ineff=
       T       F       F
#Block Obstruct= 2 , 0
       0    5508    1424    8468       0    1424
Bank Sta=6747.972,7153.695
XS Rating Curve= 0 ,0
Exp/Cntr=0.5,0.3

Type RM Length L Ch R = 1 ,73373   ,900,556,295
XS GIS Cut Line= 2
     6275715.067     2218593.054     6265887.981     2226430.734
#Sta/Elev= 30
       01421.7421011.1531419.8551079.1411423.8191125.0051420.9821198.549  1398.5
1232.6331396.945 1322.171398.3761386.125    14201424.4991418.7081475.6631398.486
1663.642    13981744.274    14242230.332    14222291.9911417.2752511.7351414.941
3171.1861417.9583219.2991411.9793315.5261410.6254174.5661410.8444264.1041412.179
4289.6861417.9924366.4321414.149 6817.621412.9577095.1351403.339 7137.831397.197
7208.9871403.9347393.9981412.8438269.2371410.789 11767.41418.39212569.841426.022
#Mann= 3 ,-1 , 0
       0    .035       07095.135     .07       07208.987    .035       0
#XS Ineff= 3 ,-1
       0    2382    1422    2382    6806  1415.3    7537   12000  1415.4
Permanent Ineff=
       T       F       F
#Block Obstruct= 2 , 0
       0    5708    1424    8507       0    1424
Bank Sta=6817.62,7393.998
XS Rating Curve= 0 ,0
Exp/Cntr=0.3,0.1

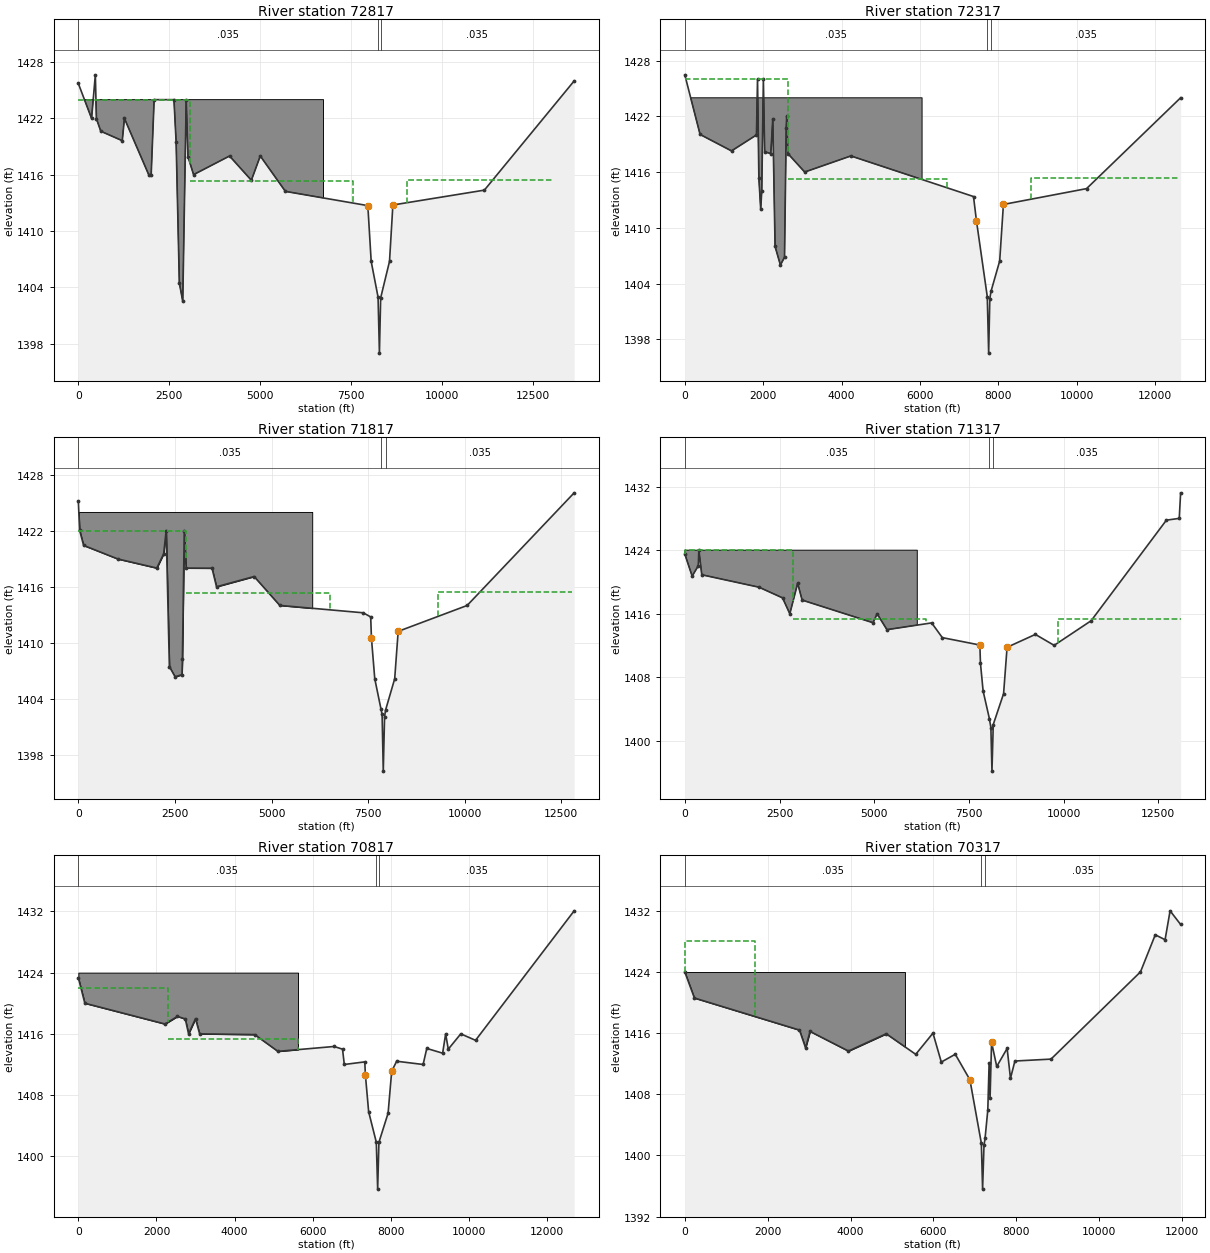
Type RM Length L Ch R = 1 ,72817   ,500.397,500,500.121
XS GIS Cut Line= 6
    6275857.4419    2217044.5198    6273400.7516    2219296.0591
    6269761.1881    2222631.5016    6269754.4644    2222637.6633
    6269661.5136    2222722.84736265848.183051432226217.53663142
#Sta/Elev= 30
       01425.725 363.893    1422 467.4961426.646 497.0971421.969  617.121420.634
1207.5191419.625 1266.72    1422 1934.331416.0012002.184    14162083.572    1424
2628.362    14242687.5641419.5162776.3661404.4562870.313  1402.52965.265    1424
3013.1741417.933 3167.541416.007 4156.011417.9934755.7431415.406 5000.941417.996
5691.6691414.2217956.6691412.7068048.7921406.7648237.8871402.9518275.2811396.983
8309.5511402.872 8552.571406.7618645.1971412.77211160.061414.356 13627.61425.996
#Mann= 3 ,-1 , 0
       0    .035       08237.887     .07       08309.551    .035       0
#XS Ineff= 3 ,-1
       0    3079    1424    3079    7555  1415.3    902313056.47  1415.4
Permanent Ineff=
       T       F       F
#Block Obstruct= 2 , 0
       0    6739    1424    9597       0    1424
Bank Sta=7956.669,8645.197
XS Rating Curve= 0 ,0
Exp/Cntr=0.3,0.1

Type RM Length L Ch R = 1 ,72317   ,500.397,500,500.121
XS GIS Cut Line= 6
    6275128.8969    2217034.1096    6269419.8493    2222266.1105
    6269310.9003    2222365.9556    6266817.9029    2224650.6387
    6266528.6258     2224915.744     6265849.151    2225538.4419
#Sta/Elev= 30
       01426.473 389.9711420.0541191.7421418.2831827.771    1420  1854.91426.019
1889.0061415.3871936.285    14121963.4131414.0072004.105    14262037.0151418.179
2194.004    14182244.2281421.7362302.517    1408 2438.371406.0012543.5991406.832
2587.3641420.7752599.449    14222629.052    14183058.2781416.0094235.1891417.742
7363.5711413.3737439.3491410.7467714.6141402.6137750.1681396.519 7779.571402.385
7809.4721403.1568031.3961406.4368126.4971412.52210246.821414.224 12646.41424.004
#Mann= 3 ,-1 , 0
       0    .035       07714.614     .07       07809.472    .035       0
#XS Ineff= 3 ,-1
       0    2637    1426    2637    6692  1415.3    882612587.19  1415.4
Permanent Ineff=
       T       F       F
#Block Obstruct= 2 , 0
       0    6052    1424    9024       0    1424
Bank Sta=7439.349,8126.497
XS Rating Curve= 0 ,0
Exp/Cntr=0.3,0.1

Type RM Length L Ch R = 1 ,71817   ,500.397,500.004,500.121
BEGIN DESCRIPTION:
Blocked obstruction is EMWD WWTP.
jcc  20 AUG 2009
END DESCRIPTION:
XS GIS Cut Line= 6
     6274897.156    2216568.2786     6268837.788    2222121.3272
     6266479.211    2224282.8219    6265509.8915    2225171.1454
    6265500.7718    2225179.5029    6265487.3615    2225191.7927
#Sta/Elev= 30
       01425.185  32.7211422.051 136.3271420.4231024.382 1418.972030.844    1418
2208.4551419.5242273.027    14222356.4641407.4592504.4741406.3752682.0841406.604
 2693.571408.2432741.288    14222788.465    14183459.5281417.985 3575.97    1416
4549.5071417.0965213.0411414.0087373.9751413.2177566.3871412.7737585.8771410.506
 7671.561406.1717832.8031402.9247861.4581402.3547892.0071396.2897925.6111402.104
 7951.211402.8158187.6591406.1698277.2041411.23110062.22    141412832.071426.044
#Mann= 3 ,-1 , 0
       0    .035       07832.803     .07       0 7951.21    .035       0
#XS Ineff= 4 ,-1
       0    2777    1422    2777    6503  1415.3    930312763.59  1415.4
Permanent Ineff=
       T       F       F       F
#Block Obstruct= 2 , 0
       0    6053    1424    9119       0    1424
Bank Sta=7585.877,8277.204
XS Rating Curve= 0 ,0
Exp/Cntr=0.3,0.1

Type RM Length L Ch R = 1 ,71317   ,495.606,499.985,508.776
XS GIS Cut Line= 6
    6274714.5628    2216057.4067    6274442.6697    2216306.5805
    6274417.9132    2216329.2682    6269825.6327    2220537.8189
    6269666.6179    2220683.5463    6265124.4031    2224846.2147
#Sta/Elev= 30
       01423.522 194.1941420.735 356.9641422.039 370.5281424.041 448.4371420.906
1957.8191419.3432580.6641417.9992772.181    14162979.3931419.8343097.3431417.721
4968.7761414.875 5077.291415.992 5335.92    14146516.8121414.8526798.029    1413
7789.691 1412.077804.492 1409.797874.8481406.2818041.3061402.7948080.1041401.663
8108.4151396.2078142.7881402.0718415.441 1405.958507.4531411.7849254.2011413.406
9749.9441412.028 10726.81415.12512713.061427.77513052.16    142813088.781431.214
#Mann= 3 ,-1 , 0
       0    .035       08041.306     .07       08142.788    .035       0
#XS Ineff= 3 ,-1
       0    2862    1424    2862    6379  1415.3    9847   14000  1415.4
Permanent Ineff=
       T       F       F
#Block Obstruct= 2 , 0
       0    6137    1424    9280       0    1424
Bank Sta=7789.691,8507.453
XS Rating Curve= 0 ,0
Exp/Cntr=0.3,0.1

Type RM Length L Ch R = 1 ,70817   ,500.661,500.005,500.027
XS GIS Cut Line= 6
    6274105.4658    2216057.4067    6273559.9997    2216545.8269
    6271992.4237    2217949.4632    6271991.0083    2217950.7307
    6271758.6536    2218158.7852    6264680.1111     2224497.042
#Sta/Elev= 30
       0 1423.33  166.54    14202220.2611417.2872537.9071418.2812738.5761417.945
2822.732    14163000.6041417.986 3106.18    14164515.5971415.9065110.9871413.713
6548.5971414.3516765.307    14146810.279    14127334.957 1412.347349.9471410.685
7433.8251405.8257629.7371401.8547664.7531395.7197696.8531401.8357931.6661405.633
8024.165 1411.128151.2031412.4248828.722    14128922.6831414.0969328.3621413.476
9405.911    14169473.026    14149793.076    141610171.021415.15612696.27 1432.07
#Mann= 3 ,-1 , 0
       0    .035       07629.737     .07       07696.853    .035       0
#XS Ineff= 3 ,-1
       0    2304    1422    2304    5613  1415.3    9748   12000  1415.4
Permanent Ineff=
       T       F       F
#Block Obstruct= 2 , 0
       0    5626    1424    8821       0    1424
Bank Sta=7349.947,8024.165
XS Rating Curve= 0 ,0
Exp/Cntr=0.3,0.1

Type RM Length L Ch R = 1 ,70317   ,500.661,500,500.027
XS GIS Cut Line= 6
    6273413.7322    2216005.6467    6269080.6305    2219885.5853
    6268048.6346    2220809.6535    6268046.1537    2220811.8748
    6265310.5989    2223261.3407    6264531.8918    2223958.6094
#Sta/Elev= 30
       0    1424 231.9661420.5952768.278  1416.42915.3151414.0613023.3151416.225
3949.5861413.6554862.2691415.9185573.6881413.2295989.802    14166191.1471412.216
6528.0931413.2376881.4611409.9047157.6521401.5937187.6871395.5967221.3891401.318
 7247.651402.2567313.453 1405.947345.177 1412.057367.8641407.4857404.3241414.804
7528.9141411.6387780.168    14147860.7061410.0877967.6091412.3548838.9281412.603
10998.881424.01611355.521428.866 11592.31428.21811713.11    143211967.481430.217
#Mann= 3 ,-1 , 0
       0    .035       07157.652     .07       0 7247.65    .035       0
#XS Ineff= 1 ,-1
       0    1706    1428
Permanent Ineff=
       T
#Block Obstruct= 2 , 0
       0    5313    1424    8398       0    1424
Bank Sta=6881.461,7404.324
XS Rating Curve= 0 ,0
Exp/Cntr=0.3,0.1

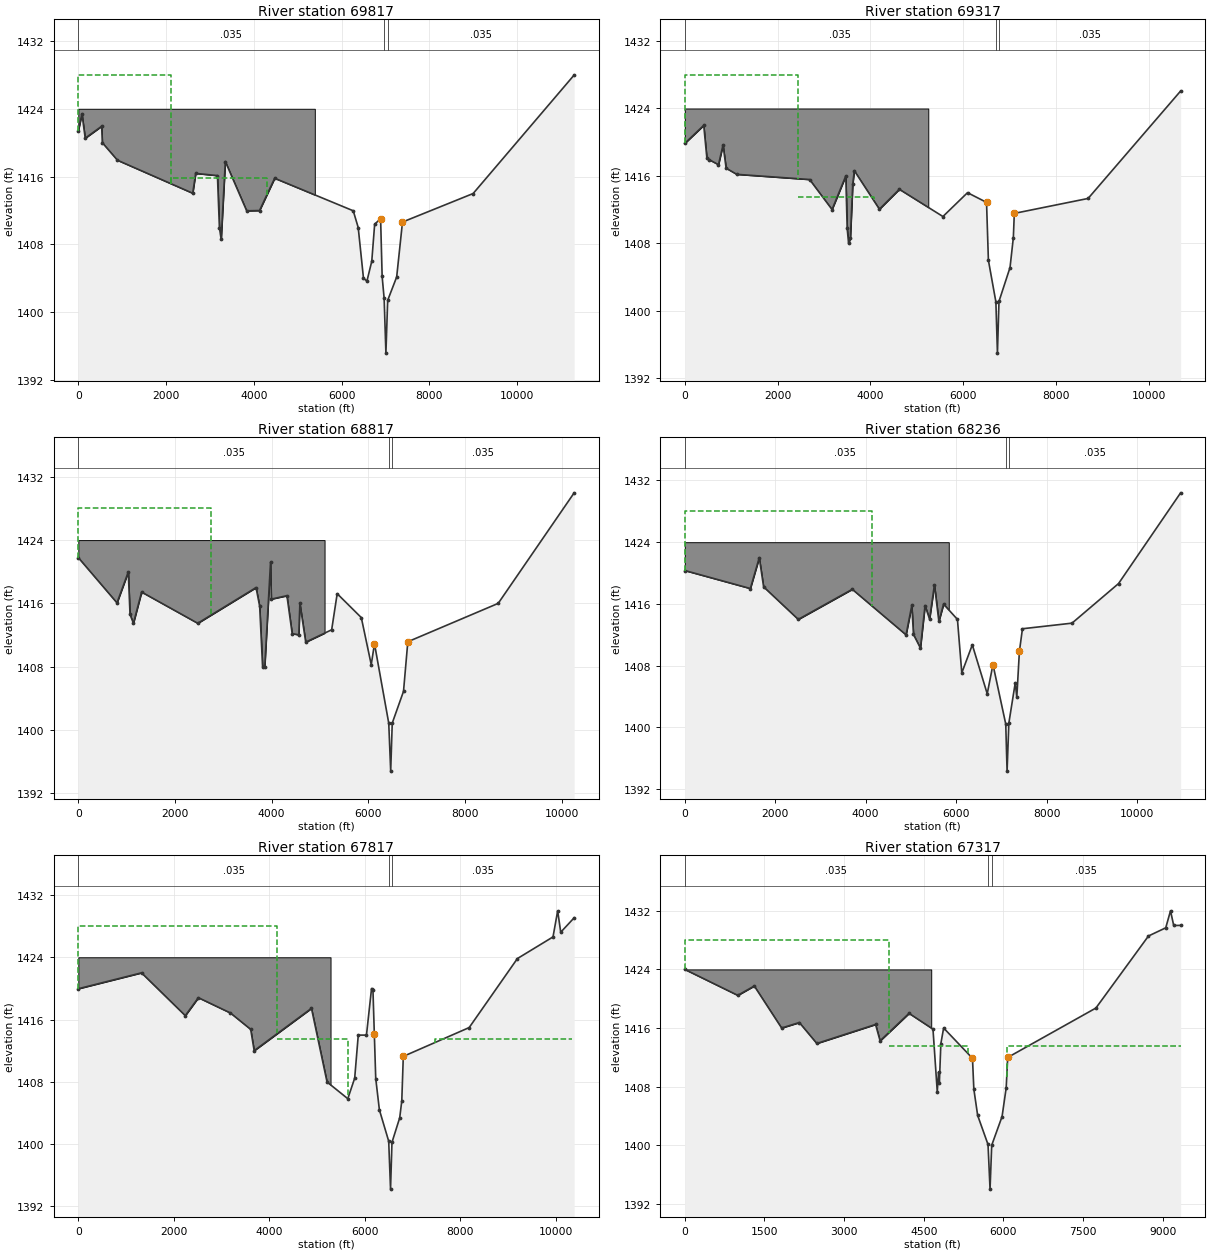
Type RM Length L Ch R = 1 ,69817   ,500.661,500.002,500.027
XS GIS Cut Line= 6
    6272943.2486    2215755.7755    6270994.7448    2217500.5014
    6270193.8444    2218217.6423    6270085.1804    2218314.9422
    6269209.1478    2219099.3577    6264575.4207    2223248.4819
#Sta/Elev= 30
       01421.401  82.4771423.413 156.8191420.531 531.5891421.938 546.579    1420
 891.3671417.9312606.5521414.0392674.4251416.3793169.9661416.1223214.938    1410
3255.1341408.5973349.8551417.781 3836.391411.9694129.375    14124474.1631415.806
6264.9091411.9716377.992    14106497.9181404.0346576.5091403.673 6687.151406.024
6752.7611410.3856888.4951411.0426923.5191404.2296969.0331401.6357009.3021395.191
7049.5711401.4127254.6251404.1687387.2311410.6448997.1711414.00711299.281427.979
#Mann= 3 ,-1 , 0
       0    .035       06969.033     .07       07049.571    .035       0
#XS Ineff= 2 ,-1
       0    2113    1428    2113    4298 1415.85
Permanent Ineff=
       T       F
#Block Obstruct= 2 , 0
       0    5389    1424    8272       0    1424
Bank Sta=6888.495,7387.231
XS Rating Curve= 0 ,0
Exp/Cntr=0.3,0.1

Type RM Length L Ch R = 1 ,69317   ,500.661,500,500.027
XS GIS Cut Line= 6
    6272405.3835    2215566.2388    6270968.3818    2216852.9566
    6270895.7975    2216917.9498    6267536.6199    2219925.8191
    6267261.3017    2220172.3439    6264476.1754    2222666.1971
#Sta/Elev= 30
       01419.858 408.043    1422 475.1591418.147 528.8511417.911 725.7741417.323
 824.1571419.674 890.6731416.9081119.4631416.1792689.5661415.5633173.185    1412
3469.0861415.9883499.0681409.771 3529.05    14083567.9181408.5753618.9941415.005
  3652.91416.6154193.3341412.0414623.3761414.4055562.4821411.1676092.473    1414
6502.0931412.8476542.3621405.9666703.4381401.0316737.0761394.9386770.5541401.092
7008.349 1405.117080.1691408.6747100.4131411.5388690.9321413.31310684.551426.078
#Mann= 3 ,-1 , 0
       0    .035       06703.438     .07       06770.554    .035       0
#XS Ineff= 2 ,-1
       0    2429    1428    2429    4087  1413.5
Permanent Ineff=
       T       T
#Block Obstruct= 2 , 0
       0    5247    1424    8056       0    1424
Bank Sta=6502.093,7100.413
XS Rating Curve= 0 ,0
Exp/Cntr=0.3,0.1

Type RM Length L Ch R = 1 ,68817   ,587.366,581.311,564.226
XS GIS Cut Line= 6
    6271867.5185    2215376.7022    6268446.0672    2218440.3323
     6267313.766    2219454.2157    6267027.5635    2219710.4865
    6266914.9734    2219811.3019    6264250.8034    2222196.8485
#Sta/Elev= 30
       01421.783 800.0331416.0631033.8091419.975 1069.751414.6011140.0361413.483
 1309.721417.4322471.4191413.4843678.263    14183753.2171415.625 3813.18    1408
3858.152    14083978.0781421.2033993.0691416.5394317.0071416.9724426.0021412.169
4562.7191412.0294585.468    14164706.2751411.0995243.1951412.663 5357.231417.226
5856.5311414.202    60621408.2546129.1151410.9016424.4211400.851 6464.691394.789
 6496.681400.8626729.8461404.8756819.0141411.149  8689.5    141610261.591429.979
#Mann= 3 ,-1 , 0
       0    .035       06424.421     .07       0 6496.68    .035       0
#XS Ineff= 2 ,-1
       0    2745    1428    2745    4392  1413.5
Permanent Ineff=
       T       T
#Block Obstruct= 2 , 0
       0    5096    1424    7842       0    1424
Bank Sta=6129.115,6819.014
XS Rating Curve= 0 ,0
Exp/Cntr=0.3,0.1

Type RM Length L Ch R = 1 ,68236   ,440.603,418.742,376.128
XS GIS Cut Line= 6
    6271854.9762    2214400.7357    6270100.0362    2216040.1783
    6270021.4155    2216113.6248     6270009.351    2216124.8955
      6269725.97    2216390.2589    6263897.9128    2221847.7668
#Sta/Elev= 30
       01420.3321449.715    14181647.062    14221742.7751418.218 2509.17    1414
3704.1221417.8994892.967    14125020.8331415.8135057.3671412.0475211.025 1410.29
5313.4361415.7985413.5651414.0315520.7921418.4875619.0641413.7465723.0791415.981
6030.062    14146125.961 1407.07 6358.861410.7066688.6671404.365 6815.591408.152
 7098.311400.441 7127.571394.3477167.1561400.5797308.9261405.8027342.721 1403.91
7399.9831409.8437467.6461412.7898563.6421413.5149592.7641418.642 10965.91430.396
#Mann= 3 ,-1 , 0
       0    .035       0 7098.31     .07       07167.156    .035       0
#XS Ineff= 2 ,-1
       0    4150    1428    4150    5742  1413.5
Permanent Ineff=
       T       F
#Block Obstruct= 2 , 0
       0    5838    1424    8557       0    1424
Bank Sta=6815.59,7399.983
XS Rating Curve= 0 ,0
Exp/Cntr=0.3,0.1

Type RM Length L Ch R = 1 ,67817   ,494.922,499.973,511.295
XS GIS Cut Line= 6
    6270845.6578    2214251.3503    6269675.7065    2215424.9974
    6269663.8418    2215437.6703    6267902.4543    2217319.0645
    6267847.6979    2217377.5514    6263748.7983    2221755.7168
#Sta/Elev= 30
       01419.9581323.335    14222239.896  1416.52513.8671418.8093185.0941416.844
3609.7491414.7363682.677    14124882.4871417.4385208.5651407.9785643.343 1405.83
5787.8151408.468 5862.82    14146034.388    14146140.8251419.9866170.089 1419.83
6199.3531414.0946228.616 1408.426305.1751404.3936500.1381400.3686538.6471394.209
6568.6311400.2176730.8641403.3816774.1781405.5556805.7581411.2658185.6181414.969
9195.2151423.8349941.4381426.61810038.991429.96910102.921427.21910384.191429.075
#Mann= 3 ,-1 , 0
       0    .035       06500.138     .07       06568.631    .035       0
#XS Ineff= 3 ,-1
       0    4170    1428    4170    5645  1413.5    7468   10329  1413.5
Permanent Ineff=
       T       T       T
#Block Obstruct= 2 , 0
       0    5282    1424    7971       0    1424
Bank Sta=6199.353,6805.758
XS Rating Curve= 0 ,0
Exp/Cntr=0.3,0.1

Type RM Length L Ch R = 1 ,67317   ,250,250,250
XS GIS Cut Line= 2
     6269983.315     2214531.662     6263478.697     2221233.914
#Sta/Elev= 30
       0    1424 997.587 1420.461308.7491421.7381823.731    14162157.3721416.749
2486.7921413.888  3593.51416.4833678.554 1414.254224.181    14184674.9541415.846
4755.4481407.3224781.0321409.9844795.1761408.4544823.4631413.8774875.537    1416
5419.0091411.8635444.6611407.6485516.5051404.0635711.6481400.0955749.876    1394
5781.3241399.9935976.4171403.9166053.9671407.8326082.2541411.9797744.1411418.728
8734.2011428.5649059.5071429.6819149.177    1432 9209.38    14309339.7131430.011
#Mann= 3 ,-1 , 0
       0    .035       05711.648     .07       05781.324    .035       0
#XS Ineff= 3 ,-1
       0    3843    1428    3843    5331  1413.5    6064 9339.97  1413.5
Permanent Ineff=
       T       T       T
#Block Obstruct= 2 , 0
       0    4642    1424    7131       0    1424
Bank Sta=5419.009,6082.254
XS Rating Curve= 0 ,0
Exp/Cntr=0.3,0.1

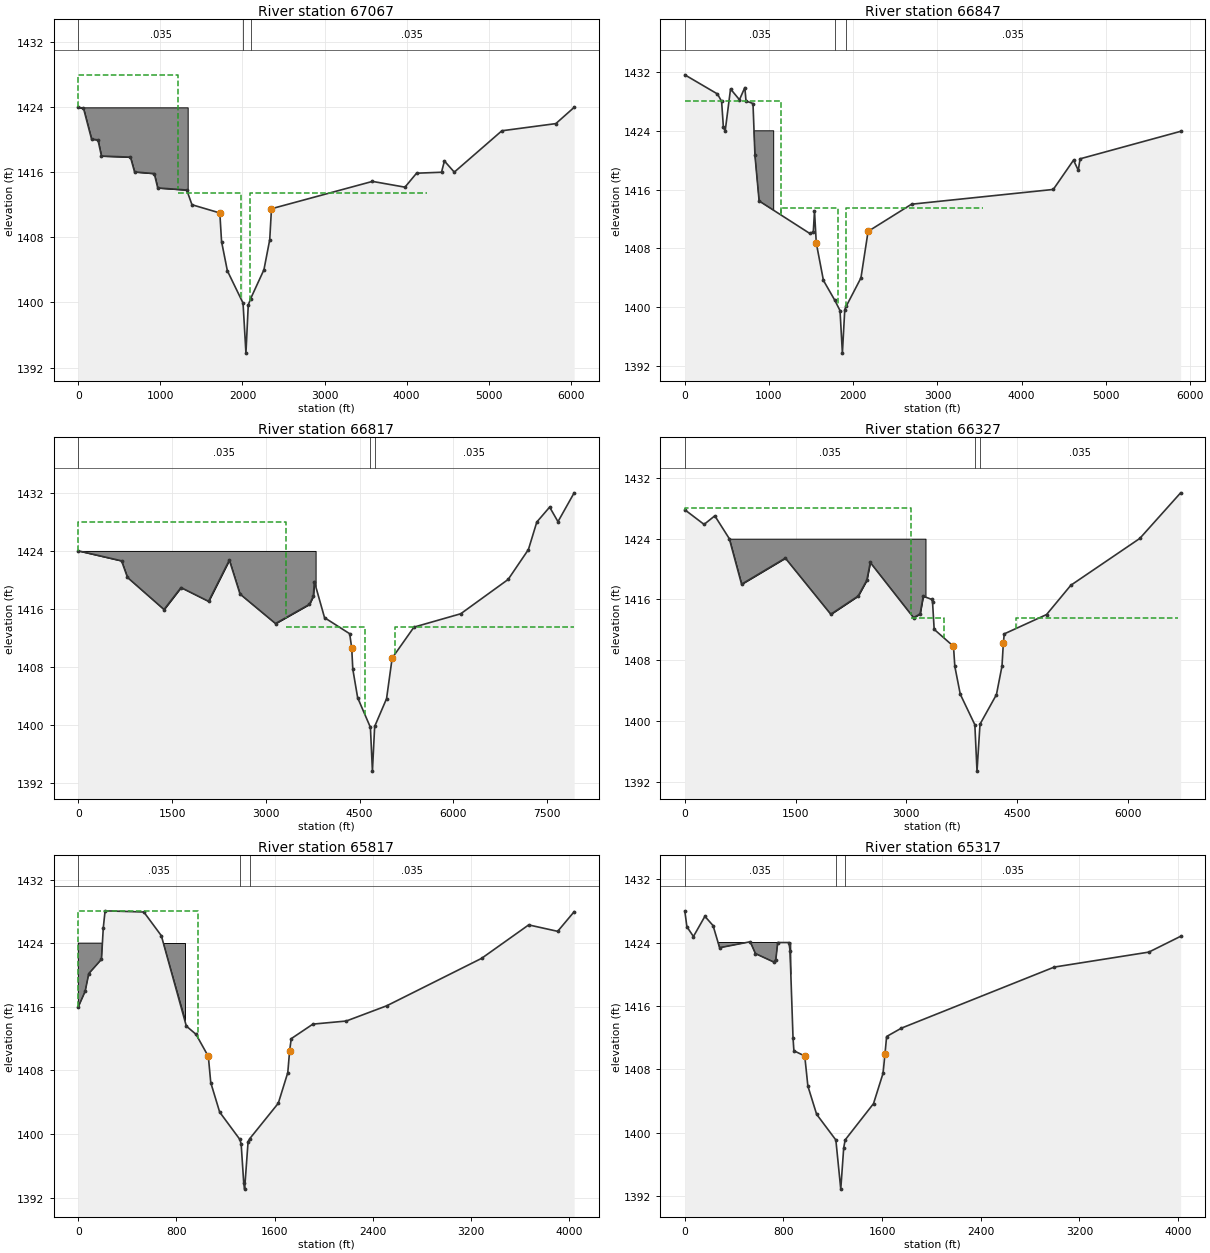
Type RM Length L Ch R = 1 ,67067   ,220,220,220
BEGIN DESCRIPTION:
Section Taken Just Upstream of Goetz Road - This section will be skewed with Bridge  jcc 11 DEC 2009
END DESCRIPTION:
XS GIS Cut Line= 2
     6265803.439     2215602.343     6265778.971     2224145.867
#Sta/Elev= 30
       01424.016  62.2561423.898 161.2511420.089 239.033    1420  281.461418.011
 635.015 1417.88 685.0291416.059  924.931415.854 967.3561414.0881320.9111413.833
1384.5511412.0221723.9641411.0081745.1771407.4841815.8881403.8982006.8071399.924
2042.1631393.7692070.4481399.6782098.7321400.4562261.3671404.0222332.0781407.723
2353.291 1411.533583.6621414.8913979.6441414.1834121.065  1415.94425.1221416.018
4460.4781417.4014580.6871416.0315160.5171421.1185818.128    14226041.208    1424
#Mann= 3 ,-1 , 0
       0    .035       02006.807     .07       02098.732    .035       0
#XS Ineff= 3 ,-1
       01214.102    14281214.1021986.093  1413.52086.9554242.641  1413.5
Permanent Ineff=
       T       T       T
#Block Obstruct= 2 , 0
       01332.189    14243375.021       0    1424
Bank Sta=1723.964,2353.291
XS Rating Curve= 0 ,0
Skew Angle= 45
Exp/Cntr=0.5,0.3

Type RM Length L Ch R = 1 ,66847   ,30,30,30
BEGIN DESCRIPTION:
Section Taken Just Downstream of Goetz Road - This section will be skewed with Bridge  jcc 11 DEC 2009
END DESCRIPTION:
XS GIS Cut Line= 2
     6265647.533     2215702.258     6265623.687     2224029.063
#Sta/Elev= 30
       01431.627 387.5861429.022 437.0841428.018 458.2981424.478 479.5111423.966
 543.1511429.698 649.2171428.236 712.8571429.895 726.9991428.064 809.8321427.719
 833.0661420.647 882.5631414.4411483.5151410.0181526.033 1410.221540.175 1413.08
1561.2571408.7221646.2411403.6171780.5921400.9241843.2941399.5021871.4971393.708
1899.7011399.6411916.0911400.0792091.7211403.9552176.5731410.2972692.764    1414
4375.685 1416.014616.103    14204672.6711418.6144693.8841420.1835887.9641423.928
#Mann= 3 ,-1 , 0
       0    .035       01780.592     .07       01916.091    .035       0
#XS Ineff= 3 ,-1
       01146.927    14281146.927 1814.04  1413.51914.9023535.534  1413.5
Permanent Ineff=
       T       F       F
#Block Obstruct= 2 , 0
       0 1055.71    14243228.649       0    1424
Bank Sta=1561.257,2176.573
XS Rating Curve= 0 ,0
Skew Angle= 45
Exp/Cntr=0.5,0.3

Type RM Length L Ch R = 1 ,66817   ,488.943,490.173,495.119
XS GIS Cut Line= 2
     6268787.315     2214851.759      6263416.04     2220689.036
#Sta/Elev= 30
       01424.011 691.1921422.632 786.3171420.346 1370.661415.9311642.4471418.957
2083.9071417.0572415.9841422.7382586.3871418.0653154.402    14143697.5031416.649
3759.9041417.7673775.9781419.7813939.0511414.8084341.5261412.599 4373.911410.615
4391.0671407.7264468.9161403.7824672.876 1399.714705.0791393.6864740.8231399.834
4931.074 1403.665020.9361409.2525369.6551413.5096117.8981415.3496876.027 1420.07
7200.4991424.1857335.1721427.979 7540.411430.0317673.5191428.025 7932.491431.996
#Mann= 3 ,-1 , 0
       0    .035       04672.876     .07       04740.823    .035       0
#XS Ineff= 3 ,-1
       0    3325    1428    3325    4590  1413.5    5063 7932.49  1413.5
Permanent Ineff=
       T       F       F
#Block Obstruct= 2 , 0
       0    3796    1424    6028       0    1424
Bank Sta=4373.91,5020.936
XS Rating Curve= 0 ,0
Exp/Cntr=0.3,0.1

Type RM Length L Ch R = 1 ,66327   ,512.084,509.915,510.645
XS GIS Cut Line= 6
    6267944.6375    2215068.9381    6265311.6366    2217905.6875
      6265242.75    2217979.9049    6264399.7486      2218888.14
    6264393.0136     2218895.396    6263394.9866    2219970.6531
#Sta/Elev= 30
       01427.813 261.2061425.878 406.6491427.012 602.2991424.011 769.139    1418
1361.9051421.438 1977.681414.0422348.6941416.4442465.7571418.5222512.4191420.866
3099.0981413.5943187.5061414.0823229.9611416.4233344.685    14163356.2521415.682
3378.5571412.0533640.3681409.8163658.4911407.1653732.3551403.5013929.532 1399.49
3958.9311393.3753999.5831399.5644222.0261403.4534297.3541407.2114315.8341410.275
4328.1661411.458 4901.321414.0045229.9631417.861 6164.19 1424.036717.493 1430.04
#Mann= 3 ,-1 , 0
       0    .035       03929.532     .07       03999.583    .035       0
#XS Ineff= 3 ,-1
       0    3068    1428    3068    3517  1413.5    4486 6687.76  1413.5
Permanent Ineff=
       T       F       F
#Block Obstruct= 2 , 0
       0    3261    1424    5116       0    1424
Bank Sta=3640.368,4315.834
XS Rating Curve= 0 ,0
Exp/Cntr=0.3,0.1

Type RM Length L Ch R = 1 ,65817   ,510.902,499.882,492.717
XS GIS Cut Line= 6
    6265799.1095    2216622.3803    6265003.0642    2217487.4889
    6264943.4484    2217552.2767    6264628.0409    2217895.0485
    6264144.0191    2218421.0629    6263070.3566    2219587.8743
#Sta/Elev= 30
       0    1416  55.6971417.944  85.2341420.171 188.6121421.966 203.3811425.916
 218.1491428.063 533.9581427.914 676.7581424.937 880.5991413.574 959.4671412.541
1059.945 1409.761079.7791406.4661152.3861402.7631315.4581399.359 1327.48 1398.77
1348.7111393.8281355.7881393.0811384.0971399.0561398.2511399.4361630.3751403.877
1707.7151407.7231722.4831410.429 1735.871411.9941912.5321413.8232184.319 1414.21
2515.021 1416.133287.9291422.0893671.9061426.294  3908.21425.486 4042.651427.953
#Mann= 3 ,-1 , 0
       0    .035       01315.458     .07       01398.251    .035       0
#XS Ineff= 2 , 0
       0     979    1428               0
Permanent Ineff=
       T       F
#Block Obstruct= 2 , 0
       0     866    1424    2561       0    1424
Bank Sta=1059.945,1722.483
XS Rating Curve= 0 ,0
Exp/Cntr=0.3,0.1

Type RM Length L Ch R = 1 ,65317   ,585.896,499.588,419.787
XS GIS Cut Line= 2
     6265337.133     2216337.679     6262691.738     2219366.285
#Sta/Elev= 30
       01428.007  16.872    1426  69.9821424.763 162.9251427.313 229.313 1426.14
 282.3841423.345 530.436  1424.1 572.9591422.605 721.7891421.538 738.3691421.855
  753.57    1424 844.776    1424 853.3611422.994 877.7071411.979 884.7941410.333
  972.861409.666 998.189 1405.871069.0611402.3091225.134 1399.061264.9671392.853
1288.7631398.0711300.8061399.0781530.5191403.6531607.6861407.4781623.462  1409.9
 1636.741412.1311756.5171413.1862996.7731420.9043763.3681422.7924021.265 1424.79
#Mann= 3 ,-1 , 0
       0    .035       01225.134     .07       01300.806    .035       0
#Block Obstruct= 2 , 0
       0     860    1424    2395       0    1424
Bank Sta=972.86,1623.462
XS Rating Curve= 0 ,0
Exp/Cntr=0.3,0.1