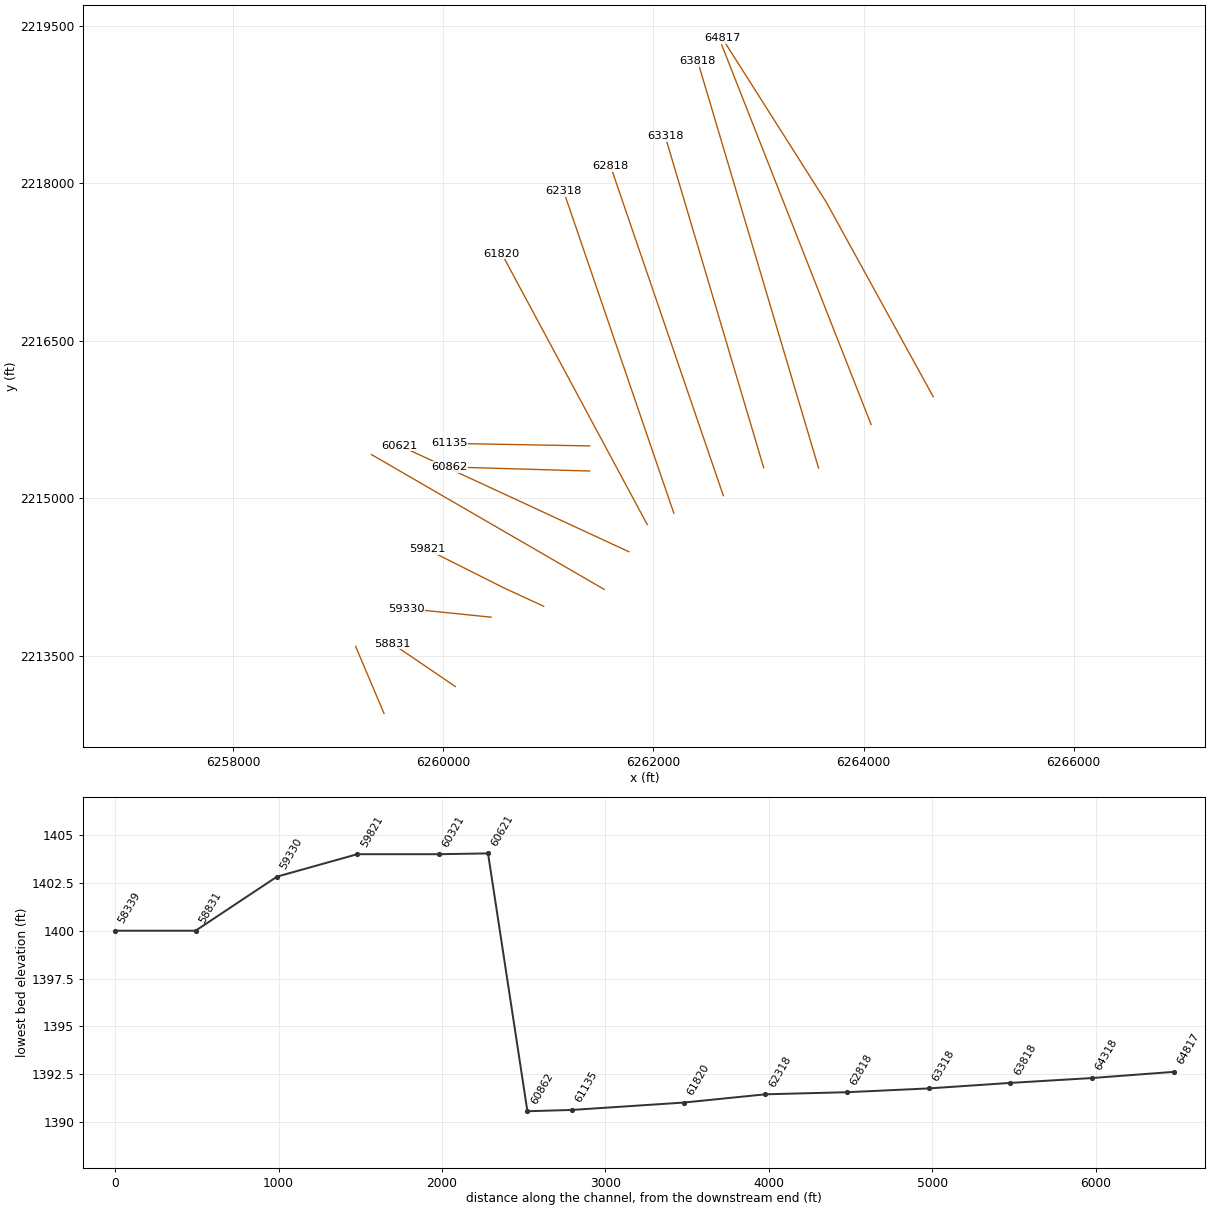
HEC-RAS study R3.prj: San Jacinto Stage III Reach 3

--- R3.g33 (geometry) --- (continued)

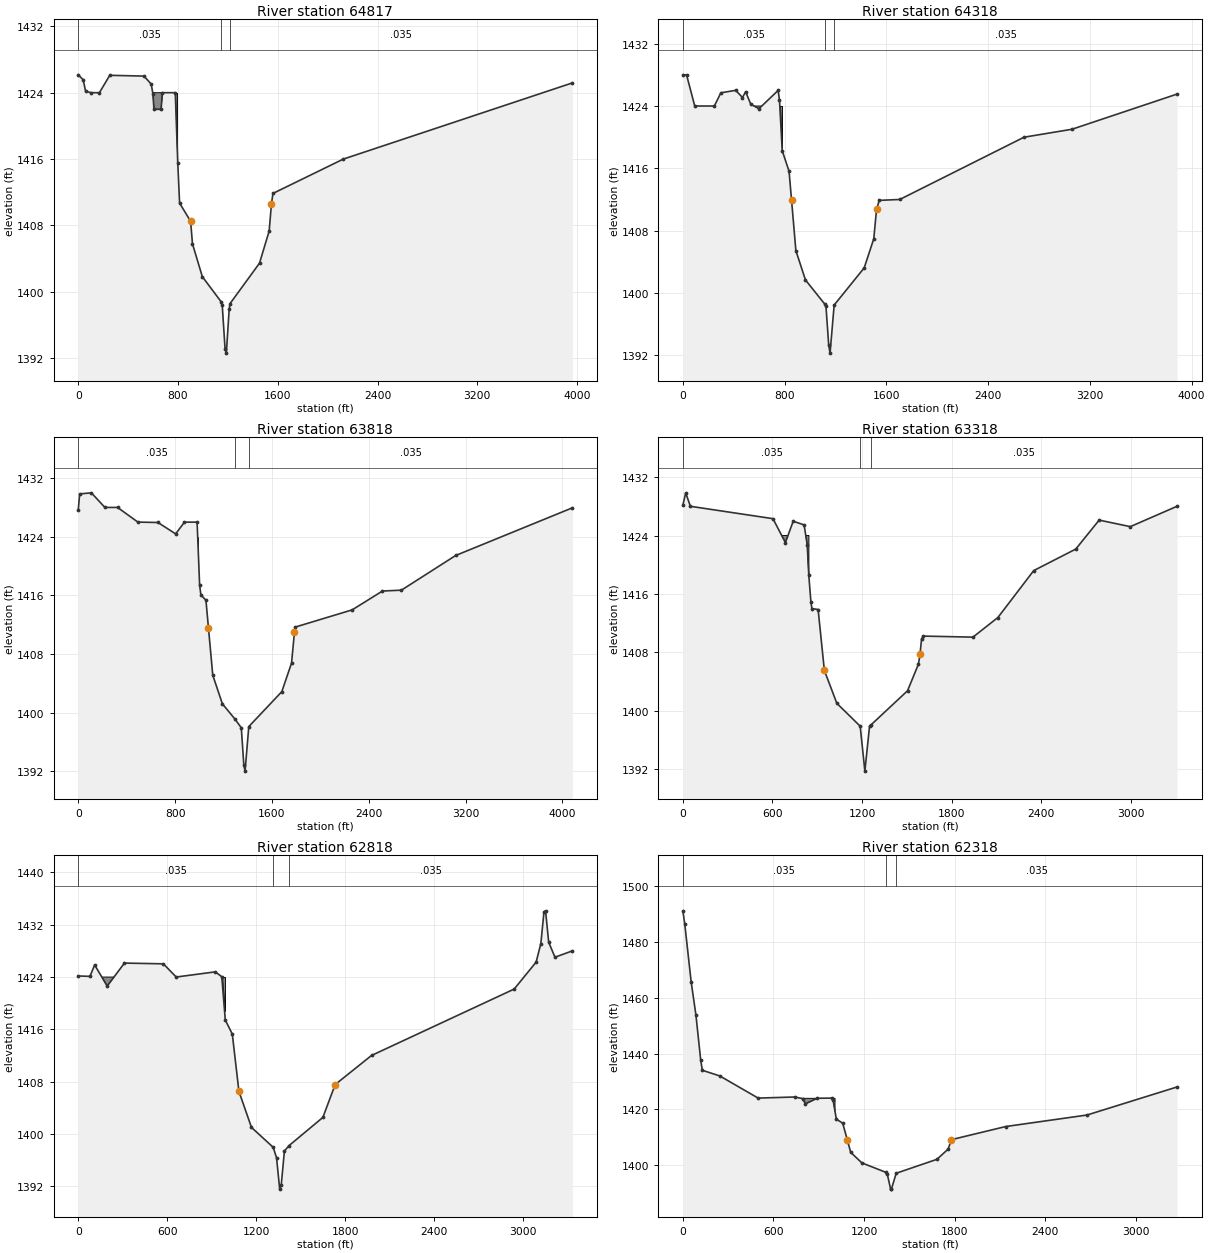
Type RM Length L Ch R = 1 ,64817   ,549.221,499.439,451.105
XS GIS Cut Line= 3
     6264663.061     2215968.432     6263644.063     2217823.711
     6262655.654       2219382.4
#Sta/Elev= 30
       01426.153  39.487 1425.56  59.2741424.158 104.911    1424 169.638    1424
 252.7281426.095 527.046    1426 585.0851425.034 599.172 1423.83  606.91    1422
 663.9551421.994 675.364    1424 778.046    1424 798.008 1415.52 812.7371410.694
 901.1081408.504 915.8371405.795 994.8181401.8411145.9391398.8051154.5451398.403
1177.3631393.1271187.4841392.6211210.4081397.9381217.772  1398.61453.4291403.459
1531.0441407.3391549.1651410.6041561.3861411.8642124.6031415.995 3962.36 1425.18
#Mann= 3 ,-1 , 0
       0    .035       01145.939     .07       01217.772    .035       0
#Block Obstruct= 2 , 0
       0     795    1424    2269       0    1424
Bank Sta=901.108,1549.165
XS Rating Curve= 0 ,0
Exp/Cntr=0.3,0.1

Type RM Length L Ch R = 1 ,64318   ,532.348,499.504,468.255
XS GIS Cut Line= 2
     6264072.036     2215703.426     6262650.272     2219318.767
#Sta/Elev= 30
       0    1428  29.0741427.998  93.443    1424 247.667    1424 298.9361425.697
 415.807 1426.01  468.611425.087 493.5851425.832 534.0071424.225  598.481423.656
 748.916    1426 759.6621424.758 781.1531418.268  834.881415.629 854.2341411.983
 888.6081405.446 963.8261401.6861116.4581398.5711125.0081398.3451146.4991393.355
1157.2451392.2991189.4811398.4671425.8811403.241  1501.11406.9761522.5911410.734
1544.0821411.8961705.2641412.0112682.0911419.9973059.1941421.0183884.8561425.528
#Mann= 3 ,-1 , 0
       0    .035       01116.458     .07       01189.481    .035       0
#Block Obstruct= 2 , 0
       0     780    1424    2235       0    1424
Bank Sta=854.234,1522.591
XS Rating Curve= 0 ,0
Exp/Cntr=0.3,0.1

Type RM Length L Ch R = 1 ,63818   ,500.024,500,500.222
XS GIS Cut Line= 6
    6263571.6532    2215289.0961    6263217.3778    2216482.3522
    6262895.6989    2217565.8176    6262782.8345    2217945.9632
    6262578.2574    2218635.0111    6262421.0415    2219164.5396
#Sta/Elev= 30
       01427.629  11.7771429.842 108.1621429.992 220.406    1428  324.72    1428
 492.791    1426 658.5261425.946 804.5661424.395 877.5861425.993   981.9    1426
1002.7631417.3861013.1951416.0761054.9261415.3431075.7831411.554 1111.231405.132
1190.5291401.2281293.9931399.1541347.0011397.9591367.8631392.8831378.2951392.044
1408.8351398.1161681.744 1402.881762.1841406.7811786.3081411.0031793.4781411.691
2262.8931414.0312513.2471416.6012669.7191416.719 3118.27 1421.454082.2951427.948
#Mann= 3 ,-1 , 0
       0    .035       01293.993     .07       01408.835    .035       0
#Block Obstruct= 2 , 0
       0     993    1424    2480       0    1424
Bank Sta=1075.783,1786.308
XS Rating Curve= 0 ,0
Exp/Cntr=0.3,0.1

Type RM Length L Ch R = 1 ,63318   ,484.415,499.819,514.433
XS GIS Cut Line= 6
    6263049.1812    2215292.1281    6262735.8303    2216347.5437
    6262534.2464    2217026.5107    6262438.7653    2217348.1059
    6262417.2653    2217420.5217    6262111.5792    2218450.1211
#Sta/Elev= 30
       01428.143  19.0451429.844   50.34    1428 603.2061426.306 686.6571423.039
 738.8151425.953 811.8351425.455 832.6971422.762 843.129 1418.57 857.4581414.904
 863.992    1414 905.7181413.875 947.4431405.5451030.8951401.0411187.3661397.904
1218.6611391.7561249.9551397.881 1257.071398.0341504.3391402.7541577.3591406.391
 1587.791407.7191598.2211409.8021608.6531410.2371942.4591410.0942109.3621412.779
2349.285  1419.22630.9341422.1472787.4051426.1112996.0341425.2163308.701    1428
#Mann= 3 ,-1 , 0
       0    .035       01187.366     .07       0 1257.07    .035       0
#Block Obstruct= 2 , 0
       0     844    1424    2242       0    1424
Bank Sta=947.443,1587.79
XS Rating Curve= 0 ,0
Exp/Cntr=0.3,0.1

Type RM Length L Ch R = 1 ,62818   ,501.027,500.015,500.265
XS GIS Cut Line= 6
    6262665.1355     2215025.788    6262628.7483    2215132.1668
    6261844.0206    2217426.3413    6261696.8594    2217856.5717
    6261660.8127     2217961.955    6261592.5569    2218161.5032
#Sta/Elev= 30
       01424.164  78.8411424.103 110.5481425.848 195.0981422.618 311.3551426.134
 573.5751426.021 660.1261424.001 924.3471424.796 967.3311424.043 990.9561417.427
1038.2071415.2771082.8791406.507 1167.431400.9991313.8361397.9541336.5311396.339
1357.6681391.5581368.2371392.2461389.375 1397.391421.0811398.2261648.5961402.526
1731.6051407.5571976.5231412.0042937.9921422.1623085.9561426.2873117.6621429.125
  3138.81433.9713149.3691434.1283170.5061429.3223212.7821427.031 3330.221428.005
#Mann= 3 ,-1 , 0
       0    .035       01313.836     .07       01421.081    .035       0
#Block Obstruct= 2 , 0
       0     986    1424    2457       0    1424
Bank Sta=1082.879,1731.605
XS Rating Curve= 0 ,0
Exp/Cntr=0.3,0.1

Type RM Length L Ch R = 1 ,62318   ,441.519,498.258,545.036
XS GIS Cut Line= 6
    6262193.9493    2214858.4017    6261870.8543    2215802.9796
    6261774.1023    2216085.8366    6261709.8765    2216273.6029
    6261687.9728    2216337.6387    6261145.1096    2217924.7155
#Sta/Elev= 30
       01491.213  12.6661486.458  54.9411465.783  86.6871453.821 118.3541437.644
 128.9231434.062  245.18 1432.01 498.8321424.083 741.9151424.476 794.7591423.863
 811.693    1422 889.8781424.031 984.9971424.074 995.5661423.3661016.7041416.539
1058.9791415.085 1090.341408.9491111.8231404.6531185.8051400.8561344.3371397.484
1354.906 1396.711376.0441391.5521381.7191391.448 1413.221397.1361683.8641402.147
1757.8461405.8211778.983 1409.182138.3231413.8792677.333 1418.013273.7631428.065
#Mann= 3 ,-1 , 0
       0    .035       01344.337     .07       0 1413.22    .035       0
#Block Obstruct= 2 , 0
       0    1008    1424    2513       0    1424
Bank Sta=1090.34,1778.983
XS Rating Curve= 0 ,0
Exp/Cntr=0.3,0.1

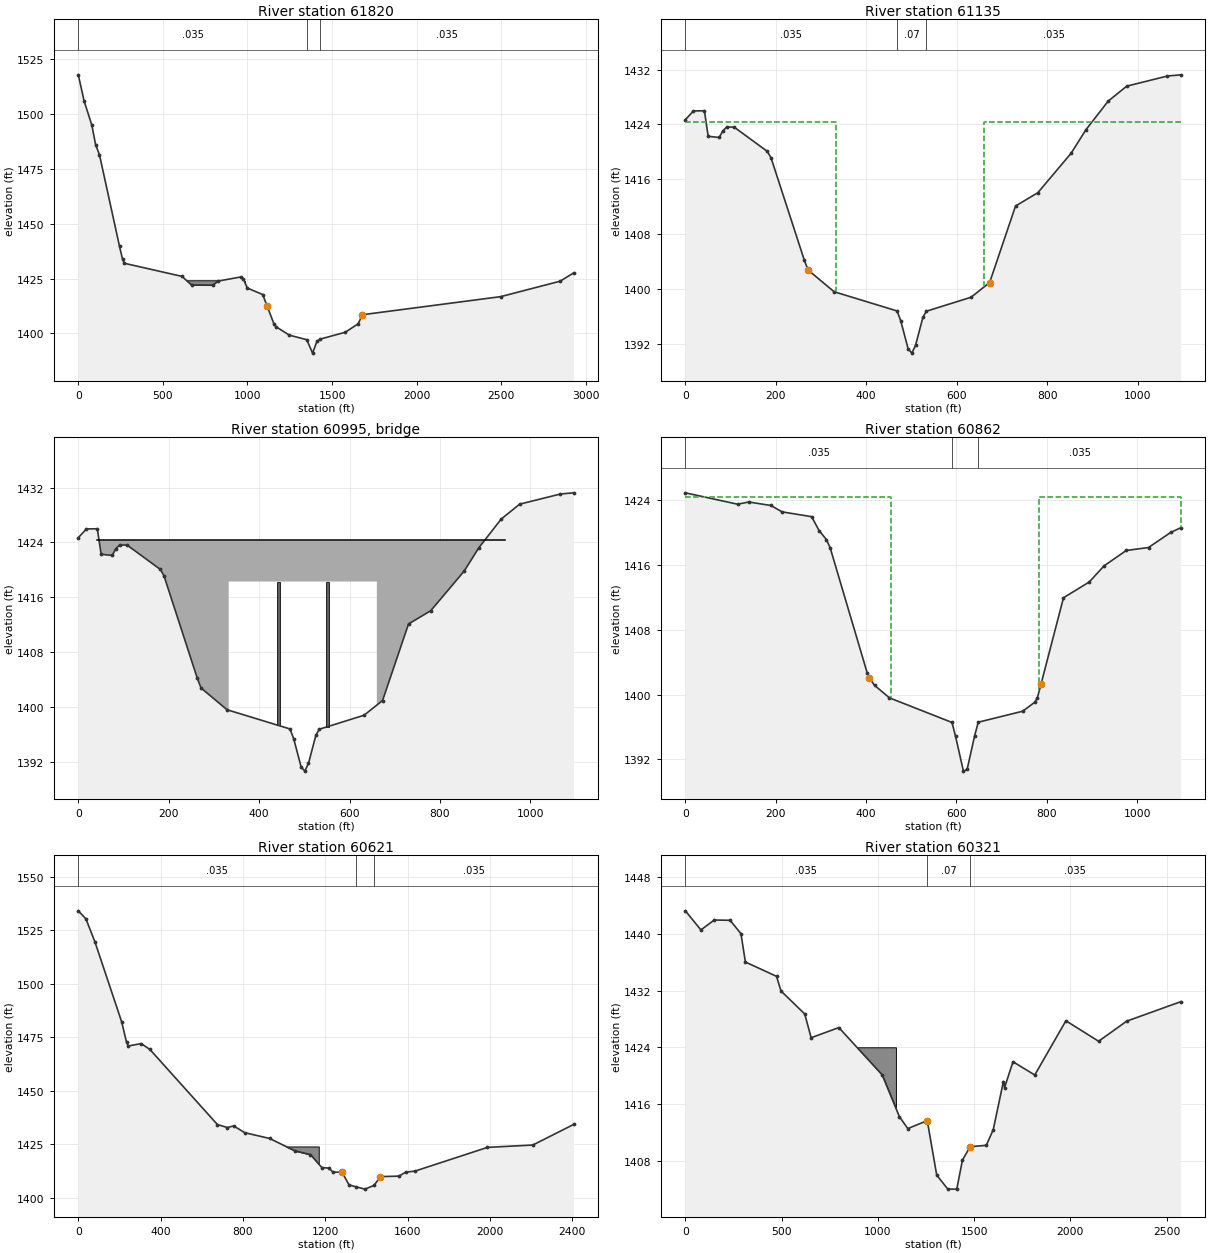
Type RM Length L Ch R = 1 ,61820   ,685,685,685
XS GIS Cut Line= 2
     6261940.961      2214750.17     6260556.217     2217330.166
#Sta/Elev= 30
       01517.877  34.2931505.969   79.691495.008 102.3891486.028 125.088 1481.45
 243.5571439.699  261.281433.912 272.6291431.966 613.1091425.998 669.8551422.026
 794.6981421.961 828.7461423.893 959.9411425.725 976.2871424.749 998.9861420.701
 1089.781417.7361115.0351412.7121157.8761404.0811169.2251403.0311247.9721399.198
1350.8151397.1341384.8631391.0171410.4511396.329 1430.261397.4081577.8011400.519
1654.1691404.3651679.9451408.5232497.0971416.7632848.926 1423.822928.1221427.576
#Mann= 3 ,-1 , 0
       0    .035       01350.815     .07       0 1430.26    .035       0
#Block Obstruct= 2 , 0
       0     987    1424    2470       0    1424
Bank Sta=1115.035,1679.945
XS Rating Curve= 0 ,0
Exp/Cntr=0.3,0.1

Type RM Length L Ch R = 1 ,61135   ,273,273,273
XS GIS Cut Line= 2
     6261392.762     2215499.533     6260055.762     2215523.533
#Sta/Elev= 30
       01424.696  17.8831425.973  42.084    1426  50.4841422.278  74.8551422.099
  83.048 1423.08   91.241423.613 107.6271423.628 181.3621420.068 189.5551419.119
  263.29 1404.15 271.4831402.762 328.8331399.591 468.1111396.787 476.3041395.371
  492.691391.259 500.8831390.631 509.0751391.763 525.4611395.874 532.9781396.745
 631.9681398.787 672.9331400.936 730.2821412.103  779.441414.035 853.1751419.805
 885.9471423.236 935.1031427.406 976.067 1429.591066.1891431.0711095.3821431.244
#Mann= 3 ,-1 , 0
       0    .035       0 468.111     .07       0 532.978    .035       0
#XS Ineff= 2 , 0
       0 332.576  1424.3 660.237       0  1424.3
Permanent Ineff=
       F       F
Bank Sta=271.483,672.933
XS Rating Curve= 0 ,0
Skew Angle= 35
Exp/Cntr=0.5,0.3

Type RM Length L Ch R = 3 ,60995   ,,,
BEGIN DESCRIPTION:
Proposed Ethanace Road
END DESCRIPTION:
Bridge Culvert--1,0,-1,-1, 0
Deck Dist Width WeirC Skew NumUp NumDn MinLoCord MaxHiCord MaxSubmerge Is_Ogee
71,140,2.6,35, 6, 6, 1424.3, , 0.98, 0, 2,2,,
  42.088 332.576 332.576 660.237 660.237 943.295
  1424.3  1424.3  1424.3  1424.3  1424.3  1424.3
                  1418.3  1418.3
       0 455.449 455.449 783.109 783.1091096.492
  1424.3  1424.3  1424.3  1424.3  1424.3  1424.3
                  1418.3  1418.3
Pier Skew, UpSta & Num, DnSta & Num=  ,442, 2 ,554, 2 , 0 , 0 , 0 ,,
       6       6
    1390    1430
       6       6
    1390    1430
Pier Skew, UpSta & Num, DnSta & Num=  ,551, 2 ,663, 2 , 0 , 0 , 0 ,,
       6       6
    1390    1430
       6       6
    1390    1430
Abutment Skew #Up #Dn= , 3 , 3
 332.576  335.58  360.41
  1415.3  1415.3 1398.75
 455.449 458.449 483.334
  1415.3  1415.3  1398.7
Abutment Skew #Up #Dn= , 3 , 3
 631.947 657.237 660.237
 1398.44  1415.3  1415.3
 757.096 780.109 783.109
 1397.94  1415.3  1415.3
BR Coef=-1 , 1 , 0 ,, 0 ,,,0.8,0,1.2,0,
WSPro=,,,, 1 ,,,, 0 ,,,, 0 ,,,,-1 ,-1 ,-1 , 0 , 0 , 0 , 0 , 0
BC Design=,, 0 ,, 0 ,,,,,,
BC Use User HTab Curves=0
BC User HTab FreeFlow(D)= 0

Type RM Length L Ch R = 1 ,60862   ,241,241,241
XS GIS Cut Line= 2
     6261392.555     2215260.268     6260054.555     2215299.268
#Sta/Elev= 30
       01424.854  115.68 1423.45 140.2651423.724 189.4351423.294  214.021422.508
  279.581421.916  295.971420.207  312.361419.088 320.5551418.082 402.5051402.678
 407.1251402.044 418.8951401.132 451.6751399.595 590.2711396.559 598.2341394.832
 615.5751390.563  623.771390.769  640.161394.856 648.355 1396.59 746.6951397.942
 773.4181399.046 779.4751399.618  787.671401.352 837.1211411.926 894.205 1413.87
 926.9851415.857 976.1551417.7521025.3251418.1161074.4951419.9761096.4911420.545
#Mann= 3 ,-1 , 0
       0    .035       0 590.271     .07       0 648.355    .035       0
#XS Ineff= 2 , 0
       0 455.449  1424.3 783.109       0  1424.3
Permanent Ineff=
       F       F
Bank Sta=407.125,787.67
XS Rating Curve= 0 ,0
Skew Angle= 35
Exp/Cntr=0.5,0.3

Type RM Length L Ch R = 1 ,60621   ,300,300,300
XS GIS Cut Line= 2
     6261764.853     2214491.923     6259581.693     2215503.207
#Sta/Elev= 30
       01534.155  36.8731530.414  80.9561519.598 210.468 1482.31 234.2591472.752
 242.4661470.952 305.6341472.089 347.9121469.328 676.0771434.206 724.5051432.847
 754.6321433.595 808.3261430.441 929.5551427.7191050.783    14221127.9281420.166
1183.0321414.1291216.0951413.8681238.1361411.9821281.0911411.9661315.2811406.014
1348.3441405.1381392.4271404.041 1436.511405.7851467.9741409.8891557.7381410.118
1590.3821411.9871634.8841412.4481987.5481423.5582207.9641424.657 2406.011434.277
#Mann= 3 ,-1 , 0
       0    .035       01348.344     .07       0 1436.51    .035       0
#Block Obstruct= 2 , 0
       0    1168    1424    1683       0    1424
Bank Sta=1281.091,1467.974
XS Rating Curve= 0 ,0
Exp/Cntr=0.3,0.1

Type RM Length L Ch R = 1 ,60321   ,475.681,499.787,516.943
XS GIS Cut Line= 6
    6261531.2769    2214132.6535    6260617.4146    2214662.4741
    6260444.8318    2214762.5307    6260439.9567    2214765.3572
    6259635.9465    2215231.4899    6259315.6303    2215417.1965
#Sta/Elev= 30
       01443.241  80.776 1440.55 150.1311441.944 232.3971441.906  288.841440.022
 311.9581436.023 473.785    1434 496.9031431.941 620.1971428.698 653.4231425.345
 797.4391426.7811022.6311420.107 1111.991414.218 1155.771412.5371256.7751413.658
1306.0381405.9771363.833    14041410.069    14041439.699 1408.091479.4241409.982
1563.7321410.1791599.8361412.3981652.3281419.1611658.4761418.3021702.2081421.967
1815.3741420.0931977.2011427.7392147.1081424.8492293.4481427.6892573.3781430.424
#Mann= 3 , 0 , 0
       0    .035       01256.775     .07       01479.424    .035       0
#Block Obstruct= 2 , 0
       0    1094    1424    1627       0    1424
Bank Sta=1256.775,1479.424
XS Rating Curve= 0 ,0
Exp/Cntr=0.3,0.1

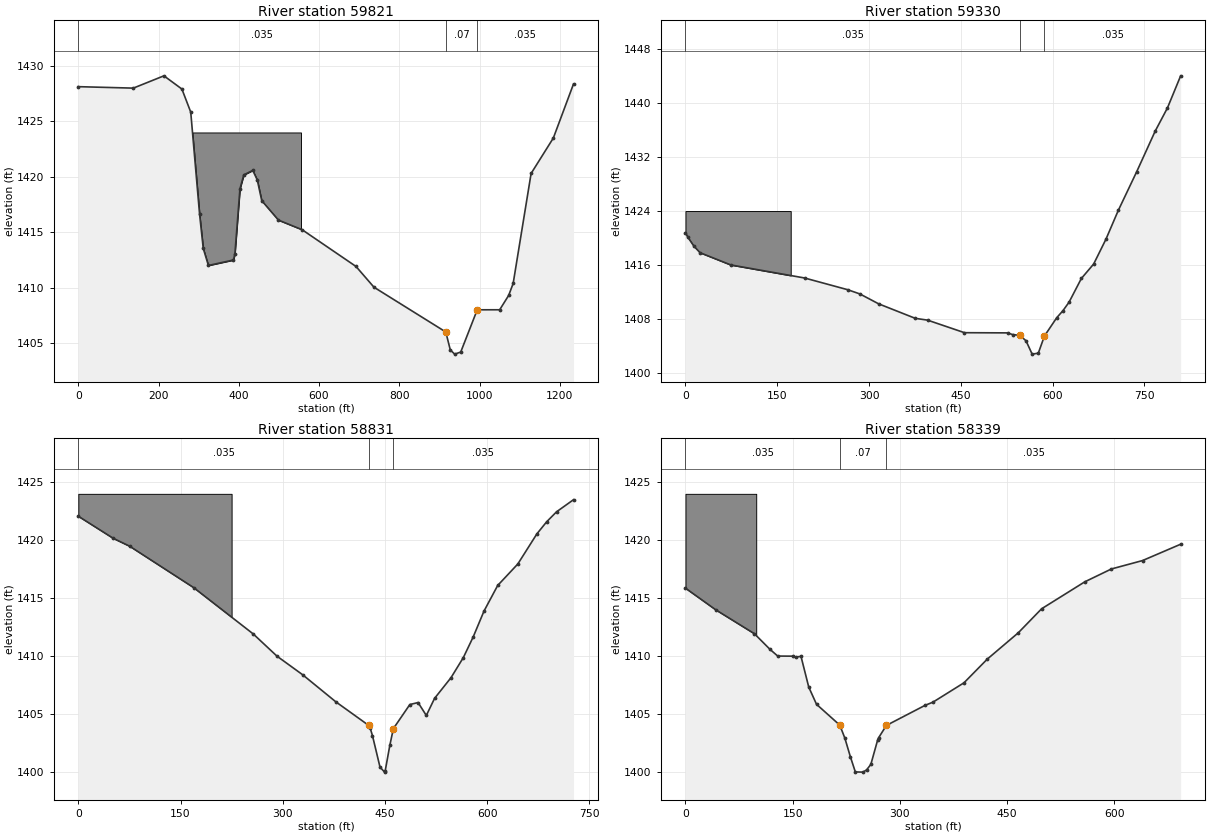
Type RM Length L Ch R = 1 ,59821   ,332.534,491.272,538.845
BEGIN DESCRIPTION:
Blocked Area is WQ Marsh for Adjacent Tract
jcc  20 Aug 2009
END DESCRIPTION:
XS GIS Cut Line= 3
     6260955.898     2213971.706     6260586.032     2214142.223
     6259846.974     2214513.309
#Sta/Elev= 30
       01428.132 137.096    1428 213.431 1429.11 258.2241427.917 280.2471425.836
  302.271416.635  311.411413.538 324.293    1412 386.7791412.494 390.3621413.063
 402.8921418.908 412.4681420.172 434.8471420.579 446.0371419.721 457.2271417.845
 498.7581416.094 557.9351415.224 692.2121411.909 736.9711410.036 915.9241405.998
 927.198 1404.38  938.04    1404 953.1711404.186 994.336    14081050.2851408.002
1072.6651409.2971083.8541410.3731128.6141420.3011184.1021423.5041234.2691428.373
#Mann= 3 , 0 , 0
       0    .035       0 915.924     .07       0 994.336    .035       0
#Block Obstruct= 2 , 0
       0     555    1424    1104       0    1424
Bank Sta=915.924,994.336
XS Rating Curve= 0 ,0
Exp/Cntr=0.3,0.1

Type RM Length L Ch R = 1 ,59330   ,700.378,498.855,440.172
XS GIS Cut Line= 2
     6260454.991     2213867.925     6259649.991     2213949.983
#Sta/Elev= 30
       01420.783   3.6141420.162  13.6661418.822  23.7181417.844  73.9771416.031
 194.5991414.097 264.9611412.365 285.0651411.734 315.6711410.271 375.5311408.125
 395.6351407.858 455.946    1406 526.3091405.972 534.5991405.721 546.4121405.604
 556.4641404.805 566.5161402.828 576.5681402.968  586.621405.512 606.7231408.222
 616.7751409.251 626.8271410.517  646.931414.026 667.0341416.164 687.1381419.844
 707.2411424.092 737.3971429.833 767.5521435.828 787.6561439.276 809.1721444.014
#Mann= 3 , 0 , 0
       0    .035       0 546.412     .07       0  586.62    .035       0
#Block Obstruct= 2 , 0
       0     172    1424     651       0    1424
Bank Sta=546.412,586.62
XS Rating Curve= 0 ,0
Exp/Cntr=0.3,0.1

Type RM Length L Ch R = 1 ,58831   ,624.909,491.981,412.339
XS GIS Cut Line= 2
     6260113.691     2213207.505     6259512.807     2213616.378
#Sta/Elev= 30
       0 1422.07  51.1581420.167  75.3491419.484 169.2751415.914 256.7821411.915
 291.637    1410 329.3551408.394 377.7371406.074 426.1191404.033 428.3941403.796
 431.7381403.149  442.791400.437 449.513    1400 450.3111400.071 457.1861402.298
 462.4061403.751 486.5971405.829 498.693    1406 510.7881404.886 522.884 1406.36
 547.0751408.151 565.1521409.882 579.5481411.655 595.4571413.891 615.5371416.098
 645.0461417.947 673.1191420.551 687.5141421.596  701.911422.449   726.81423.494
#Mann= 3 , 0 , 0
       0    .035       0 426.119     .07       0 462.406    .035       0
#Block Obstruct= 2 , 0
       0     225    1424     592       0    1424
Bank Sta=426.119,462.406
XS Rating Curve= 0 ,0
Exp/Cntr=0.3,0.1

Type RM Length L Ch R = 1 ,58339   ,575.329,494.229,395.965
XS GIS Cut Line= 2
     6259434.833     2212951.526     6259164.833     2213589.526
#Sta/Elev= 30
       01415.866  42.1961414.006   96.491411.935 118.2071410.592 129.065 1410.01
 150.783    1410 154.3471409.928 161.6411409.981   172.51407.331 183.359 1405.85
 215.9341404.051 223.0151402.927 230.6451401.341 237.6521400.018  248.51    1400
 253.5341400.202 259.3691400.669 268.7931402.754 270.2271402.965 281.0861404.026
 335.3791405.764 346.2381406.033 389.6721407.704 422.2481409.746 465.6831412.019
 498.2591414.087 558.7231416.413 595.9861417.522 639.4211418.244  692.781419.654
#Mann= 3 , 0 , 0
       0    .035       0 215.934     .07       0 281.086    .035       0
#Block Obstruct= 2 , 0
       0      99    1424     479       0    1424
Bank Sta=215.934,281.086
XS Rating Curve= 0 ,0
Exp/Cntr=0.3,0.1