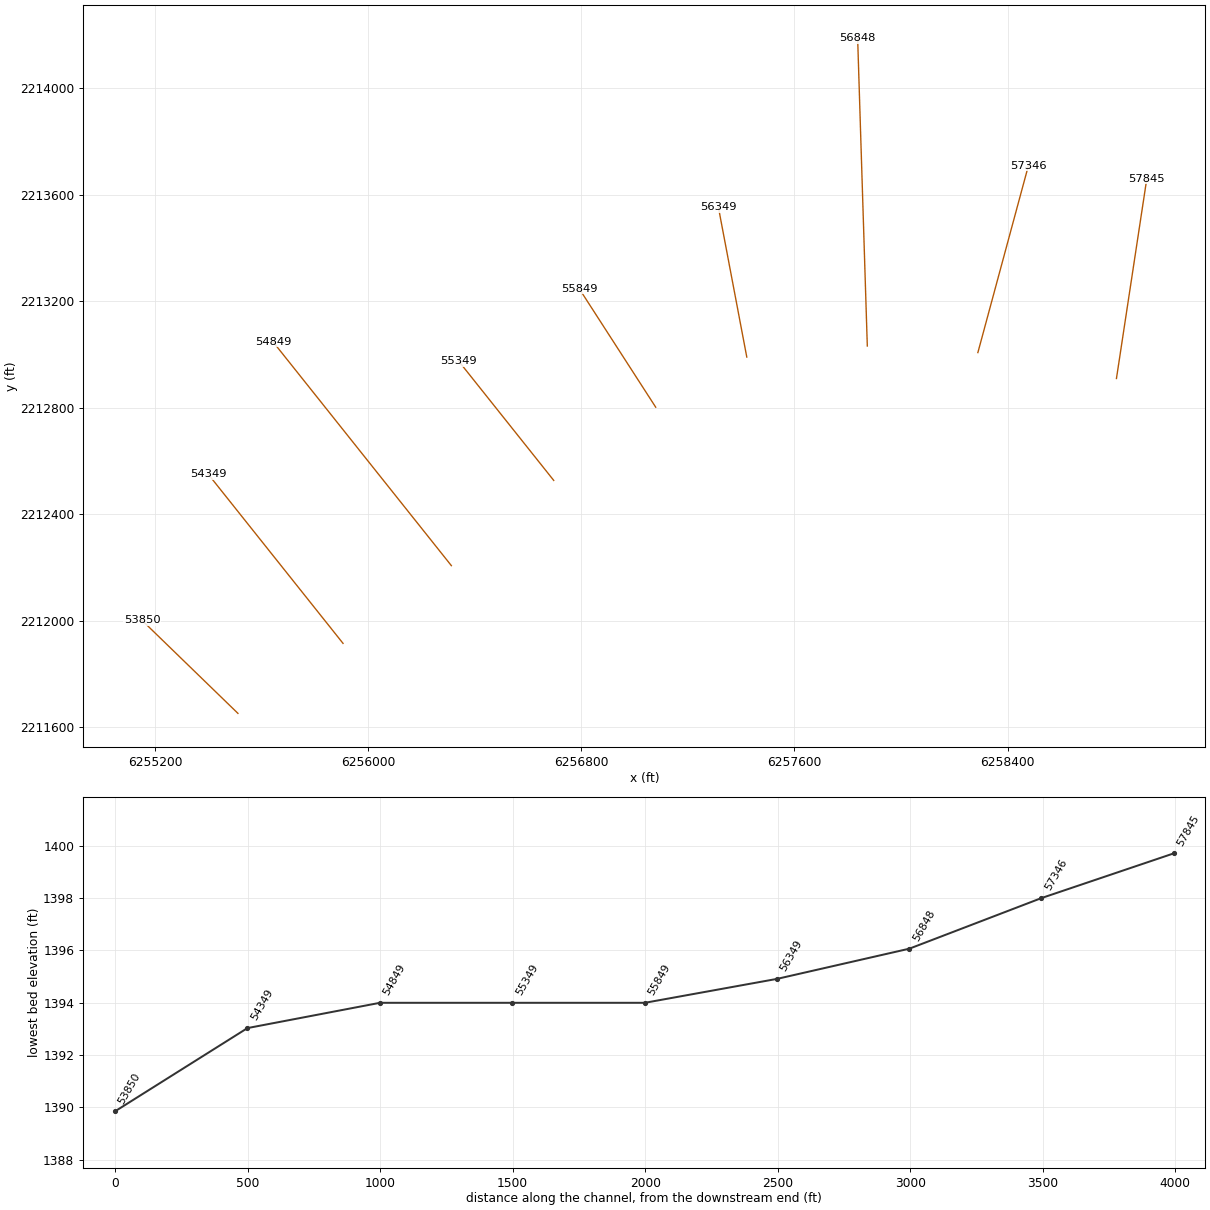
HEC-RAS study R3.prj: San Jacinto Stage III Reach 3

--- R3.g33 (geometry) --- (continued)

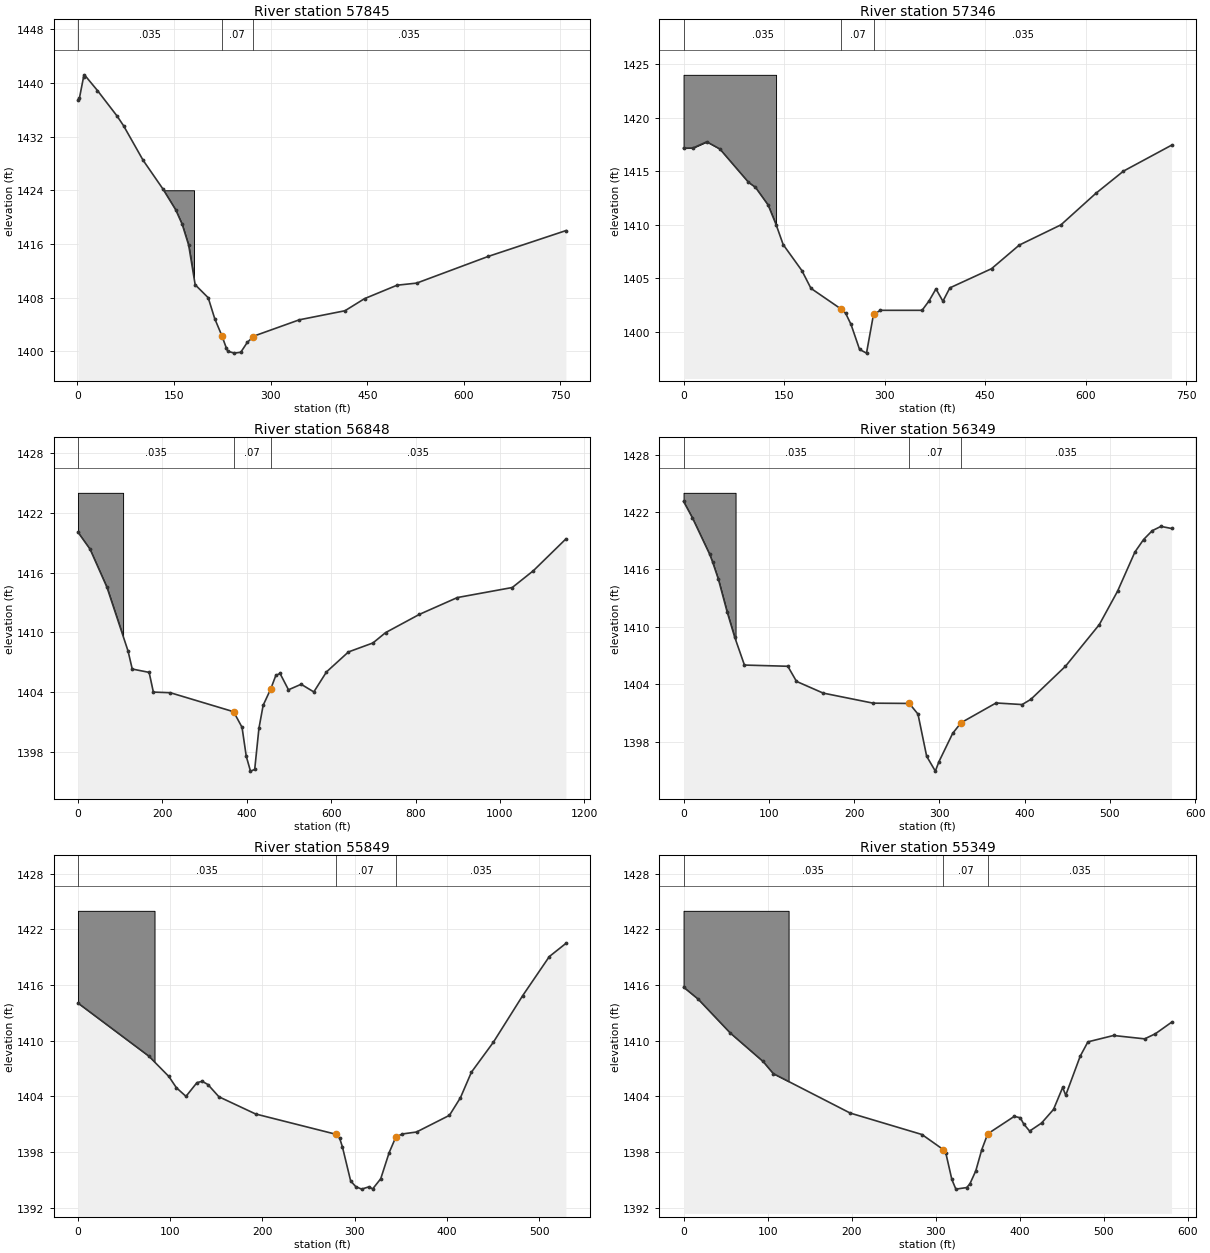
Type RM Length L Ch R = 1 ,57845   ,514.213,499.263,481.295
XS GIS Cut Line= 2
     6258808.677     2212909.698     6258922.502     2213659.637
#Sta/Elev= 30
    .6961437.453   2.9911437.738   9.5031440.931   10.811441.219  31.0391438.874
  61.3831435.083  71.4971433.637 101.8411428.484 132.1851424.263 152.4141421.102
 162.5281418.938 172.6431415.818 182.7571409.908 202.9861407.973 213.1011404.858
 224.1421402.323 231.3151400.427  233.331399.991 243.4441399.708 253.5591399.833
 263.6741401.311  271.841402.048 273.7881402.245  344.591404.681 415.3911406.029
 445.7351407.833 496.308 1409.84 526.651 1410.15 637.9111414.134 758.5281417.984
#Mann= 3 , 0 , 0
    .696    .035       0 224.142     .07       0  271.84    .035       0
#Block Obstruct= 2 , 0
       0     181    1424     546       0    1424
Bank Sta=224.142,271.84
XS Rating Curve= 0 ,0
Exp/Cntr=0.3,0.1

Type RM Length L Ch R = 1 ,57346   ,453.727,498.048,544.871
XS GIS Cut Line= 2
     6258288.506     2213006.936     6258478.324     2213709.609
#Sta/Elev= 30
       01417.151  13.9321417.165  34.6491417.745  54.1021417.075    96.81413.965
 107.1581413.497 126.1161411.841 138.2331409.975 148.592 1408.14 176.4331405.717
 190.0261404.052  235.351402.104 241.8181401.719 249.8311400.675 262.5351398.346
 272.893    1398 283.2521401.588 284.641 1401.65  293.61    1402 355.761    1402
 366.1191402.874 376.478    1404 386.8361402.849 397.1951404.096 459.3451405.887
 500.7791408.096  562.931409.986 614.7221412.915 656.1561415.004  727.861417.425
#Mann= 3 , 0 , 0
       0    .035       0  235.35     .07       0 284.641    .035       0
#Block Obstruct= 2 , 0
       0     138    1424     564       0    1424
Bank Sta=235.35,284.641
XS Rating Curve= 0 ,0
Exp/Cntr=0.3,0.1

Type RM Length L Ch R = 1 ,56848   ,463.71,498.764,521.989
XS GIS Cut Line= 2
     6257873.523     2213031.774     6257837.237     2214187.449
#Sta/Elev= 30
       01420.055  28.6261418.347  68.6461414.531  118.671408.131 128.6751406.314
 168.6951405.979   178.7    1404  218.721403.939 368.7941402.031 388.8031400.469
 398.808 1397.56 408.8131396.068 418.8181396.233 428.8231400.354 438.8281402.675
 456.634  1404.3 468.8431405.667 478.8481405.871 498.8581404.232 528.8721404.786
 558.8871404.017 588.9021406.025 640.9411408.031 698.9561408.932 728.9711409.971
  809.01  1411.8 899.055 1413.491029.1191414.4971079.1431416.1851156.2451419.376
#Mann= 3 , 0 , 0
       0    .035       0 368.794     .07       0 456.634    .035       0
#Block Obstruct= 2 , 0
       0     107    1424     718       0    1424
Bank Sta=368.794,456.634
XS Rating Curve= 0 ,0
Exp/Cntr=0.3,0.1

Type RM Length L Ch R = 1 ,56349   ,400.121,499.315,547.433
XS GIS Cut Line= 2
     6257421.121     2212990.223     6257314.613     2213552.586
#Sta/Elev= 30
       01423.104  10.3441421.396  30.6991417.563  34.1331416.752  40.8771414.962
  51.0551411.579  59.8041408.971   71.41    1406 122.2991405.874 132.4771404.293
 163.774 1403.07 222.3891402.018 264.7881401.989 274.9661400.875 285.1431396.469
 295.3211394.915 299.4031395.875 315.6771398.866  325.561399.976 366.5661402.039
 397.0991401.872 407.2771402.413 447.9881405.878  487.661410.231 509.0541413.719
  529.411417.814 539.5881419.122 549.7651420.045 559.9431420.492  572.361420.273
#Mann= 3 , 0 , 0
       0    .035       0 264.788     .07       0  325.56    .035       0
#Block Obstruct= 2 , 0
       0      61    1424     475       0    1424
Bank Sta=264.788,325.56
XS Rating Curve= 0 ,0
Exp/Cntr=0.3,0.1

Type RM Length L Ch R = 1 ,55849   ,483.814,499.484,509.926
XS GIS Cut Line= 2
     6257079.224     2212801.961     6256792.619     2213246.493
#Sta/Elev= 30
       0 1414.06  76.8651408.335  98.5681406.141 106.7191404.928 117.108    1404
 129.007 1405.48 134.7381405.624 140.9051405.271 152.8031403.954 192.6111402.099
 279.4211399.919 283.6841399.479 286.6551398.555 295.5821394.886 301.1241394.269
  307.48    1394 315.5921394.254 319.3781394.016 328.1731395.117 337.294 1397.93
 344.5281399.609 351.7631399.948 366.9711400.157 402.6661401.956 414.5641403.851
 426.4631406.605 450.2591409.834 481.9771414.847 510.914 1419.07 528.9151420.492
#Mann= 3 , 0 , 0
       0    .035       0 279.421     .07       0 344.528    .035       0
#Block Obstruct= 2 , 0
       0      83    1424     434       0    1424
Bank Sta=279.421,344.528
XS Rating Curve= 0 ,0
Exp/Cntr=0.3,0.1

Type RM Length L Ch R = 1 ,55349   ,501.885,500.002,500.816
XS GIS Cut Line= 6
    6256696.5451    2212526.8543    6256569.2877    2212686.6895
    6256477.0868     2212802.494    6256442.5236    2212845.9052
    6256415.5425    2212879.7936    6256339.4156    2212975.4089
#Sta/Elev= 30
       01415.775  17.2971414.488  55.6441410.823  94.5221407.769 106.7741406.453
 198.3221402.198 283.7191399.887   309.11398.262 312.1851397.864 319.3021395.039
 324.074    1394 336.8571394.167 340.6511394.547 347.7671395.967 354.8841398.251
     3621399.962  393.581401.842 400.7691401.692 404.6991401.039 411.8151400.256
 426.0481401.124 440.2811402.591 451.1411404.956 454.8231404.124 472.0451408.331
 481.2171409.876 511.6931410.561 548.7391410.199 561.4911410.748 580.7251411.987
#Mann= 3 , 0 , 0
       0    .035       0   309.1     .07       0     362    .035       0
#Block Obstruct= 2 , 0
       0     125    1424     454       0    1424
Bank Sta=309.1,362
XS Rating Curve= 0 ,0
Exp/Cntr=0.3,0.1

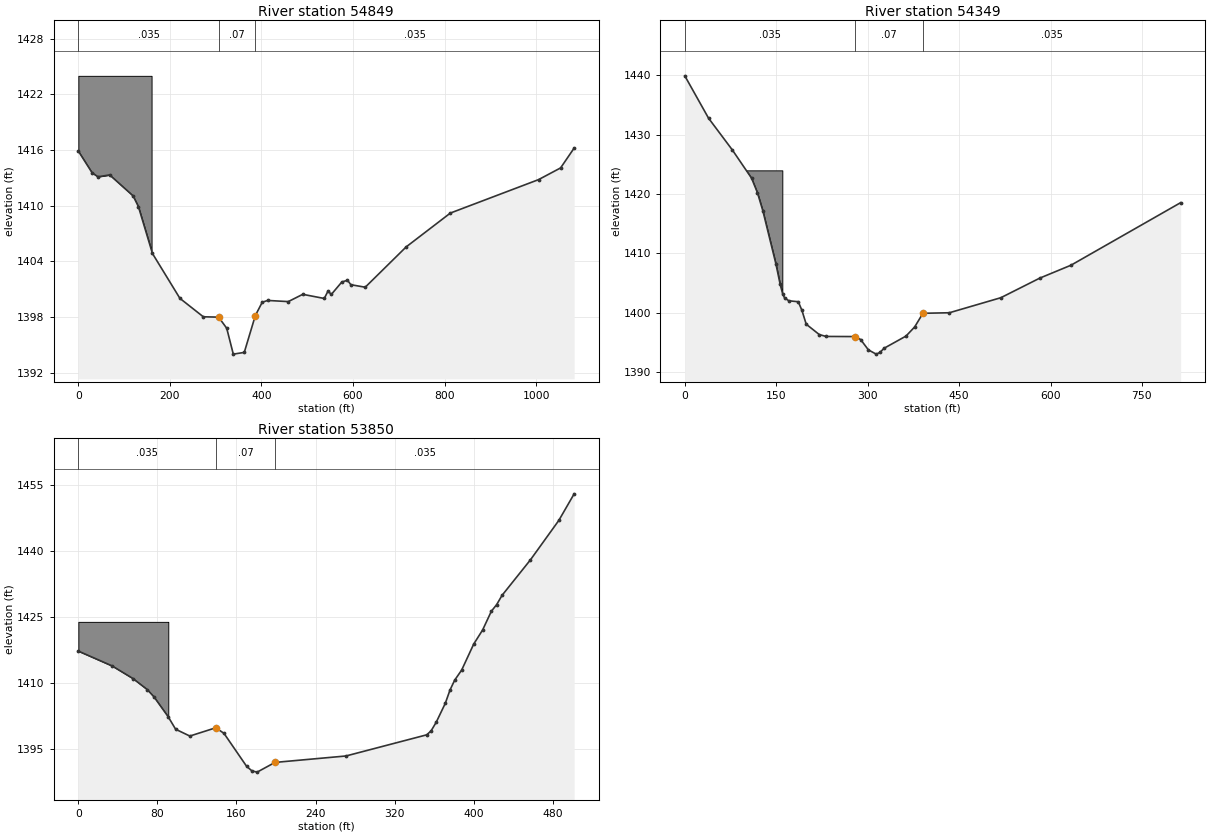
Type RM Length L Ch R = 1 ,54849   ,500.709,500,500.43
XS GIS Cut Line= 6
    6256312.2608    2212206.7801    6256102.3601    2212470.4154
      6256015.49    2212579.5241    6255895.5148    2212730.2131
    6255719.0876    2212951.8055    6255642.9384     2213047.449
#Sta/Elev= 30
       01415.891  30.1741413.542  42.9561413.119  68.5211413.318 119.6511411.059
 131.2781409.896 161.9361404.848  221.911400.012  273.041398.025 306.4281397.988
 324.1691396.791 338.538    1394 362.5171394.185 386.702 1398.16 401.7031399.589
 413.6461399.787 458.6341399.662 490.2761400.446 537.312    1400 545.5391400.807
 552.6561400.432 575.6591401.775 587.9821401.965 595.3541401.483 626.7891401.213
 716.2661405.561 812.7481409.2061005.4051412.8111053.5691414.0731083.2011416.215
#Mann= 3 , 0 , 0
       0    .035       0 306.428     .07       0 386.702    .035       0
#Block Obstruct= 2 , 0
       0     160    1424     708       0    1424
Bank Sta=306.428,386.702
XS Rating Curve= 0 ,0
Exp/Cntr=0.3,0.1

Type RM Length L Ch R = 1 ,54349   ,487.215,499.118,518.069
XS GIS Cut Line= 2
     6255905.662     2211914.732     6255398.978     2212551.128
#Sta/Elev= 30
       01439.926  38.9591432.791  78.2241427.405 109.4861422.691 119.2331420.214
 128.0391417.192 149.3891408.283 156.5051404.771 160.6161403.172 163.622 1402.52
 170.7381402.021 186.1811401.862 192.0871400.429 199.2041398.077 220.5531396.336
 231.6161396.014  279.78 1395.99  288.441395.497 301.2221393.749 314.0051393.034
 320.1831393.314 326.7871394.013 362.8821396.074 377.1151397.614 390.6991399.915
 434.0471400.005 518.5231402.541 582.4351405.843 633.5651408.014 813.4671418.554
#Mann= 3 , 0 , 0
       0    .035       0  279.78     .07       0 390.699    .035       0
#Block Obstruct= 2 , 0
       0     160    1424     538       0    1424
Bank Sta=279.78,390.699
XS Rating Curve= 0 ,0
Exp/Cntr=0.3,0.1

Type RM Length L Ch R = 1 ,53850   ,,,
XS GIS Cut Line= 2
     6255511.186     2211651.813     6255151.296     2212001.195
#Sta/Elev= 30
       01417.361  34.2021413.988  55.4171411.097  69.7331408.615  76.6331406.924
  90.7761402.479  98.4461399.599 112.8021398.054  139.081399.936 147.3511398.663
 170.2281391.179 175.6391390.137 180.8911389.857 198.9411392.065 270.7221393.525
 352.4351398.332 356.8611399.232 362.0751401.206 371.2171405.486 376.0121408.525
 380.7221410.754 387.7941413.049  399.931418.935 409.0091422.164 417.824 1426.41
 423.1531427.903 428.6431430.022 457.3551438.085 486.0681447.043 501.5861453.086
#Mann= 3 , 0 , 0
       0    .035       0  139.08     .07       0 198.941    .035       0
#Block Obstruct= 2 , 0
       0      91    1424     365       0    1424
Bank Sta=139.08,198.941
XS Rating Curve= 0 ,0
Exp/Cntr=0.3,0.1
Stream Node=SJR Stage III   ,4               , 0 , 0 ,Upstream end
Stream Node=SJR Stage III   ,4               , 0 , 1 ,Downstream end
Stream Node=SJR Stage III   ,2               , 0 , 0 ,Upstream end
Stream Node=SJR Stage III   ,2               , 0 , 1 ,Downstream end
Stream Node=SJR Stage III   ,3               , 0 , 0 ,Upstream end
Stream Node=SJR Stage III   ,3               , 0 , 1 ,Downstream end
Stream Node=SJR Stage III   ,1               , 0 , 0 ,Upstream end
Stream Node=SJR Stage III   ,1               , 0 , 1 ,Downstream end
LCMann Table=0